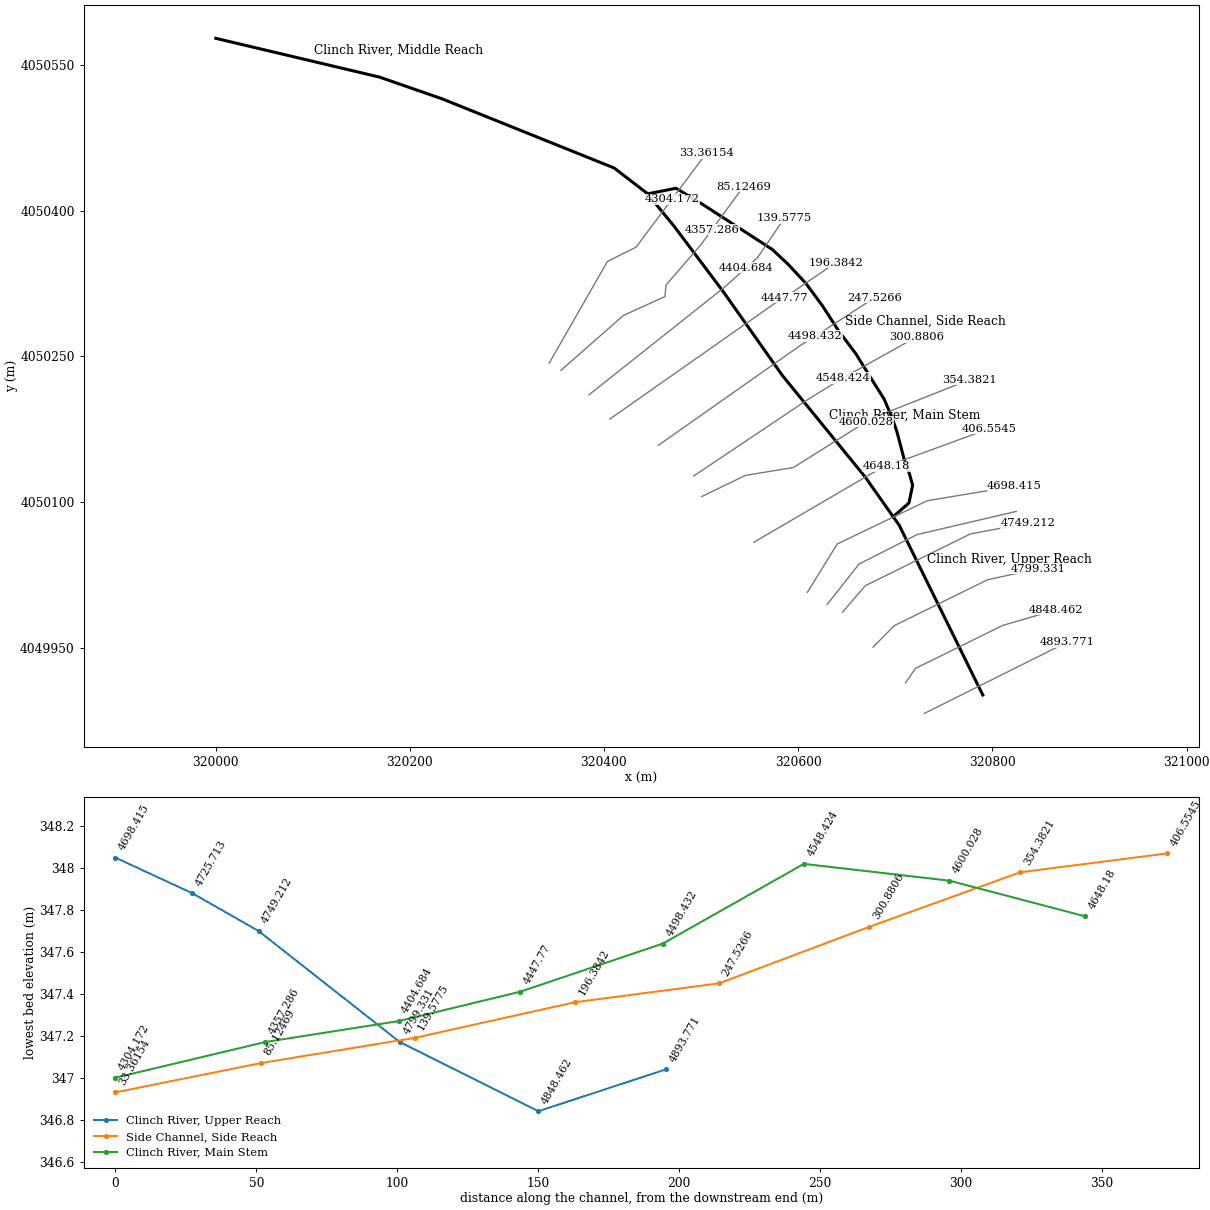
--- WBmod1D.prj (project) ---

Proj Title=WBmod1D
Current Plan=p01
Current Flow=f01
Default Exp/Contr=0.3,0.1
SI Units
Geom File=g01
Geom File=g02
Geom File=g03
Geom File=g04
Geom File=g05
Geom File=g06
Geom File=g07
Geom File=g08
Geom File=g09
Flow File=f01
Flow File=f02
Flow File=f03
Flow File=f04
Flow File=f05
Flow File=f06
Flow File=f07
Flow File=f08
Flow File=f09
Plan File=p01
Plan File=p02
Plan File=p03
Plan File=p04
Plan File=p05
Plan File=p06
Plan File=p07
Plan File=p08
Plan File=p09
Y Axis Title=Elevation
X Axis Title(PF)=Main Channel Distance
X Axis Title(XS)=Station
BEGIN DESCRIPTION:
END DESCRIPTION:
DSS Export Rating Curves= 0
DSS Export Rating Curve Sorted= 0
DSS Export Volume Flow Curves= 0
DXF OffsetX= 0
DXF OffsetY= 0
DXF ScaleX= 1
DXF ScaleY= 10

--- WBmod1D.p01 (plan) ---

Plan Title=planSIM20190924
Program Version=5.07
Short Identifier=pSIM20190924
Geom File=g03
Flow File=f01
Subcritical Flow
K Sum by GR= 0
Std Step Tol= 0.003
Critical Tol= 0.003
Num of Std Step Trials= 20
Max Error Tol= 0.1
Flow Tol Ratio= 0.001
Split Flow NTrial= 30
Split Flow Tol= 0.006
Split Flow Ratio= 0.02
Log Output Level= 3
Friction Slope Method= 1
Unsteady Friction Slope Method= 2
Unsteady Bridges Friction Slope Method= 1
Parabolic Critical Depth
Global Vel Dist= 0 , 0 , 0
Global Log Level= 3
CheckData=True
Encroach Param=-1 ,0,0, 0
Optimized Junction=2
Computation Interval=1MIN
Output Interval=1HOUR
Instantaneous Interval=1HOUR
Mapping Interval=1HOUR
Computation Time Step Use Courant=        0
Computation Time Step Use Time Series=    0
Computation Time Step Count To Double=0
Computation Time Step Max Doubling=0
Computation Time Step Max Halving=0
Computation Time Step Residence Courant=0
Run HTab= 0
Run UNet= 0
Run Sediment= 0
Run PostProcess= 0
Run WQNet= 0
Run RASMapper= 0
UNET Theta= 1
UNET Theta Warmup= 1
UNET ZTol= 0.006
UNET ZSATol= 0.006
UNET MxIter= 20
UNET Max Iter WO Improvement= 0
UNET MaxInSteps= 0
UNET DtIC= 0
UNET DtMin= 0
UNET MaxCRTS= 20
UNET WFStab= 2
UNET SFStab= 1
UNET WFX= 1
UNET SFX= 1
UNET 1D Methodology=Finite Difference
UNET DSS MLevel= 4
UNET Pardiso=0
UNET DZMax Abort= 30
UNET Use Existing IB Tables=-1
UNET Froude Reduction=False
UNET Froude Limit= 0.8
UNET Froude Power= 4
UNET D1 Cores= 0
UNET D2 Coriolis=0
UNET D2 Cores= 0
UNET D2 Theta= 1
UNET D2 Theta Warmup= 1
UNET D2 Z Tol= 0.003
UNET D2 Volume Tol= 0.003
UNET D2 Max Iterations= 20
UNET D2 Equation= 0
UNET D2 RampUpFraction=0.1
UNET D2 TimeSlices= 1
UNET D2 BCVolumeCheck=0
UNET D1D2 MaxIter= 0
UNET D1D2 ZTol=0.003
UNET D1D2 QTol=0.1
UNET D1D2 MinQTol=0.03
Write IC File= 0
Write IC File at Fixed DateTime=0
Write IC File at Sim End=0
Echo Input=False
Echo Parameters=False
Echo Output=False
Write Detailed= 0
HDF Write Warmup=0
HDF Write Time Slices=0
HDF Flush=0
HDF Face Node Velocities=0
HDF Compression= 1
HDF Chunk Size= 1
HDF Spatial Parts= 1
HDF Use Max Rows=0
HDF Fixed Rows= 1
Calibration Method= 0
Calibration Iterations= 20
Calibration Max Change=0.05
Calibration Tolerance=0.2
Calibration Maximum=1.5
Calibration Minimum=0.5
Calibration Optimization Method= 1
WQ AD Non Conservative
WQ ULTIMATE=-1
WQ Max Comp Step=1HOUR
WQ Output Interval=15MIN
WQ Output Selected Increments= 0
WQ Output face flow=0
WQ Output face velocity=0
WQ Output face area=0
WQ Output face dispersion=0
WQ Output cell volume=0
WQ Output cell surface area=0
WQ Output cell continuity=0
WQ Output cumulative cell continuity=0
WQ Output face conc=0
WQ Output face dconc_dx=0
WQ Output face courant=0
WQ Output face peclet=0
WQ Output face adv mass=0
WQ Output face disp mass=0
WQ Output cell mass=0
WQ Output cell source sink temp=0
WQ Output nsm pathways=0
WQ Output nsm derived pathways=0
WQ Output MaxMinRange=-1
WQ Daily Max Min Mean=-1
WQ Daily Range=0
WQ Daily Time=0
WQ Create Restart=0
WQ Fixed Restart=0
WQ System Summary=0
WQ Write To DSS=0
WQ Use Fixed Temperature=0
Sorting and Armoring Iterations= 10
XS Update Threshold= 0.02
Bed Roughness Predictor= 0
Hydraulics Update Threshold= 0.02
Energy Slope Method= 1
Volume Change Method= 1
Sediment Retention Method= 0
XS Weighting Method= 0
Number of US Weighted Cross Sections= 1
Number of DS Weighted Cross Sections= 1
Upstream XS Weight=0
Main XS Weight=1
Downstream XS Weight=0
Number of DS XS's Weighted with US Boundary= 1
Upstream Boundary Weight= 1
Weight of XSs Associated with US Boundary= 0
Number of US XS's Weighted with DS Boundary= 1
Downstream Boundary Weight= 0.5
Weight of XSs Associated with DS Boundary= 0.5
Percentile Method= 0
Sediment Output Level= 3
Mass or Volume Output= 0
Output Increment Type= 1
Profile and TS Output Increment= 1
XS Output Flag= 0
XS Output Increment= 10
Write Gradation File= 0
Read Gradation Hotstart= 0
Write HDF5 File= 1
Write Binary Output= 1
Write DSS Sediment File= 0
SV Curve= 0
Specific Gage Flag= 0

--- WBmod1D.p02 (plan) ---

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Plan Title=planSIM20190925
Short Identifier=pSIM20190925
Geom File=g03
Flow File=f02

--- WBmod1D.p03 (plan) ---

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Plan Title=planSIM20200825
Short Identifier=pSIM20200825
Geom File=g03
Flow File=f03

--- WBmod1D.p04 (plan) ---

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Plan Title=planSIM20200914
Short Identifier=pSIM20200914
Geom File=g03
Flow File=f04

--- WBmod1D.p05 (plan) ---

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Plan Title=planSIM20210513
Short Identifier=pSIM20210513
Geom File=g03
Flow File=f05

--- WBmod1D.p06 (plan) ---

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Plan Title=planSIM20210601
Short Identifier=pSIM20210601
Geom File=g03
Flow File=f06

--- WBmod1D.p07 (plan) ---

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Plan Title=planSIM20210810
Short Identifier=pSIM20210810
Geom File=g03
Flow File=f07

--- WBmod1D.p08 (plan) ---

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Plan Title=planSIM20210908
Short Identifier=pSIM20210908
Geom File=g03
Flow File=f08

--- WBmod1D.p09 (plan) ---

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Plan Title=planSIM20211215
Short Identifier=pSIM20211215
Geom File=g03
Flow File=f09

--- WBmod1D.f01 (steady flow) ---

Flow Title=steadySIM20190924
Program Version=5.07
Number of Profiles= 1
Profile Names=20190924
River Rch & RM=Clinch River,Upper Reach     ,4893.771
  3.49
River Rch & RM=Clinch River,Main Stem       ,4648.18
  2.62
River Rch & RM=Clinch River,Middle Reach    ,4279.376
  3.49
River Rch & RM=Clinch River,Lower Reach     ,3803.314
  3.69
River Rch & RM=North Fork,Tributary       ,98.29333
    0.2
River Rch & RM=Side Channel,Side Reach      ,406.5545
   0.87
Boundary for River Rch & Prof#=Clinch River,Upper Reach     , 1
Up Type= 1
Up Known WS=348.752
Dn Type= 0
Boundary for River Rch & Prof#=Clinch River,Main Stem       , 1
Up Type= 0
Dn Type= 0
Boundary for River Rch & Prof#=Clinch River,Middle Reach    , 1
Up Type= 0
Dn Type= 0
Boundary for River Rch & Prof#=Clinch River,Lower Reach     , 1
Up Type= 0
Dn Type= 3
Dn Slope=0.0002
Boundary for River Rch & Prof#=North Fork,Tributary       , 1
Up Type= 1
Up Known WS=346.981
Dn Type= 0
Boundary for River Rch & Prof#=Side Channel,Side Reach      , 1
Up Type= 0
Dn Type= 0
DSS Import GetInterval= 0
DSS Import GetPeak= 0
DSS Import FillOption= 0

--- WBmod1D.f02 (steady flow) ---

Flow Title=steadySIM20190925
Program Version=5.07
Number of Profiles= 1
Profile Names=20190925
River Rch & RM=Clinch River,Upper Reach     ,4893.771
  3.45
River Rch & RM=Clinch River,Main Stem       ,4648.18
  2.58
River Rch & RM=Clinch River,Middle Reach    ,4279.376
  3.45
River Rch & RM=Clinch River,Lower Reach     ,3803.314
  3.65
River Rch & RM=North Fork,Tributary       ,98.29333
    0.2
River Rch & RM=Side Channel,Side Reach      ,406.5545
   0.86
Boundary for River Rch & Prof#=Clinch River,Upper Reach     , 1
Up Type= 1
Up Known WS=348.751
Dn Type= 0
Boundary for River Rch & Prof#=Clinch River,Main Stem       , 1
Up Type= 0
Dn Type= 0
Boundary for River Rch & Prof#=Clinch River,Middle Reach    , 1
Up Type= 0
Dn Type= 0
Boundary for River Rch & Prof#=Clinch River,Lower Reach     , 1
Up Type= 0
Dn Type= 3
Dn Slope=0.0002
Boundary for River Rch & Prof#=North Fork,Tributary       , 1
Up Type= 1
Up Known WS=346.98
Dn Type= 0
Boundary for River Rch & Prof#=Side Channel,Side Reach      , 1
Up Type= 0
Dn Type= 0
DSS Import GetInterval= 0
DSS Import GetPeak= 0
DSS Import FillOption= 0

--- WBmod1D.f03 (steady flow) ---

Flow Title=steadySIM20200825
Program Version=5.07
Number of Profiles= 1
Profile Names=20200825
River Rch & RM=Clinch River,Upper Reach     ,4893.771
  20.56
River Rch & RM=Clinch River,Main Stem       ,4648.18
  15.42
River Rch & RM=Clinch River,Middle Reach    ,4279.376
  20.56
River Rch & RM=Clinch River,Lower Reach     ,3803.314
  21.76
River Rch & RM=North Fork,Tributary       ,98.29333
    1.2
River Rch & RM=Side Channel,Side Reach      ,406.5545
   5.14
Boundary for River Rch & Prof#=Clinch River,Upper Reach     , 1
Up Type= 1
Up Known WS=348.913
Dn Type= 0
Boundary for River Rch & Prof#=Clinch River,Main Stem       , 1
Up Type= 0
Dn Type= 0
Boundary for River Rch & Prof#=Clinch River,Middle Reach    , 1
Up Type= 0
Dn Type= 0
Boundary for River Rch & Prof#=Clinch River,Lower Reach     , 1
Up Type= 0
Dn Type= 3
Dn Slope=0.0002
Boundary for River Rch & Prof#=North Fork,Tributary       , 1
Up Type= 1
Up Known WS=347.219
Dn Type= 0
Boundary for River Rch & Prof#=Side Channel,Side Reach      , 1
Up Type= 0
Dn Type= 0
DSS Import GetInterval= 0
DSS Import GetPeak= 0
DSS Import FillOption= 0

--- WBmod1D.f04 (steady flow) ---

Flow Title=steadySIM20200914
Program Version=5.07
Number of Profiles= 1
Profile Names=20200914
River Rch & RM=Clinch River,Upper Reach     ,4893.771
  15.5
River Rch & RM=Clinch River,Main Stem       ,4648.18
  11.63
River Rch & RM=Clinch River,Middle Reach    ,4279.376
  15.5
River Rch & RM=Clinch River,Lower Reach     ,3803.314
  16.41
River Rch & RM=North Fork,Tributary       ,98.29333
    0.9
River Rch & RM=Side Channel,Side Reach      ,406.5545
   3.88
Boundary for River Rch & Prof#=Clinch River,Upper Reach     , 1
Up Type= 1
Up Known WS=348.865
Dn Type= 0
Boundary for River Rch & Prof#=Clinch River,Main Stem       , 1
Up Type= 0
Dn Type= 0
Boundary for River Rch & Prof#=Clinch River,Middle Reach    , 1
Up Type= 0
Dn Type= 0
Boundary for River Rch & Prof#=Clinch River,Lower Reach     , 1
Up Type= 0
Dn Type= 3
Dn Slope=0.0002
Boundary for River Rch & Prof#=North Fork,Tributary       , 1
Up Type= 1
Up Known WS=347.148
Dn Type= 0
Boundary for River Rch & Prof#=Side Channel,Side Reach      , 1
Up Type= 0
Dn Type= 0
DSS Import GetInterval= 0
DSS Import GetPeak= 0
DSS Import FillOption= 0

--- WBmod1D.f05 (steady flow) ---

Flow Title=steadySIM20210513
Program Version=5.07
Number of Profiles= 1
Profile Names=20210513
River Rch & RM=Clinch River,Upper Reach     ,4893.771
  28.01
River Rch & RM=Clinch River,Main Stem       ,4648.18
  21.01
River Rch & RM=Clinch River,Middle Reach    ,4279.376
  28.01
River Rch & RM=Clinch River,Lower Reach     ,3803.314
  29.64
River Rch & RM=North Fork,Tributary       ,98.29333
    1.63
River Rch & RM=Side Channel,Side Reach      ,406.5545
   7.0
Boundary for River Rch & Prof#=Clinch River,Upper Reach     , 1
Up Type= 1
Up Known WS=348.983
Dn Type= 0
Boundary for River Rch & Prof#=Clinch River,Main Stem       , 1
Up Type= 0
Dn Type= 0
Boundary for River Rch & Prof#=Clinch River,Middle Reach    , 1
Up Type= 0
Dn Type= 0
Boundary for River Rch & Prof#=Clinch River,Lower Reach     , 1
Up Type= 0
Dn Type= 3
Dn Slope=0.0002
Boundary for River Rch & Prof#=North Fork,Tributary       , 1
Up Type= 1
Up Known WS=347.323
Dn Type= 0
Boundary for River Rch & Prof#=Side Channel,Side Reach      , 1
Up Type= 0
Dn Type= 0
DSS Import GetInterval= 0
DSS Import GetPeak= 0
DSS Import FillOption= 0

--- WBmod1D.f06 (steady flow) ---

Flow Title=steadySIM20210601
Program Version=5.07
Number of Profiles= 1
Profile Names=20210601
River Rch & RM=Clinch River,Upper Reach     ,4893.771
  14.81
River Rch & RM=Clinch River,Main Stem       ,4648.18
  11.11
River Rch & RM=Clinch River,Middle Reach    ,4279.376
  14.81
River Rch & RM=Clinch River,Lower Reach     ,3803.314
  15.67
River Rch & RM=North Fork,Tributary       ,98.29333
    0.86
River Rch & RM=Side Channel,Side Reach      ,406.5545
   3.7
Boundary for River Rch & Prof#=Clinch River,Upper Reach     , 1
Up Type= 1
Up Known WS=348.859
Dn Type= 0
Boundary for River Rch & Prof#=Clinch River,Main Stem       , 1
Up Type= 0
Dn Type= 0
Boundary for River Rch & Prof#=Clinch River,Middle Reach    , 1
Up Type= 0
Dn Type= 0
Boundary for River Rch & Prof#=Clinch River,Lower Reach     , 1
Up Type= 0
Dn Type= 3
Dn Slope=0.0002
Boundary for River Rch & Prof#=North Fork,Tributary       , 1
Up Type= 1
Up Known WS=347.139
Dn Type= 0
Boundary for River Rch & Prof#=Side Channel,Side Reach      , 1
Up Type= 0
Dn Type= 0
DSS Import GetInterval= 0
DSS Import GetPeak= 0
DSS Import FillOption= 0

--- WBmod1D.f07 (steady flow) ---

Flow Title=steadySIM20210810
Program Version=5.07
Number of Profiles= 1
Profile Names=20210810
River Rch & RM=Clinch River,Upper Reach     ,4893.771
  6.91
River Rch & RM=Clinch River,Main Stem       ,4648.18
  5.18
River Rch & RM=Clinch River,Middle Reach    ,4279.376
  6.91
River Rch & RM=Clinch River,Lower Reach     ,3803.314
  7.31
River Rch & RM=North Fork,Tributary       ,98.29333
    0.4
River Rch & RM=Side Channel,Side Reach      ,406.5545
   1.73
Boundary for River Rch & Prof#=Clinch River,Upper Reach     , 1
Up Type= 1
Up Known WS=348.784
Dn Type= 0
Boundary for River Rch & Prof#=Clinch River,Main Stem       , 1
Up Type= 0
Dn Type= 0
Boundary for River Rch & Prof#=Clinch River,Middle Reach    , 1
Up Type= 0
Dn Type= 0
Boundary for River Rch & Prof#=Clinch River,Lower Reach     , 1
Up Type= 0
Dn Type= 3
Dn Slope=0.0002
Boundary for River Rch & Prof#=North Fork,Tributary       , 1
Up Type= 1
Up Known WS=347.028
Dn Type= 0
Boundary for River Rch & Prof#=Side Channel,Side Reach      , 1
Up Type= 0
Dn Type= 0
DSS Import GetInterval= 0
DSS Import GetPeak= 0
DSS Import FillOption= 0

--- WBmod1D.f08 (steady flow) ---

Flow Title=steadySIM20210908
Program Version=5.07
Number of Profiles= 1
Profile Names=20210908
River Rch & RM=Clinch River,Upper Reach     ,4893.771
  14.32
River Rch & RM=Clinch River,Main Stem       ,4648.18
  10.74
River Rch & RM=Clinch River,Middle Reach    ,4279.376
  14.32
River Rch & RM=Clinch River,Lower Reach     ,3803.314
  15.16
River Rch & RM=North Fork,Tributary       ,98.29333
    0.83
River Rch & RM=Side Channel,Side Reach      ,406.5545
   3.58
Boundary for River Rch & Prof#=Clinch River,Upper Reach     , 1
Up Type= 1
Up Known WS=348.854
Dn Type= 0
Boundary for River Rch & Prof#=Clinch River,Main Stem       , 1
Up Type= 0
Dn Type= 0
Boundary for River Rch & Prof#=Clinch River,Middle Reach    , 1
Up Type= 0
Dn Type= 0
Boundary for River Rch & Prof#=Clinch River,Lower Reach     , 1
Up Type= 0
Dn Type= 3
Dn Slope=0.0002
Boundary for River Rch & Prof#=North Fork,Tributary       , 1
Up Type= 1
Up Known WS=347.132
Dn Type= 0
Boundary for River Rch & Prof#=Side Channel,Side Reach      , 1
Up Type= 0
Dn Type= 0
DSS Import GetInterval= 0
DSS Import GetPeak= 0
DSS Import FillOption= 0

--- WBmod1D.f09 (steady flow) ---

Flow Title=steadySIM20211215
Program Version=5.07
Number of Profiles= 1
Profile Names=20211215
River Rch & RM=Clinch River,Upper Reach     ,4893.771
  18.7
River Rch & RM=Clinch River,Main Stem       ,4648.18
  14.03
River Rch & RM=Clinch River,Middle Reach    ,4279.376
  18.7
River Rch & RM=Clinch River,Lower Reach     ,3803.314
  19.79
River Rch & RM=North Fork,Tributary       ,98.29333
    1.09
River Rch & RM=Side Channel,Side Reach      ,406.5545
   4.68
Boundary for River Rch & Prof#=Clinch River,Upper Reach     , 1
Up Type= 1
Up Known WS=348.895
Dn Type= 0
Boundary for River Rch & Prof#=Clinch River,Main Stem       , 1
Up Type= 0
Dn Type= 0
Boundary for River Rch & Prof#=Clinch River,Middle Reach    , 1
Up Type= 0
Dn Type= 0
Boundary for River Rch & Prof#=Clinch River,Lower Reach     , 1
Up Type= 0
Dn Type= 3
Dn Slope=0.0002
Boundary for River Rch & Prof#=North Fork,Tributary       , 1
Up Type= 1
Up Known WS=347.193
Dn Type= 0
Boundary for River Rch & Prof#=Side Channel,Side Reach      , 1
Up Type= 0
Dn Type= 0
DSS Import GetInterval= 0
DSS Import GetPeak= 0
DSS Import FillOption= 0

--- WBmod1D.g03 (geometry) ---

Geom Title=WBgeom1D
Program Version=5.07

Junct Name=2
Junct Desc=, 0 , 0 ,-1 ,0
Up River,Reach=Clinch River    ,Upper Reach
Dn River,Reach=Clinch River    ,Main Stem
Dn River,Reach=Side Channel    ,Side Reach
Junc L&A=50,
Junc L&A=49,

Junct Name=3
Junct Desc=, 0 , 0 ,-1 ,0
Up River,Reach=Clinch River    ,Main Stem
Up River,Reach=Side Channel    ,Side Reach
Dn River,Reach=Clinch River    ,Middle Reach
Junc L&A=25,
Junc L&A=23,0

Junct Name=4
Junct Desc=, 0 , 0 ,-1 ,0
Up River,Reach=Clinch River    ,Middle Reach
Up River,Reach=North Fork      ,Tributary
Dn River,Reach=Clinch River    ,Lower Reach
Junc L&A=66.5,
Junc L&A=46,0

River Reach=Clinch River    ,Upper Reach
Reach XY= 30
     320790.1431    4049901.3955     320786.5132    4049908.6763
     320771.6967     4049938.775     320765.5959    4049951.1685
     320763.8527    4049954.7095     320762.9812    4049956.4801
     320757.7519    4049967.1031     320756.0087    4049970.6441
      320751.651    4049979.4967     320749.9078    4049983.0377
     320744.6785    4049993.6607      320743.807    4049995.4313
     320742.0638    4049998.9723     320729.8621    4050023.7594
     320728.1189    4050027.3004     320726.3758    4050030.8414
     320725.5043     4050032.612     320718.5288    4050046.7821
     320715.9913    4050051.9371     320714.2995    4050055.3737
     320713.4537    4050057.0921     320711.7619    4050060.5287
     320710.0702    4050063.9653     320709.2244    4050065.6837
     320707.5326    4050069.1203     320704.9951    4050074.2753
     320704.1492    4050075.9936     320702.0404    4050078.9859
     320700.9861    4050080.4821     320697.8229    4050084.9706

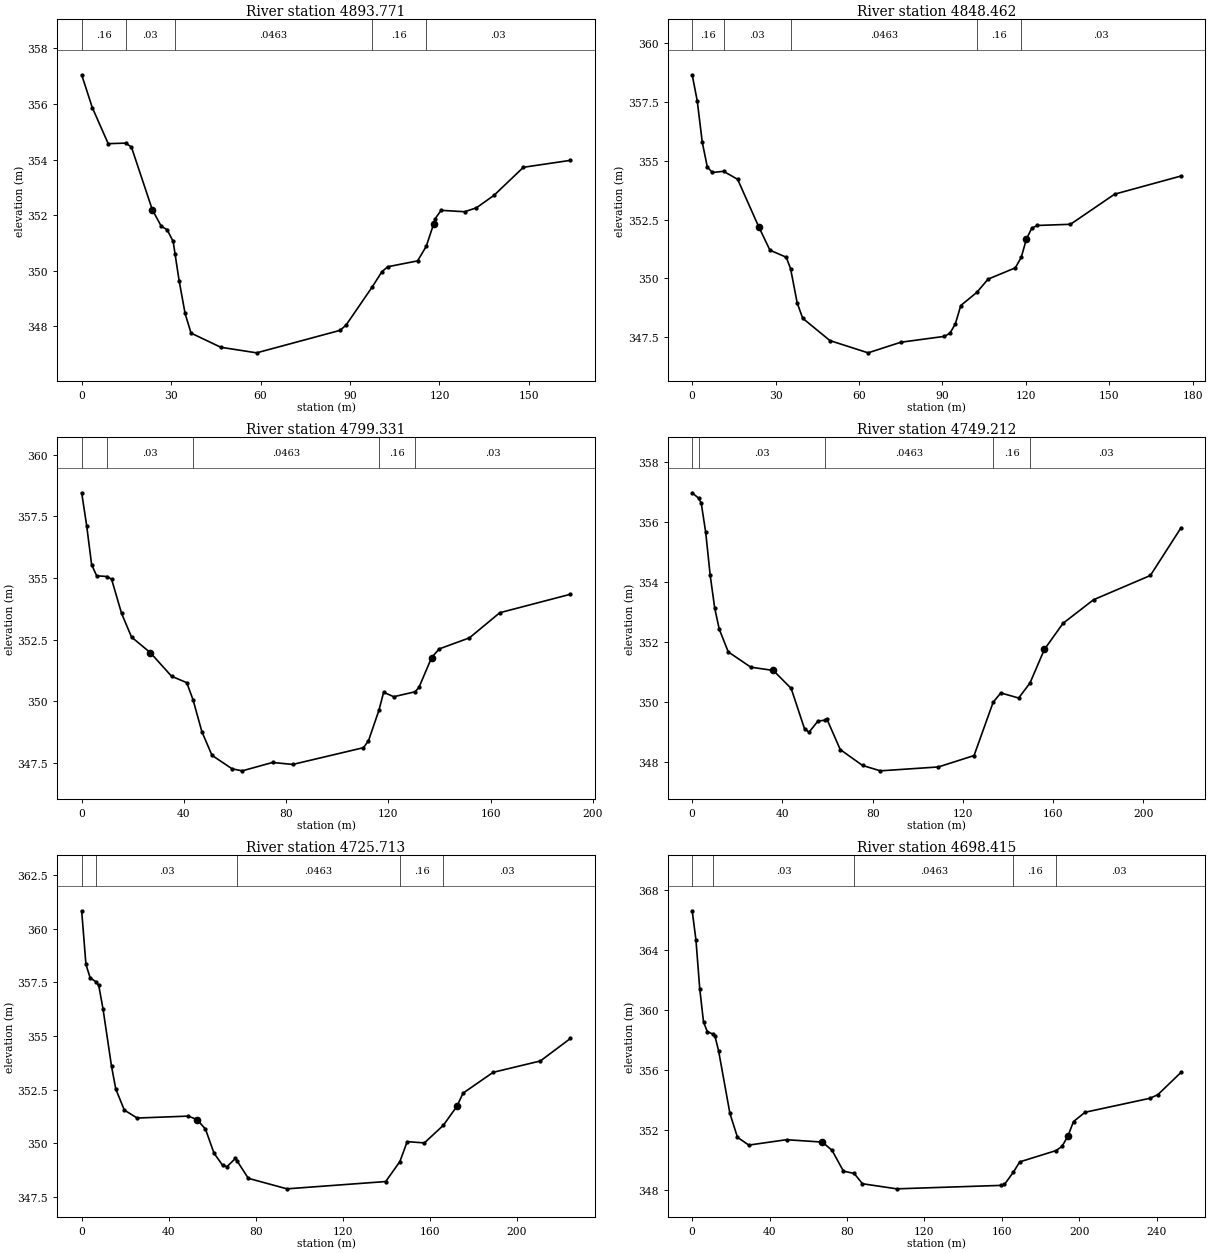
Type RM Length L Ch R = 1 ,4893.771,44.6,45.31,43.51
XS GIS Cut Line= 4
     320729.9764    4049882.4458     320739.5355    4049887.2116
     320829.0295    4049931.8302     320876.6807    4049955.5874
#Sta/Elev= 30
       0  357.05    3.56  355.87     8.9  354.57   14.74  354.59   16.68  354.45
    23.7  352.19   26.68   351.6   28.68  351.47   30.68  351.05   31.32   350.6
   32.68  349.64   34.68  348.46   36.68  347.75   46.68  347.24   58.68  347.04
   86.68  347.85   88.68  348.04   97.43  349.41  100.68  349.96  102.68  350.14
  112.65  350.35  115.54  350.87  118.05  351.68  118.57  351.87  120.54  352.17
  128.43  352.12  132.37  352.26  138.29  352.71  148.15  353.72  163.93  353.97
#Mann= 5 ,-1 , 0
       0     .16       0   14.74     .03       0   31.32   .0463       0
   97.43     .16       0  115.54     .03       0
Bank Sta=23.7,118.05
XS Rating Curve= 0 ,0
Exp/Cntr=0.3,0.1

Type RM Length L Ch R = 1 ,4848.462,47.67,49.13,49.02
XS GIS Cut Line= 4
      320710.478    4049913.9269     320720.8694     4049928.816
     320810.5881    4049972.9812     320865.8832    4049989.1218
#Sta/Elev= 30
       0  358.65    1.82  357.54    3.63  355.78    5.45  354.73    7.26   354.5
   11.28  354.55   16.34  354.21   23.91   352.2   27.96   351.2   33.84   350.9
   35.39  350.41   37.76  348.96   39.73  348.31   49.53  347.36   63.25  346.84
   75.02  347.29   90.71  347.54   92.67  347.67   94.63  348.07   96.59  348.85
  102.37  349.41  106.39  349.97   116.2  350.45  118.33   350.9  120.18  351.67
  122.13  352.14  124.12  352.25  136.03   352.3  151.92  353.58  175.76  354.35
#Mann= 5 ,-1 , 0
       0     .16       0   11.28     .03       0   35.39   .0463       0
  102.37     .16       0  118.33     .03       0
Bank Sta=23.91,120.18
XS Rating Curve= 0 ,0
Exp/Cntr=0.3,0.1

Type RM Length L Ch R = 1 ,4799.331,50.26,50.12,50.04
XS GIS Cut Line= 4
     320677.1605    4049950.7305     320699.1708    4049972.8953
     320794.8941    4050020.0163     320847.0184    4050031.4049
#Sta/Elev= 30
       0  358.46    1.95  357.13     3.9  355.54    5.86  355.09     9.9  355.06
   11.71  354.95   15.62  353.56   19.52   352.6   26.85  351.97   35.19  351.01
   41.12  350.75   43.57  350.06   47.04  348.76   50.99   347.8    58.9  347.25
   62.85  347.17    74.7  347.51   82.61  347.43  110.27  348.11  112.24  348.39
  116.36  349.64  118.17  350.36  122.12  350.18  130.48  350.38     132  350.56
  136.95  351.77  139.91  352.12  151.76  352.57  163.62  353.59  191.28  354.34
#Mann= 5 ,-1 , 0
       0     .16       0     9.9     .03       0   43.57   .0463       0
  116.36     .16       0  130.48     .03       0
Bank Sta=26.85,136.95
XS Rating Curve= 0 ,0
Exp/Cntr=0.3,0.1

Type RM Length L Ch R = 1 ,4749.212,19.57,23.5,12.37
XS GIS Cut Line= 4
     320645.7347    4049986.7913     320669.2309    4050014.0194
      320777.424    4050067.2789      320836.478    4050078.3248
#Sta/Elev= 30
       0  356.98    2.82   356.8       4  356.64    5.99  355.66    7.99  354.22
    9.99  353.13   11.99  352.43   15.98  351.67   25.97  351.16   35.96  351.05
   43.87  350.45    49.8   349.1   51.78  348.99   55.73  349.36    58.7  349.39
   59.69  349.43   65.62  348.41    75.5  347.88   83.41   347.7  109.11  347.83
  124.93  348.21  133.39  349.99  136.79   350.3  144.69  350.13  149.71  350.63
  156.08  351.75  164.31  352.62  177.87  353.41  203.07  354.22  216.63  355.81
#Mann= 5 ,-1 , 0
       0     .16       0    2.82     .03       0    58.7   .0463       0
  133.39     .16       0  149.71     .03       0
Bank Sta=35.96,156.08
XS Rating Curve= 0 ,0
Exp/Cntr=0.3,0.1

Type RM Length L Ch R = 1 ,4725.713,31.14,27.3,29.3
XS GIS Cut Line= 4
     320629.8557    4049994.6365     320662.6549    4050036.2249
      320722.478    4050066.5906     320824.4461     4050090.426
#Sta/Elev= 30
       0  360.84    1.96  358.34    3.92  357.71    6.58  357.53    7.85  357.36
    9.81  356.27   13.73  353.59   15.69  352.53   19.62  351.55    25.5  351.18
   49.04  351.27   52.97  351.11   56.91  350.67   60.86  349.54   64.81  348.98
   66.78  348.91   70.72   349.3   71.54  349.17   76.64  348.37    94.4  347.88
  139.81  348.22  146.32  349.15  149.69  350.08  157.59  350.02   166.3  350.84
  172.51  351.72  175.38  352.34  189.21  353.31  210.94  353.84  224.77  354.89
#Mann= 5 ,-1 , 0
       0     .16       0    6.58     .03       0   71.54   .0463       0
  146.32     .16       0   166.3     .03       0
Bank Sta=52.97,172.51
XS Rating Curve= 0 ,0
Exp/Cntr=0.3,0.1

Type RM Length L Ch R = 1 ,4698.415,50.19,50.23,55.05
XS GIS Cut Line= 5
     320609.4483    4050007.0777     320640.1808    4050056.8439
      320712.838    4050091.7937     320732.8593    4050101.4244
      320822.844     4050116.414
#Sta/Elev= 30
       0  366.61    1.95  364.66     3.9  361.41    5.85  359.19     7.8  358.55
   10.98  358.36    11.7  358.28   13.65  357.26    19.5  353.08    23.4  351.49
   29.25  350.97   48.74  351.33   67.28  351.17   72.26  350.62   78.16  349.23
   83.67  349.08   87.99  348.39  105.69  348.05  159.48  348.28  161.33  348.34
  165.88  349.15  169.27  349.85  187.93   350.6  191.08  350.88  194.16  351.58
  197.03  352.54  202.98  353.16  236.69   354.1  240.66  354.34  252.56  355.82
#Mann= 5 ,-1 , 0
       0     .16       0   10.98     .03       0   83.67   .0463       0
  165.88     .16       0  187.93     .03       0
Bank Sta=67.28,194.16
XS Rating Curve= 0 ,0
Exp/Cntr=0.3,0.1

River Reach=Side Channel    ,Side Reach
Reach XY= 30
     320697.8229    4050084.9706     320702.2456    4050088.8197
     320709.6169    4050095.2347     320714.0396    4050099.0838
     320717.8575     4050117.342      320714.687    4050128.8044
      320709.284    4050143.6492     320701.5901    4050172.8576
     320696.4307     4050187.542     320688.4932    4050206.1952
       320676.19    4050225.6421     320659.5212    4050252.6297
     320657.2607    4050255.6427     320647.0882    4050269.2009
      320645.958    4050270.7074     320641.4369    4050276.7333
     320625.0327    4050302.1333     320607.7973    4050325.4892
     320589.0493    4050345.5251     320573.1743    4050360.3418
     320564.9963    4050365.6335      320561.725    4050367.7501
     320555.1826    4050371.9835     320550.2758    4050375.1584
     320548.6402    4050376.2168     320545.3689    4050378.3334
     320537.1909    4050383.6251      320502.795    4050405.8502
      320474.217    4050423.2455     320444.8197    4050417.4518

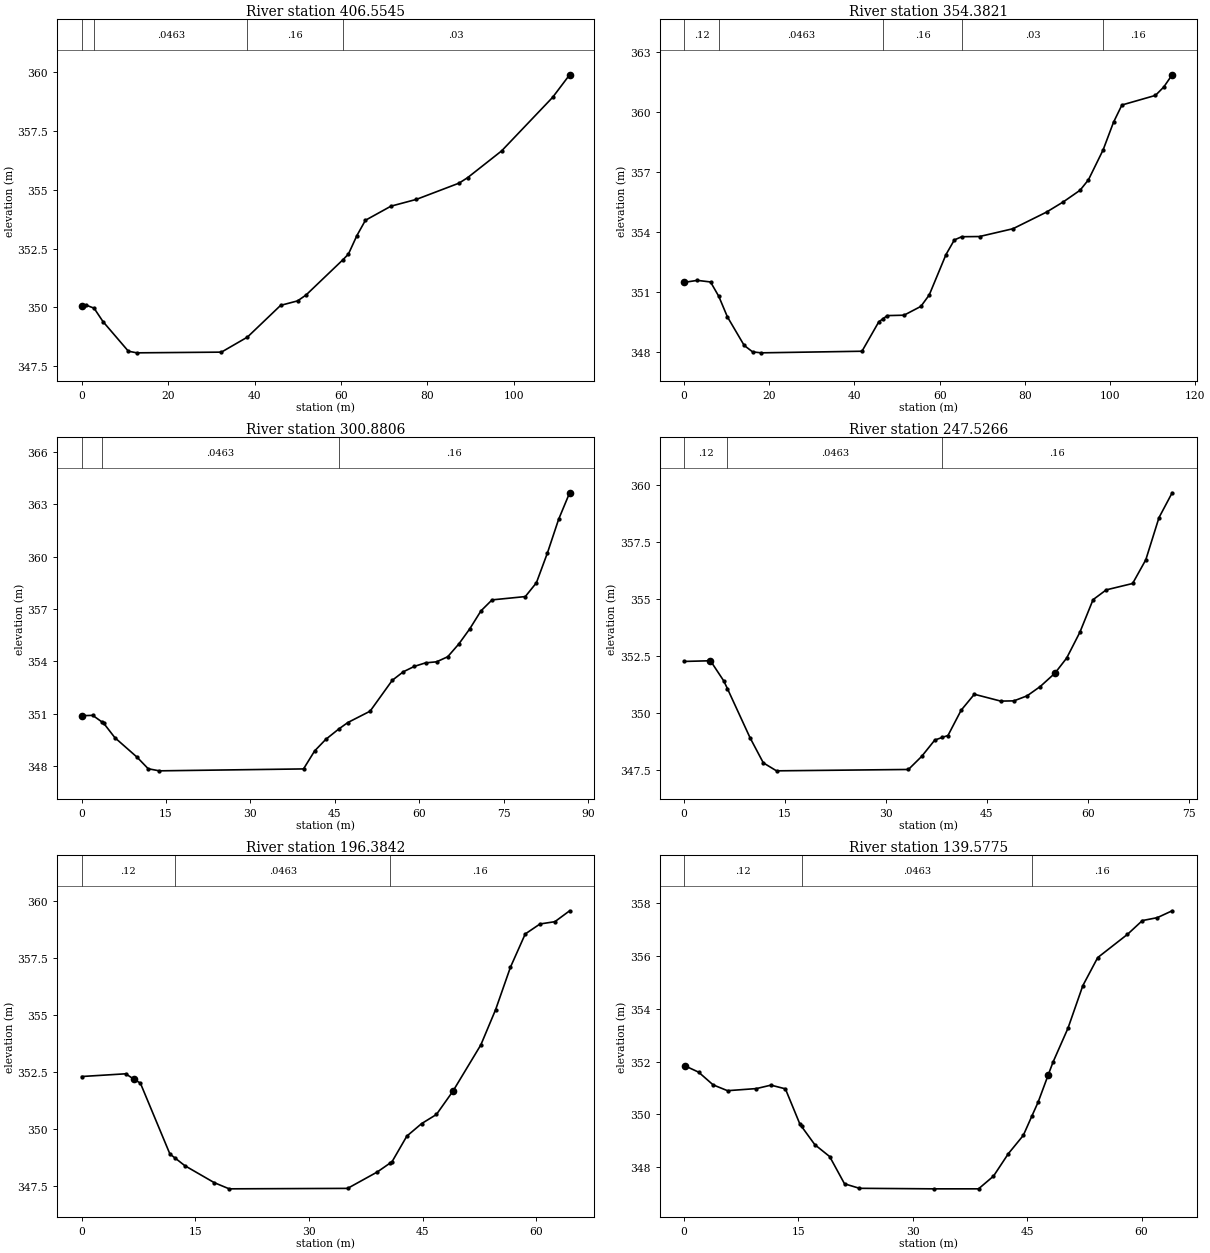
Type RM Length L Ch R = 1 ,406.5545,50.34,52.17,53.22
XS GIS Cut Line= 4
     320690.4575    4050136.7511     320691.4209    4050137.1041
     320744.7176    4050156.6323     320796.4729    4050175.5958
#Sta/Elev= 22
       0  350.08    1.03   350.1    2.88  349.97    4.94   349.4   10.81  348.14
   12.77  348.07   32.34   348.1   38.36  348.74   46.04  350.09   49.96  350.28
   51.92  350.53   60.45  352.03   61.72  352.27   63.69  353.06   65.66  353.71
   71.57  354.31   77.47   354.6   87.32  355.29   89.28  355.52   97.16  356.66
  108.97  358.94  112.91   359.9
#Mann= 4 ,-1 , 0
       0     .12       0    2.88   .0463       0   38.36     .16       0
   60.45     .03       0
Bank Sta=0,112.91
XS Rating Curve= 0 ,0
Exp/Cntr=0.3,0.1

Type RM Length L Ch R = 1 ,354.3821,51,53.5,59.55
XS GIS Cut Line= 4
     320669.8785    4050182.6929     320675.1223    4050185.9925
     320721.0462    4050204.1692     320775.9194    4050225.8882
#Sta/Elev= 30
       0   351.5     3.1   351.6     6.2  351.52    8.14   350.8   10.15  349.78
    14.1  348.35   16.07  348.03   18.05  347.98   41.76  348.06   45.71  349.53
   46.75  349.69   47.68  349.84   51.63  349.86   55.59   350.3   57.55  350.87
   61.49  352.89   63.45  353.62   65.18  353.78   69.36  353.79   77.22  354.18
   85.09  355.01   89.03  355.52   92.96   356.1   94.93  356.62   98.39  358.12
  100.83   359.5   102.8  360.36  110.67  360.84  112.63  361.26   114.6  361.87
#Mann= 5 ,-1 , 0
       0     .12       0    8.14   .0463       0   46.75     .16       0
   65.18     .03       0   98.39     .16       0
Bank Sta=0,114.6
XS Rating Curve= 0 ,0
Exp/Cntr=0.3,0.1

Type RM Length L Ch R = 1 ,300.8806,51.73,53.35,56.02
XS GIS Cut Line= 3
     320646.1206     4050227.881     320690.8836    4050252.8527
     320721.8501    4050270.1278
#Sta/Elev= 29
       0  350.88    1.97   350.9    3.58  350.53    3.94  350.44    5.91  349.62
    9.86   348.5   11.83  347.84    13.8  347.72   39.43  347.83    41.4  348.86
   43.37  349.52    45.7  350.12   47.31  350.49   51.26  351.14    55.2  352.91
   57.17   353.4   59.14  353.71   61.11  353.91   63.08  353.97   65.05  354.26
   67.02  354.99   68.99  355.87   70.96  356.89   72.93  357.52   78.84  357.71
   80.81   358.5   82.78  360.22   84.75  362.13   86.72  363.66
#Mann= 3 ,-1 , 0
       0     .12       0    3.58   .0463       0    45.7     .16       0
Bank Sta=0,86.72
XS Rating Curve= 0 ,0
Exp/Cntr=0.3,0.1

Type RM Length L Ch R = 1 ,247.5266,50.9,51.14,53.63
XS GIS Cut Line= 2
      320617.721    4050271.0724      320678.652    4050310.4615
#Sta/Elev= 27
       0  352.25    3.91  352.28    5.88   351.4    6.43  351.06     9.8   348.9
   11.77   347.8   13.73  347.45   33.34  347.51    35.3  348.08   37.26   348.8
    38.4  348.92   39.22     349   41.18  350.11   43.14  350.81   47.06  350.51
   49.02  350.52   50.98  350.74   52.94  351.15   55.11  351.73   56.87   352.4
   58.83  353.53   60.79  354.96   62.75  355.39   66.67  355.67   68.63  356.71
   70.59  358.56   72.55  359.65
#Mann= 3 ,-1 , 0
       0     .12       0    6.43   .0463       0    38.4     .16       0
Bank Sta=3.91,55.11
XS Rating Curve= 0 ,0
Exp/Cntr=0.3,0.1

Type RM Length L Ch R = 1 ,196.3842,49.6,56.81,67.88
XS GIS Cut Line= 3
     320585.5492    4050310.7311     320592.1555    4050314.7802
     320638.8935    4050346.7788
#Sta/Elev= 24
       0   352.3    5.81  352.42    6.96  352.17    7.75  352.01   11.65  348.89
   12.35  348.71   13.61  348.38   17.51  347.63   19.47  347.36   35.09  347.38
      39   348.1   40.73   348.5   40.95  348.55   42.91  349.68   44.86  350.23
   46.81  350.63   48.98  351.65   52.67  353.69   54.62  355.24   56.58  357.11
   58.53  358.57   60.48  359.01   62.44  359.11   64.39  359.59
#Mann= 3 ,-1 , 0
       0     .12       0   12.35   .0463       0   40.73     .16       0
Bank Sta=6.96,48.98
XS Rating Curve= 0 ,0
Exp/Cntr=0.3,0.1

Type RM Length L Ch R = 1 ,139.5775,52.8,54.45,53.47
XS GIS Cut Line= 3
     320546.7671    4050341.6357     320558.0778    4050351.7635
     320585.5657    4050392.1313
#Sta/Elev= 30
       0  351.85      .1  351.84     1.9   351.6     3.8  351.12    5.69   350.9
    9.49  350.98   11.39  351.11   13.28  350.97   15.18  349.64    15.4  349.55
   17.14  348.86   19.09  348.41   21.04  347.38      23  347.21   32.76  347.19
   38.62  347.19   40.58  347.67   42.53  348.52   44.49  349.21    45.6  349.93
   46.44  350.47   47.74  351.48   48.39  351.98   50.35  353.26    52.3  354.87
   54.25  355.93   58.16  356.81   60.11  357.33   62.07  357.44   64.02   357.7
#Mann= 3 ,-1 , 0
       0     .12       0    15.4   .0463       0    45.6     .16       0
Bank Sta=0.1,47.74
XS Rating Curve= 0 ,0
Exp/Cntr=0.3,0.1

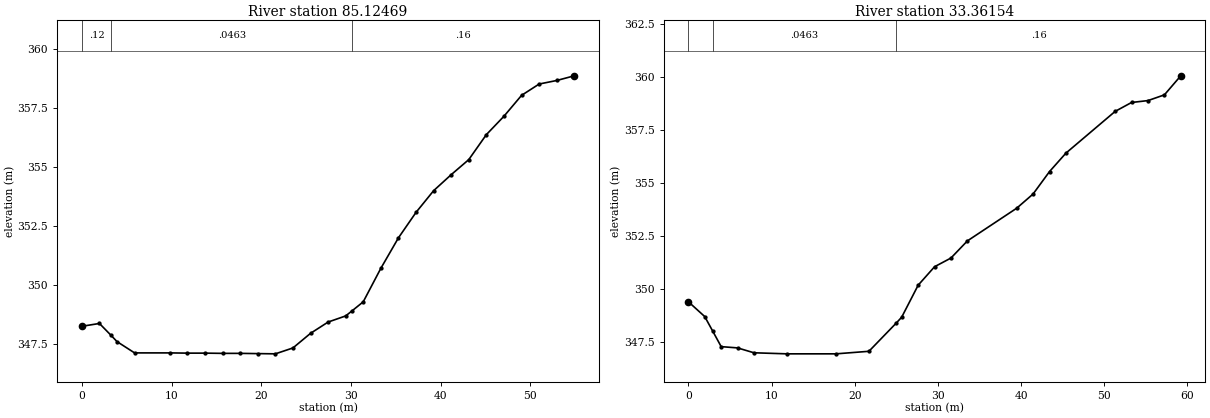
Type RM Length L Ch R = 1 ,85.12469,51.7,51.76,51.42
XS GIS Cut Line= 2
      320511.251    4050380.7478     320543.7404    4050425.0261
#Sta/Elev= 30
       0  348.24    1.96  348.36    3.27  347.85    3.92  347.59    5.88  347.11
    9.81  347.11   11.77   347.1   13.73   347.1   15.69  347.09   17.65  347.09
   19.61  347.08   21.58  347.07   23.54  347.32    25.5  347.94   27.46  348.42
   29.42  348.68   30.18  348.91   31.38  349.28   33.34   350.7   35.31     352
   37.27  353.08   39.23     354   41.19  354.68   43.15  355.32   45.11  356.38
   47.07  357.16   49.04  358.05      51  358.53   52.96  358.68   54.92  358.88
#Mann= 3 ,-1 , 0
       0     .12       0    3.27   .0463       0   30.18     .16       0
Bank Sta=0,54.92
XS Rating Curve= 0 ,0
Exp/Cntr=0.3,0.1

Type RM Length L Ch R = 1 ,33.36154,26.26,33.36,18.47
XS GIS Cut Line= 2
     320469.9539    4050411.9048     320505.4319    4050459.3002
#Sta/Elev= 24
       0  349.39    1.97  348.69    2.95  347.99    3.95  347.27    5.92  347.21
    7.89  346.98   11.84  346.93   17.76  346.93   21.71  347.05   24.99  348.38
   25.65  348.66   27.63  350.17    29.6  351.04   31.57  351.45   33.55  352.26
   39.47   353.8   41.44  354.47   43.42  355.53   45.39   356.4   51.31  358.37
   53.28  358.79   55.26  358.88   57.23  359.15    59.2  360.05
#Mann= 3 ,-1 , 0
       0     .12       0    2.95   .0463       0   24.99     .16       0
Bank Sta=0,59.2
XS Rating Curve= 0 ,0
Exp/Cntr=0.3,0.1

River Reach=Clinch River    ,Main Stem
Reach XY= 30
     320697.8229    4050084.9706     320694.4887    4050089.7018
     320693.3774    4050091.2789     320688.9318    4050097.5871
     320686.7091    4050100.7413     320680.0407    4050110.2036
      320677.818    4050113.3578     320673.3724     4050119.666
     320672.2611    4050121.2431     320668.9269    4050125.9743
     320663.9132    4050132.1191     320658.8994    4050138.2638
     320645.1117     4050155.162     320640.0979    4050161.3067
     320626.3102    4050178.2049     320625.0567     4050179.741
     320622.5498    4050182.8134     320612.5224     4050195.103
     320607.5086    4050201.2477     320593.7209    4050218.1459
     320588.7071    4050224.2906     320583.6934    4050230.4354
     320522.4418    4050317.3024       320511.83    4050331.4197
     320503.5763    4050342.3997     320490.6064    4050359.6542
     320482.3527    4050370.6342     320477.6364    4050376.9086
     320471.7409    4050384.7515     320444.8197    4050417.4518

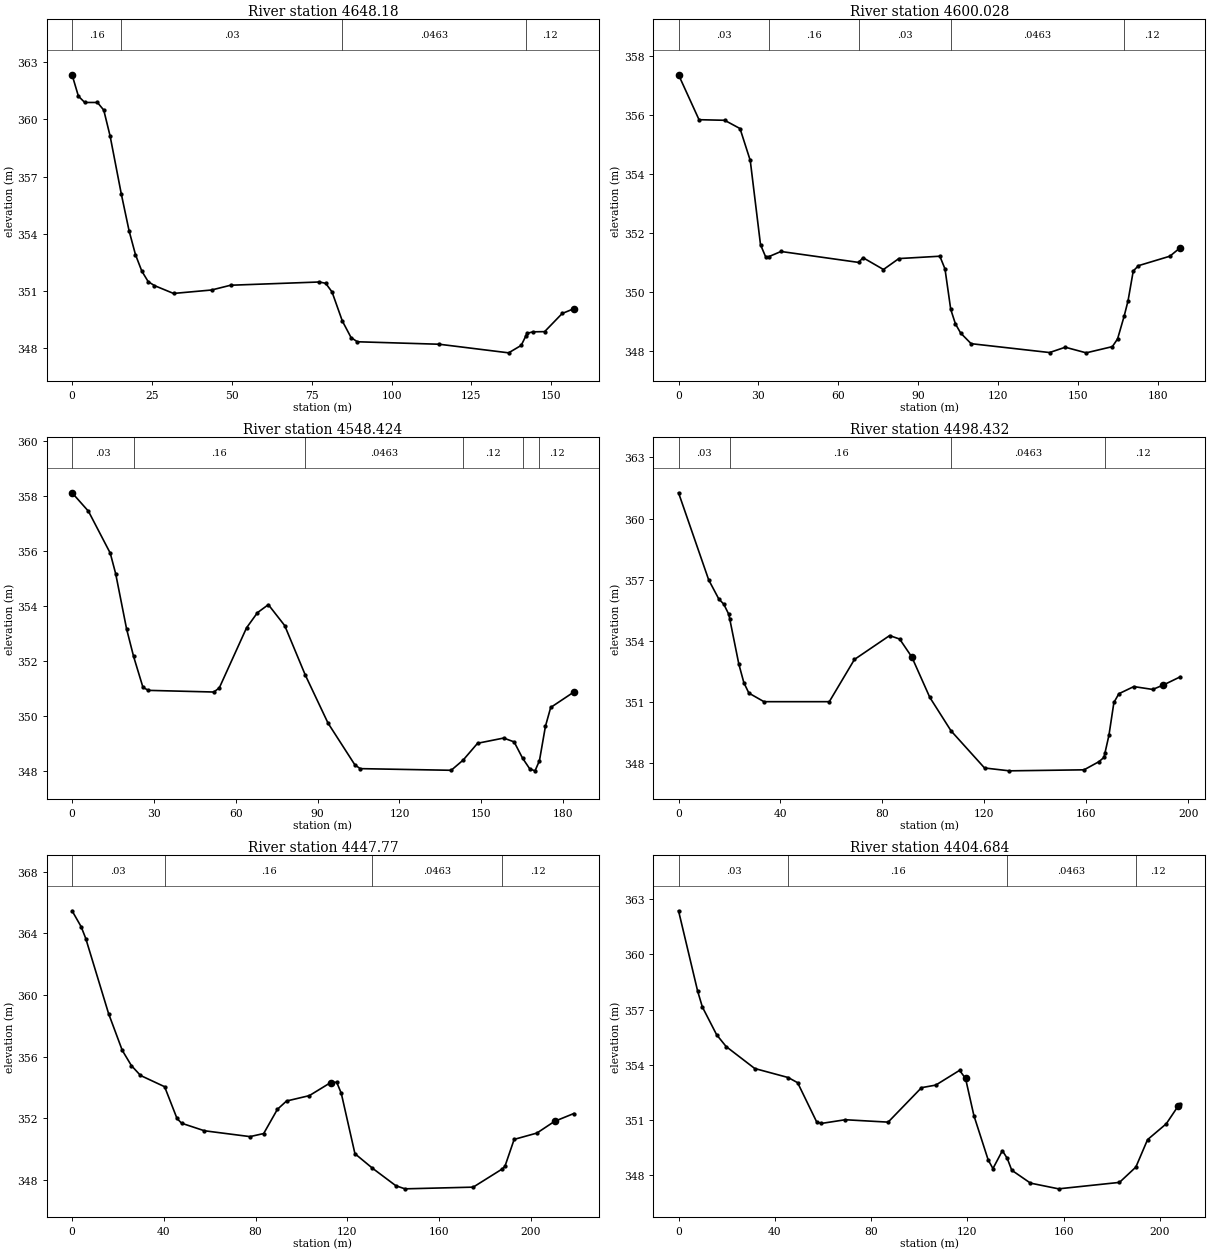
Type RM Length L Ch R = 1 ,4648.18 ,60,48.15,50.34
XS GIS Cut Line= 4
     320554.2473    4050058.6163      320629.645     4050102.679
      320675.632    4050129.5539     320690.4575    4050136.7511
#Sta/Elev= 30
       0  362.33    1.98  361.21    3.97  360.88    7.94  360.88    9.92  360.48
   11.91  359.12   15.42  356.08   17.86  354.15   19.85  352.91   21.83  352.05
   23.82   351.5    25.8  351.29   31.76  350.88   43.66  351.06   49.62  351.31
   77.41  351.48   79.39  351.41   81.37  350.96   84.59  349.44   87.33  348.57
    89.3  348.35  114.95  348.22  136.65  347.77  140.59  348.16  141.97  348.63
  142.42  348.79  144.26  348.87  147.92  348.88  153.41  349.83  157.07  350.08
#Mann= 4 ,-1 , 0
       0     .16       0   15.42     .03       0   84.59   .0463       0
  141.97     .12       0
Bank Sta=0,157.07
XS Rating Curve= 0 ,0
Exp/Cntr=0.3,0.1

Type RM Length L Ch R = 1 ,4600.028,35.94,51.6,51
XS GIS Cut Line= 4
     320500.7236    4050105.8024     320545.7491    4050127.5448
     320595.1043     4050135.642     320669.8785    4050182.6929
#Sta/Elev= 30
       0  357.35    7.69  355.83   17.31  355.81   23.08  355.53   26.92  354.45
   30.77   351.6   32.69  351.19   34.01   351.2   38.46  351.37    67.6     351
   69.24  351.16   76.93  350.76    82.7  351.13   98.09  351.21  100.02  350.78
  102.18  349.41  103.94  348.92   105.9  348.61  109.83  348.25  139.28  347.95
  145.17  348.13  153.02  347.94  162.84  348.15   164.8  348.41  167.27  349.18
  168.73   349.7  170.69  350.71  172.65  350.89  184.43  351.21  188.36   351.5
#Mann= 5 ,-1 , 0
       0     .03       0   34.01     .16       0    67.6     .03       0
  102.18   .0463       0  167.27     .12       0
Bank Sta=0,188.36
XS Rating Curve= 0 ,0
Exp/Cntr=0.3,0.1

Type RM Length L Ch R = 1 ,4548.424,48.23,49.99,51.73
XS GIS Cut Line= 5
     320492.4164    4050126.9221     320565.4709    4050175.8588
     320611.1192     4050206.437     320643.7081    4050226.5351
     320646.1108    4050227.8755
#Sta/Elev= 30
       0  358.11       6  357.44   13.99  355.92   15.99  355.17   19.98  353.17
   22.55  352.17   25.98  351.05   27.98  350.94   51.96  350.88   53.96  351.03
   63.95  353.21   67.95  353.76   71.94  354.05   77.94  353.29   85.46   351.5
   93.82  349.75  103.63  348.24  105.59   348.1  138.95  348.04  143.33  348.41
  148.62  349.02  158.19  349.21  162.02  349.07  165.11  348.48  167.76  348.09
  169.68  348.02   171.3  348.39   173.5  349.64  175.42  350.32  183.91  350.88
#Mann= 6 ,-1 , 0
       0     .03       0   22.55     .16       0   85.46   .0463       0
  143.33     .12       0  165.11   .0463       0   171.3     .12       0
Bank Sta=0,183.91
XS Rating Curve= 0 ,0
Exp/Cntr=0.3,0.1

Type RM Length L Ch R = 1 ,4498.432,50.94,50.66,50.9
XS GIS Cut Line= 5
     320456.1551    4050158.6168       320536.79    4050215.3347
     320602.2454    4050261.3754     320616.4107    4050270.2253
     320617.7136    4050271.0676
#Sta/Elev= 30
       0  361.27   11.83     357   15.77  356.07   17.75  355.81   19.72  355.31
   20.13  355.06   23.66  352.87   25.63  351.96    27.6  351.45   33.52  351.03
   59.15  351.03   69.01   353.1   82.81  354.27   86.75   354.1   91.52  353.22
   98.58  351.24  106.91   349.6  120.05  347.78  129.81  347.64  159.09  347.69
  164.95  348.09   166.9   348.3  167.32  348.53  168.85  349.38   170.8  350.99
  172.75  351.42  178.61  351.77  186.03  351.63  190.24  351.85  196.86  352.25
#Mann= 4 ,-1 , 0
       0     .03       0   20.13     .16       0  106.91   .0463       0
  167.32     .12       0
Bank Sta=91.52,190.24
XS Rating Curve= 0 ,0
Exp/Cntr=0.3,0.1

Type RM Length L Ch R = 1 ,4447.77 ,39.28,43.09,49.6
XS GIS Cut Line= 4
     320406.1333    4050185.6172     320510.3316    4050258.7264
     320576.8649    4050305.4085     320585.5429    4050310.7273
#Sta/Elev= 30
       0  365.46    3.98  364.42    5.97  363.66   15.91  358.79   21.88   356.4
   25.86  355.41   29.83  354.77   40.34  354.04   45.74  351.98   47.73  351.67
   57.68  351.18   77.57   350.8   83.53     351    89.5  352.57   93.48  353.11
  103.42  353.46  112.75  354.31  115.35  354.33  117.34  353.62  123.31  349.69
  130.94  348.75  141.16  347.61  145.13  347.41  174.86  347.52  187.63  348.71
  188.74  348.89  192.71  350.62  202.62  351.03  210.31  351.79  218.74   352.3
#Mann= 4 ,-1 , 0
       0     .03       0   40.34     .16       0  130.94   .0463       0
  187.63     .12       0
Bank Sta=112.75,210.31
XS Rating Curve= 0 ,0
Exp/Cntr=0.3,0.1

Type RM Length L Ch R = 1 ,4404.684,35.13,47.4,52.8
XS GIS Cut Line= 4
     320384.6058    4050210.6092     320488.5035     4050293.043
      320523.576      4050320.87     320546.7602    4050341.6296
#Sta/Elev= 30
       0  362.36    7.92  358.01     9.9  357.14   15.84  355.63    19.8  354.99
   31.67   353.8   45.58  353.31   49.49  353.03   57.41   350.9   59.39  350.82
   69.28  351.02    87.1  350.89  100.96  352.76  106.89   352.9  116.79   353.7
  119.27  353.26  122.73  351.25  128.67  348.84  130.65  348.37  134.57  349.34
  136.57  348.93  138.47  348.28  146.25  347.58  157.93  347.27  183.23  347.62
  190.04  348.45   194.9  349.94  202.68   350.8  207.65  351.77  208.52  351.85
#Mann= 4 ,-1 , 0
       0     .03       0   45.58     .16       0  136.57   .0463       0
  190.04     .12       0
Bank Sta=119.27,207.65
XS Rating Curve= 0 ,0
Exp/Cntr=0.3,0.1

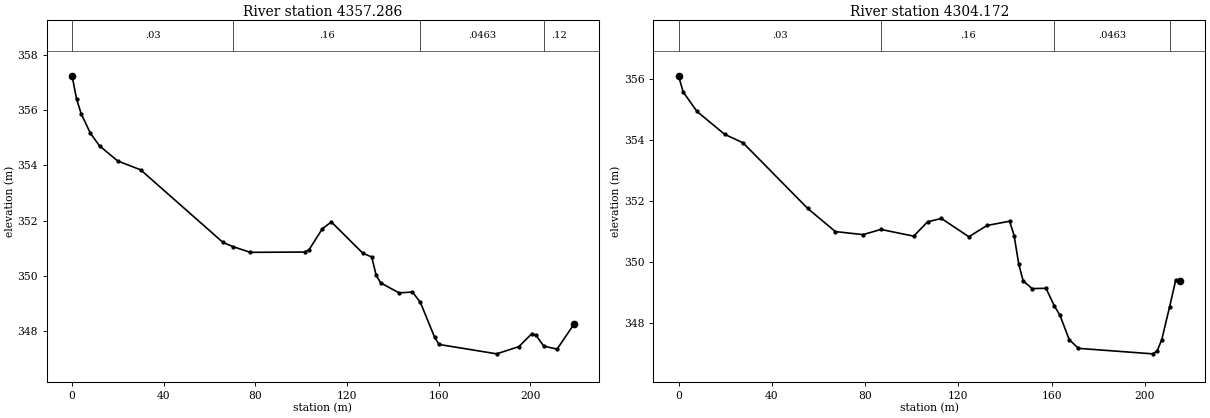
Type RM Length L Ch R = 1 ,4357.286,59.28,53.11,51.7
XS GIS Cut Line= 6
     320355.6307    4050235.7011     320420.0751    4050292.2872
     320462.8057    4050311.7008      320463.864     4050323.607
     320499.3183    4050364.4852      320511.251    4050380.7478
#Sta/Elev= 30
       0  357.25    1.99   356.4    3.99  355.87    7.98  355.17   11.97  354.71
   19.94  354.16   29.92  353.84   65.82  351.21   70.41  351.05   77.78  350.85
  101.41  350.86  103.36  350.94  109.23  351.71  113.14  351.95  126.83  350.82
  130.74  350.68   132.7  350.01  134.69  349.74  142.66  349.38  148.51  349.41
  151.94  349.04  158.18  347.77  160.11  347.51  185.23  347.17   194.9  347.43
  200.59   347.9  202.43  347.84  205.81  347.45   211.6  347.34  218.93  348.24
#Mann= 4 ,-1 , 0
       0     .03       0   70.41     .16       0  151.94   .0463       0
  205.81     .12       0
Bank Sta=0,218.93
XS Rating Curve= 0 ,0
Exp/Cntr=0.3,0.1

Type RM Length L Ch R = 1 ,4304.172,19.2,24.8,26.26
XS GIS Cut Line= 4
     320343.5792    4050243.1492     320403.5441    4050347.8591
     320433.0418    4050362.5935     320469.9492    4050411.8985
#Sta/Elev= 30
       0  356.12    1.98  355.59    7.91  354.95   19.78   354.2   27.69  353.92
   55.39  351.77   67.26  351.01   79.12  350.91   86.81  351.08  100.88  350.86
  106.82  351.33  112.75  351.44  124.54  350.84   132.3  351.21     142  351.35
  143.94  350.88  145.88  349.96  147.82  349.39   151.7  349.14  157.61  349.15
  161.21  348.57  163.57  348.27  167.54  347.47  171.52  347.18  203.31     347
  205.29  347.09  207.28  347.47  210.59  348.53  213.24  349.41  215.23  349.39
#Mann= 4 ,-1 , 0
       0     .03       0   86.81     .16       0  161.21   .0463       0
  210.59     .12       0
Bank Sta=0,215.23
XS Rating Curve= 0 ,0
Exp/Cntr=0.3,0.1

River Reach=Clinch River    ,Middle Reach
Reach XY= 30
     320444.8197    4050417.4518     320444.2269    4050418.1719
     320410.4457    4050444.1319     320233.1726    4050515.3925
     320168.6084    4050537.7791     320160.8653    4050539.6121
     320156.9937    4050540.5285      320155.058    4050540.9868
     320151.1864    4050541.9032     320145.3791     4050543.278
     320141.5075    4050544.1944     320124.0855    4050548.3186
     320120.2139     4050549.235     320118.2782    4050549.6933
     320104.7277     4050552.901     320095.0488    4050555.1921
     320089.2415    4050556.5669     320079.5626     4050558.858
     320073.7553    4050560.2328     320064.0764    4050562.5239
     320050.5259    4050565.7316     320048.5902    4050566.1899
     320044.7186    4050567.1063     320027.2966    4050571.2305
      320023.425    4050572.1469     320017.6177    4050573.5217
     320013.7461    4050574.4381     320011.8104    4050574.8964
     320007.9388    4050575.8128     320000.1957    4050577.6458