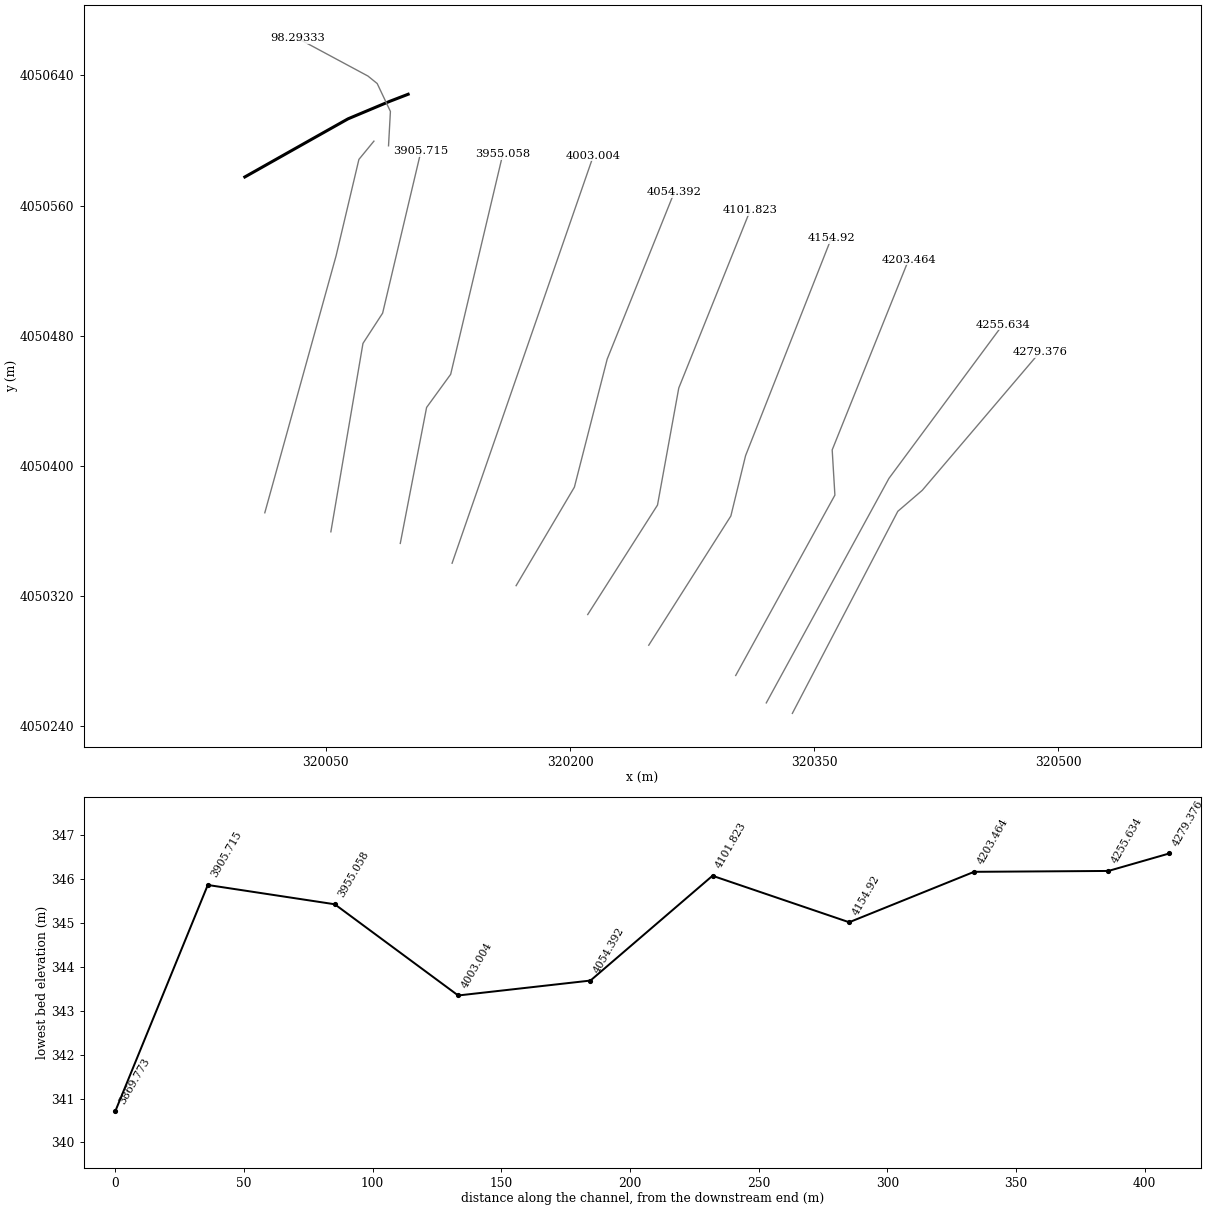
HEC-RAS study WBmod1D.prj: WBmod1D

--- WBmod1D.g03 (geometry) --- (continued)

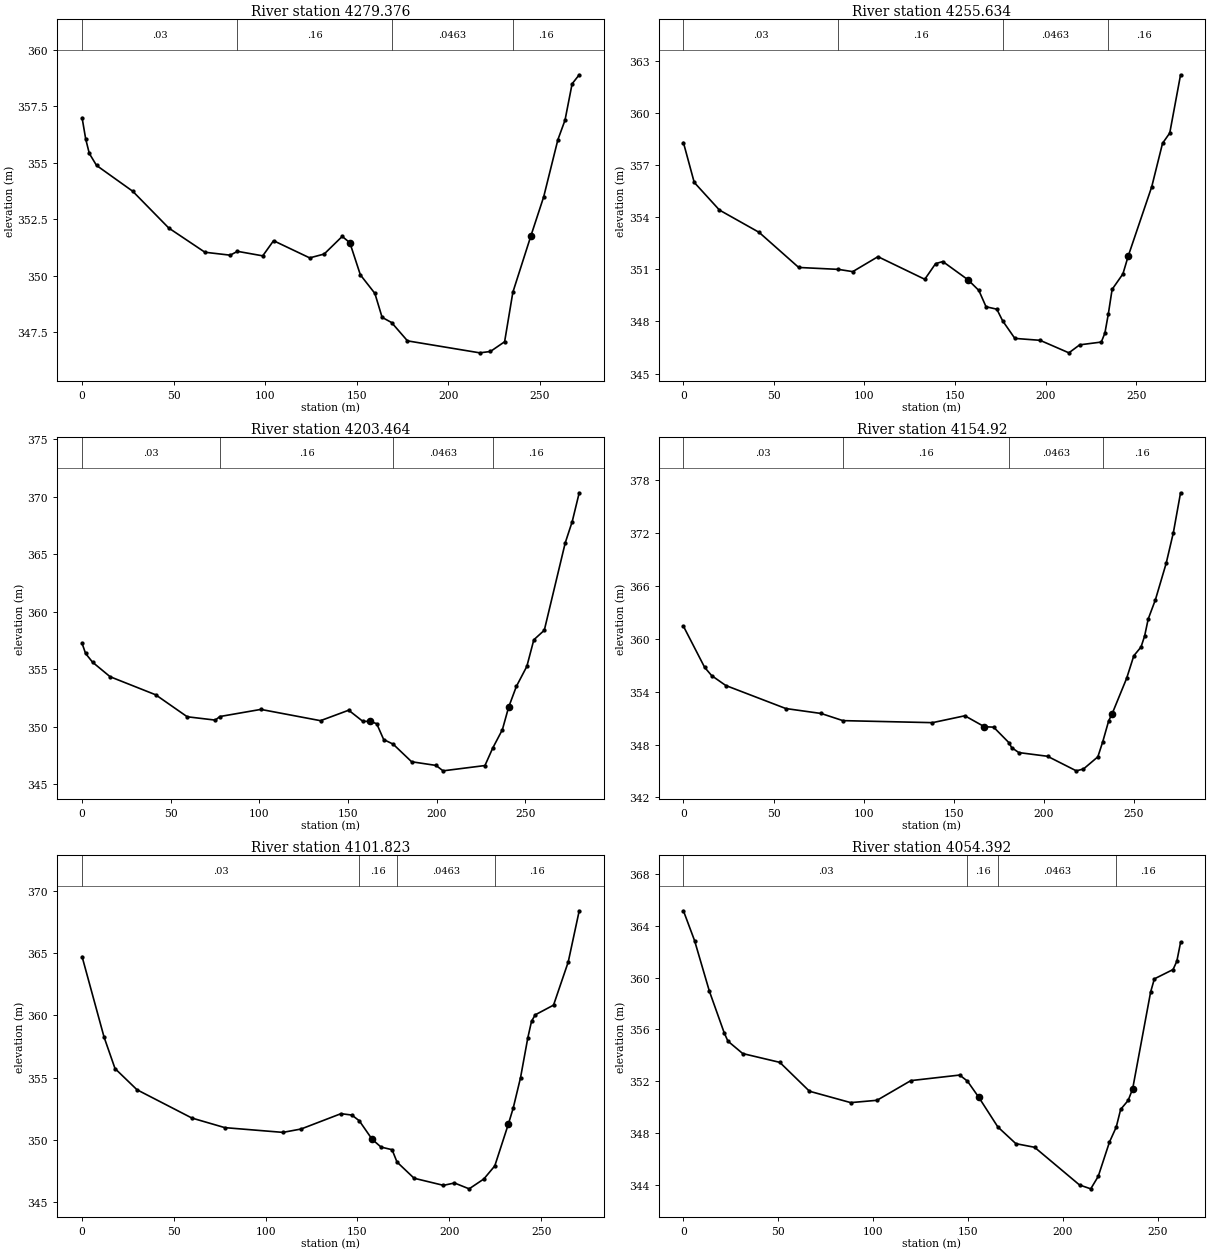
Type RM Length L Ch R = 1 ,4279.376,15.66,23.74,27.2
XS GIS Cut Line= 5
     320336.6232    4050248.0636     320401.4124    4050372.2086
     320416.4359    4050385.1111     320449.7769    4050424.2814
     320488.7458    4050470.0636
#Sta/Elev= 30
       0  356.99    1.97  356.05    3.94  355.41    7.89  354.88   27.61  353.74
   47.34  352.11   67.06  351.04   80.86  350.91   84.83  351.08   98.62  350.88
  104.53  351.55  124.26  350.79  132.15  350.96  142.01  351.74  146.19  351.46
  151.92  350.04  159.84  349.22  163.79  348.16  168.97  347.93  177.64  347.12
  217.09  346.59  222.91  346.65  230.67  347.08  235.17  349.27     245  351.76
     252  353.49  259.76  356.02  263.64  356.88  267.52  358.49   271.4  358.89
#Mann= 4 ,-1 , 0
       0     .03       0   84.83     .16       0  168.97   .0463       0
  235.17     .16       0
Bank Sta=146.19,245
XS Rating Curve= 0 ,0
Exp/Cntr=0.3,0.1

Type RM Length L Ch R = 1 ,4255.634,32.76,52.17,63.74
XS GIS Cut Line= 3
     320320.6015    4050254.5014     320395.9612    4050392.4355
     320465.8256    4050486.7638
#Sta/Elev= 30
       0  358.28    5.97  355.99    19.9   354.4   41.78  353.12   63.67   351.1
   85.52  350.99   93.51  350.86  107.44  351.72   133.3  350.42  139.27  351.32
  143.25  351.44  157.18  350.39  163.15  349.78  167.13  348.84  173.09   348.7
   176.3  348.03  183.04  347.02  196.97  346.91  212.89  346.19  218.85  346.65
  230.79  346.81  232.78  347.33  234.66  348.42  236.76  349.84  242.73  350.73
  245.61  351.74  258.64  355.74  264.61  358.24  268.59  358.83  274.56  362.18
#Mann= 4 ,-1 , 0
       0     .03       0   85.52     .16       0   176.3   .0463       0
  234.66     .16       0
Bank Sta=157.18,245.61
XS Rating Curve= 0 ,0
Exp/Cntr=0.3,0.1

Type RM Length L Ch R = 1 ,4203.464,53.89,48.54,48.84
XS GIS Cut Line= 4
     320301.8165    4050271.3392     320362.7586    4050382.1803
     320361.0967    4050409.9472     320408.0969    4050526.8685
#Sta/Elev= 30
       0  357.25    1.98  356.37    5.93  355.61   15.81  354.35    41.5  352.78
   59.29  350.87    75.1  350.58   77.68  350.89   100.8  351.51  134.44  350.53
  150.33  351.44  158.24  350.48  162.53  350.46  166.12  350.27  170.06  348.89
   175.4  348.49  185.81  346.96  199.59  346.64  203.53  346.17  227.16  346.63
  231.52  348.14     237  349.75  240.49  351.69  244.88  353.51  250.79  355.25
  254.72  357.56  260.63  358.39  272.44  365.99  276.38  367.84  280.32  370.34
#Mann= 4 ,-1 , 0
       0     .03       0   77.68     .16       0   175.4   .0463       0
  231.52     .16       0
Bank Sta=162.53,240.49
XS Rating Curve= 0 ,0
Exp/Cntr=0.3,0.1

Type RM Length L Ch R = 1 ,4154.92 ,50.74,53.1,52.8
XS GIS Cut Line= 4
     320248.3828    4050289.9528     320298.8335    4050369.3239
     320307.8783    4050406.4264     320360.5787     4050540.048
#Sta/Elev= 30
       0  361.41   11.76  356.75   15.67  355.81   23.51  354.69   56.82  352.08
   76.41  351.52   88.49  350.71  138.22  350.48  156.18  351.26  167.01  350.02
  172.14  349.97  180.68   348.2  182.11  347.66   186.1  347.09  202.06  346.67
  218.02  345.02  222.01  345.23  229.99  346.61  232.72  348.33  235.98  350.68
  237.93   351.5  245.95   355.5  249.94  358.06  253.93  359.05  255.93  360.29
  257.92  362.22  261.91   364.4   267.9  368.54  271.89  372.02  275.88  376.53
#Mann= 4 ,-1 , 0
       0     .03       0   88.49     .16       0  180.68   .0463       0
  232.72     .16       0
Bank Sta=167.01,237.93
XS Rating Curve= 0 ,0
Exp/Cntr=0.3,0.1

Type RM Length L Ch R = 1 ,4101.823,48.48,47.43,47.43
XS GIS Cut Line= 4
     320210.8897    4050308.7956     320253.7623     4050376.048
      320266.836    4050447.9719      320310.819    4050557.3871
#Sta/Elev= 30
       0  364.71   11.96  358.26   17.94  355.73   29.91  354.03   59.82  351.76
   77.76  350.99  109.39  350.61  119.27  350.88     141  352.11  146.93     352
  150.99  351.54  158.01  350.05  162.85  349.43  168.85  349.22  171.53  348.23
  180.84  346.93  196.83  346.36  202.83  346.55  210.82  346.08  218.82  346.87
  224.79  347.92  232.26  351.31  234.81  352.55   238.8  354.99   242.8  358.21
   244.8  359.52   246.8  360.04  256.79  360.82  264.79  364.28  270.78  368.39
#Mann= 4 ,-1 , 0
       0     .03       0  150.99     .16       0  171.53   .0463       0
  224.79     .16       0
Bank Sta=158.01,232.26
XS Rating Curve= 0 ,0
Exp/Cntr=0.3,0.1

Type RM Length L Ch R = 1 ,4054.392,50.43,51.39,53.8
XS GIS Cut Line= 4
     320166.8993    4050326.5308     320202.6957    4050387.0594
     320222.8456    4050465.7071     320264.0367    4050568.1773
#Sta/Elev= 30
       0  365.17    5.86  362.87   13.67  358.96   21.49  355.74   23.44   355.1
   31.25  354.14   50.79  353.46   66.41  351.23   88.14  350.35     102  350.53
  119.83  352.05  145.57  352.48  149.65  352.01  155.59  350.77  165.68  348.47
  175.17  347.18  185.04   346.9   208.7  343.99  214.62  343.69  218.56  344.65
  224.48   347.3  228.06  348.46  230.39  349.83  234.34  350.52   236.7  351.41
  246.17  358.89  248.14  359.91     258  360.63  259.98  361.27  261.95  362.72
#Mann= 4 ,-1 , 0
       0     .03       0  149.65     .16       0  165.68   .0463       0
  228.06     .16       0
Bank Sta=155.59,236.7
XS Rating Curve= 0 ,0
Exp/Cntr=0.3,0.1

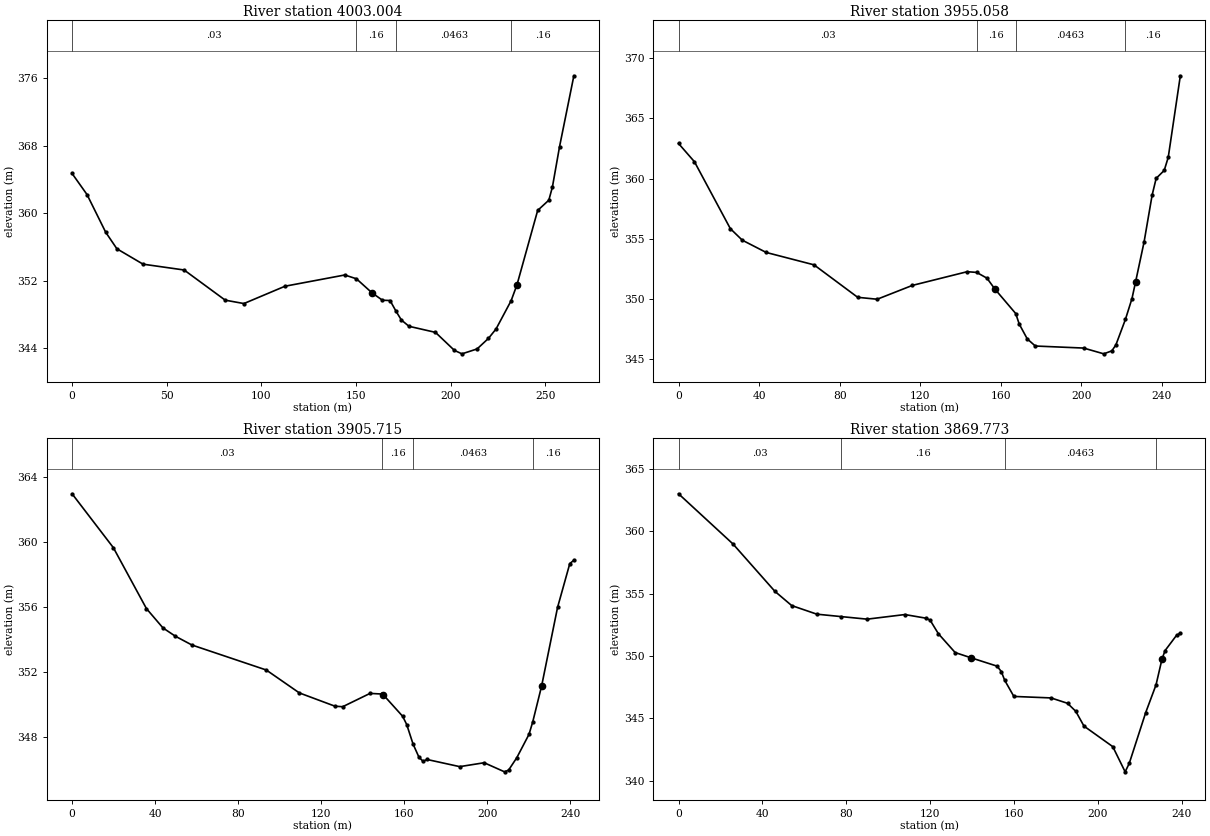
Type RM Length L Ch R = 1 ,4003.004,42.97,47.95,52
XS GIS Cut Line= 4
     320127.5561     4050340.332     320176.6961    4050482.0545
     320209.4561    4050576.5361     320214.4091    4050590.8209
#Sta/Elev= 30
       0  364.69    7.89   362.2   17.76  357.74   23.68  355.78    37.5  353.96
   59.21  353.27   80.92   349.7   90.79   349.3   112.5  351.35  144.08  352.68
  150.24  352.23  158.41  350.58     164  349.69     168  349.66  171.24  348.36
     174  347.35     178  346.61     192  345.89     202  343.76     206  343.35
     214  343.93     220  345.18     224  346.29  231.98  349.64  235.08  351.53
     246  360.32  251.89  361.53  253.78  363.08  257.56  367.87  265.12  376.25
#Mann= 4 ,-1 , 0
       0     .03       0  150.24     .16       0  171.24   .0463       0
  231.98     .16       0
Bank Sta=158.41,235.08
XS Rating Curve= 0 ,0
Exp/Cntr=0.3,0.1

Type RM Length L Ch R = 1 ,3955.058,50.75,49.34,49.49
XS GIS Cut Line= 5
     320095.7166    4050352.4919     320111.8844    4050436.0227
      320126.686    4050456.3993     320135.6451    4050494.2464
     320158.6805     4050591.557
#Sta/Elev= 30
       0  362.92    7.91   361.4   25.72  355.84   31.66  354.88   43.53  353.86
   67.27  352.83   88.96  350.13   98.64  349.97   116.1  351.12  143.33  352.26
  148.04   352.2  153.16  351.72  157.06  350.82  167.43  348.78  169.16  347.91
  173.16  346.67  177.16  346.08  201.16  345.91  211.16  345.43  215.16  345.68
  217.16  346.17  221.89  348.29  225.16  350.03  226.94  351.41  231.16  354.73
  235.16  358.63  237.16  360.02  241.16  360.68  243.16  361.77  249.16  368.55
#Mann= 4 ,-1 , 0
       0     .03       0  148.04     .16       0  167.43   .0463       0
  221.89     .16       0
Bank Sta=157.06,226.94
XS Rating Curve= 0 ,0
Exp/Cntr=0.3,0.1

Type RM Length L Ch R = 1 ,3905.715,37.46,35.94,32.79
XS GIS Cut Line= 4
     320053.0693    4050359.6191     320072.7926    4050475.3878
     320084.8748    4050493.9783     320108.3964     4050593.343
#Sta/Elev= 30
       0  362.99    19.9  359.67   35.83  355.92   43.79  354.73   49.76  354.22
   57.72  353.68   93.55  352.14  109.47  350.73  126.67  349.91  130.37  349.88
  143.54   350.7   149.3  350.66   149.8  350.63  159.25  349.29  161.21  348.78
  164.26  347.58   167.1  346.77  169.06  346.52  171.03  346.63  186.74  346.19
  198.52  346.43  208.34  345.87   210.3  345.98  214.23  346.74  220.12  348.18
   221.9  348.94  226.18  351.15  233.86  355.99  239.76  358.69  241.72   358.9
#Mann= 4 ,-1 , 0
       0     .03       0   149.3     .16       0  164.26   .0463       0
   221.9     .16       0
Bank Sta=149.8,226.18
XS Rating Curve= 0 ,0
Exp/Cntr=0.3,0.1

Type RM Length L Ch R = 1 ,3869.773,65,66.46,14.16
XS GIS Cut Line= 4
      320012.478    4050371.3182     320056.2836    4050529.2275
     320070.2988    4050588.4335     320079.5228    4050599.6658
#Sta/Elev= 30
       0  363.02   25.98  358.99   45.96  355.19   53.96  354.05   65.95  353.36
   77.29  353.17   89.93  352.96  107.92  353.33  117.91  353.04  119.91  352.89
   123.9  351.79   131.9  350.28  139.48  349.86  151.88  349.19  153.88  348.76
   155.5  348.06  159.88  346.76  177.61  346.64  185.46  346.21  189.39  345.57
  193.31  344.38  207.05  342.73  212.94  340.71   214.9  341.39  222.75  345.47
  227.67  347.69   230.5  349.75  231.98  350.44  237.43  351.66  239.25  351.83
#Mann= 4 ,-1 , 0
       0     .03       0   77.29     .16       0   155.5   .0463       0
  227.67     .16       0
Bank Sta=139.48,230.5
XS Rating Curve= 0 ,0
Exp/Cntr=0.3,0.1

River Reach=North Fork      ,Tributary
Reach XY= 30
     320100.5544    4050628.4754      320098.922    4050627.8466
     320097.2896    4050627.2177     320092.3924    4050625.3313
       320090.76    4050624.7024     320089.1276    4050624.0736
     320080.0089    4050620.2466      320072.714    4050617.1849
     320063.5953    4050613.3579     320061.9623    4050612.4397
     320060.3292    4050611.5216     320058.6962    4050610.6034
     320057.0631    4050609.6853     320055.4301    4050608.7671
      320050.531    4050606.0127      320048.898    4050605.0945
     320047.2649    4050604.1764     320045.6319    4050603.2582
     320043.9988    4050602.3401     320042.3658    4050601.4219
      320040.679    4050600.4709     320028.8714    4050593.8135
     320025.4978    4050591.9115      320023.811    4050590.9604
     320018.7505    4050588.1073     320017.0637    4050587.1562
     320013.6901    4050585.2542     320003.5693    4050579.5479
     320001.8825    4050578.5968     320000.1957    4050577.6458

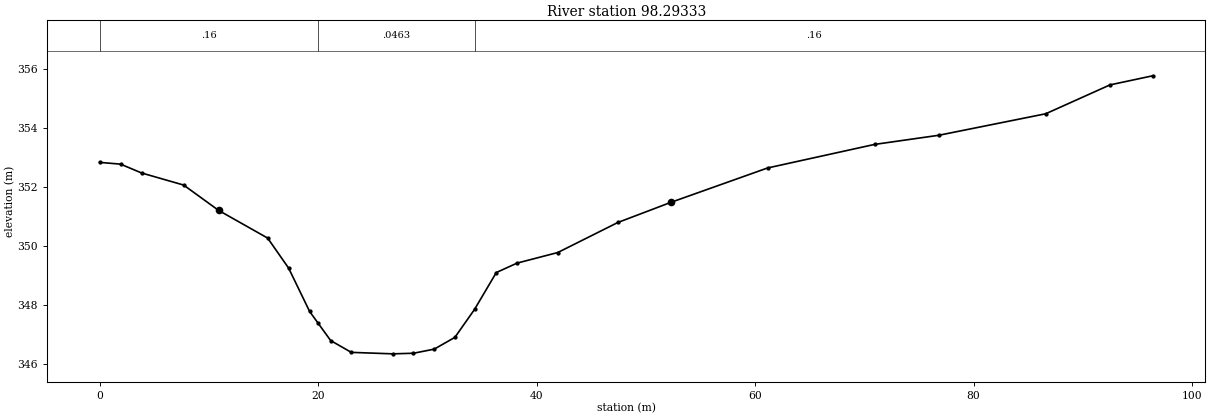
Type RM Length L Ch R = 1 ,98.29333,10.02,11.21,14.23
XS GIS Cut Line= 5
     320088.4987    4050596.8002     320089.6548    4050617.9138
     320081.5393    4050635.0498     320075.8435    4050639.6626
     320032.7105    4050662.8283
#Sta/Elev= 27
       0  352.83    1.92  352.77    3.84  352.47    7.69  352.06   10.89   351.2
   15.38  350.26    17.3  349.24   19.22  347.77   19.96  347.39   21.15  346.78
   23.04  346.38   26.83  346.33   28.73  346.35   30.63  346.49   32.52  346.89
   34.32  347.84   36.31  349.09   38.21  349.41   41.94  349.77   47.44  350.79
   52.27  351.47   61.14  352.64   70.94  353.44   76.81  353.75    86.6  354.48
   92.48  355.46    96.4  355.77
#Mann= 3 ,-1 , 0
       0     .16       0   19.96   .0463       0   34.32     .16       0
Bank Sta=10.89,52.27
XS Rating Curve= 0 ,0
Exp/Cntr=0.3,0.1