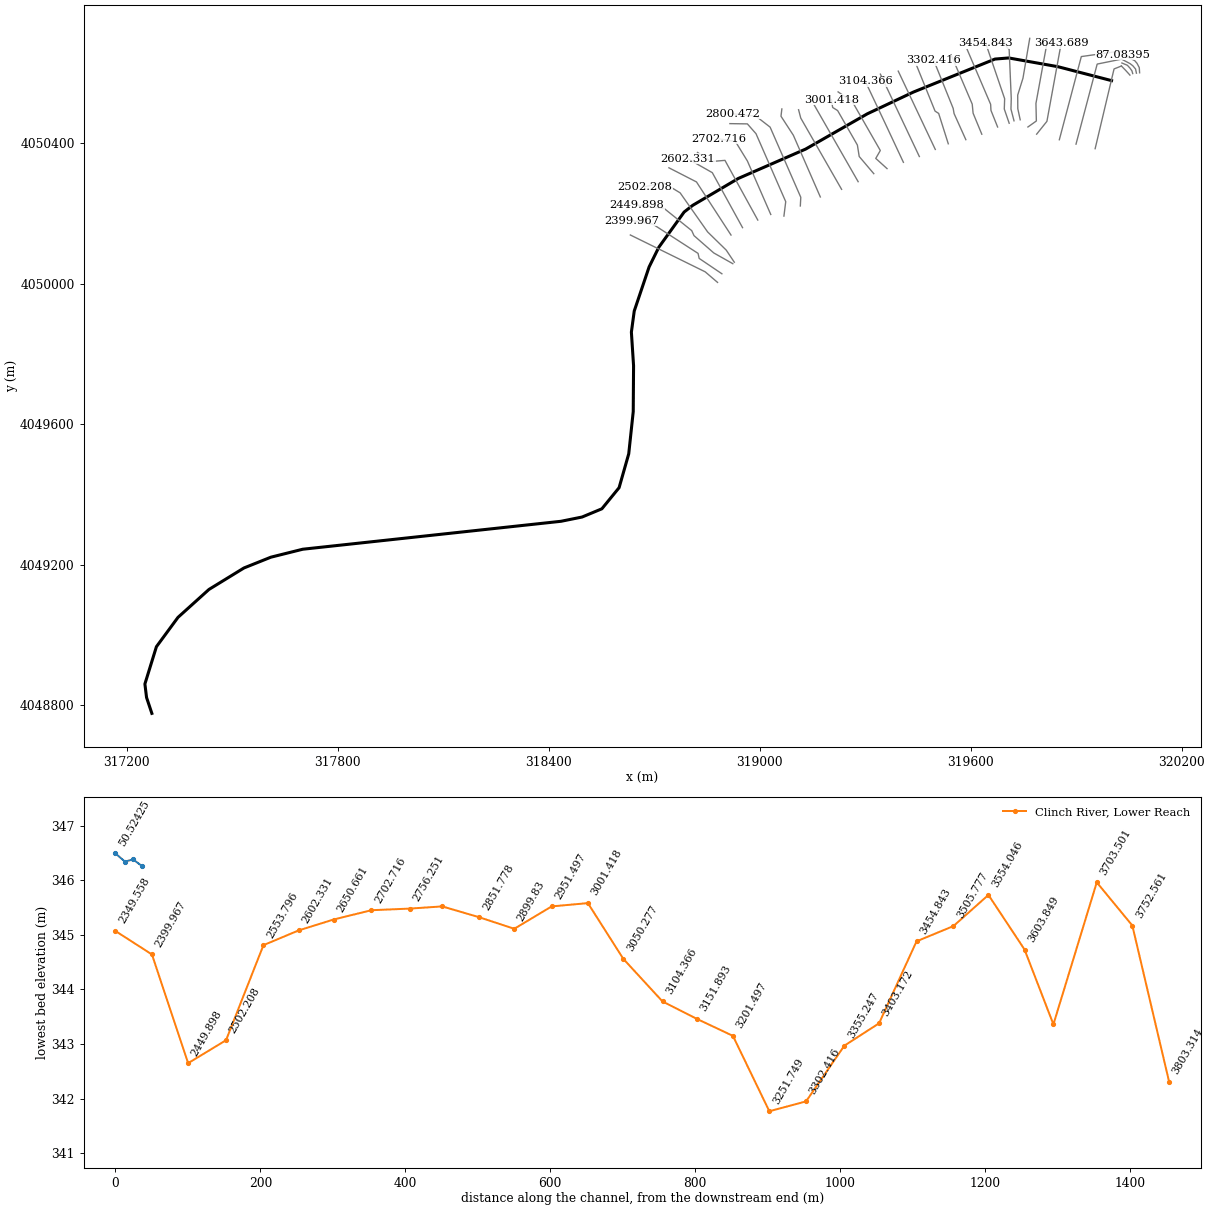
HEC-RAS study WBmod1D.prj: WBmod1D

--- WBmod1D.g03 (geometry) --- (continued)

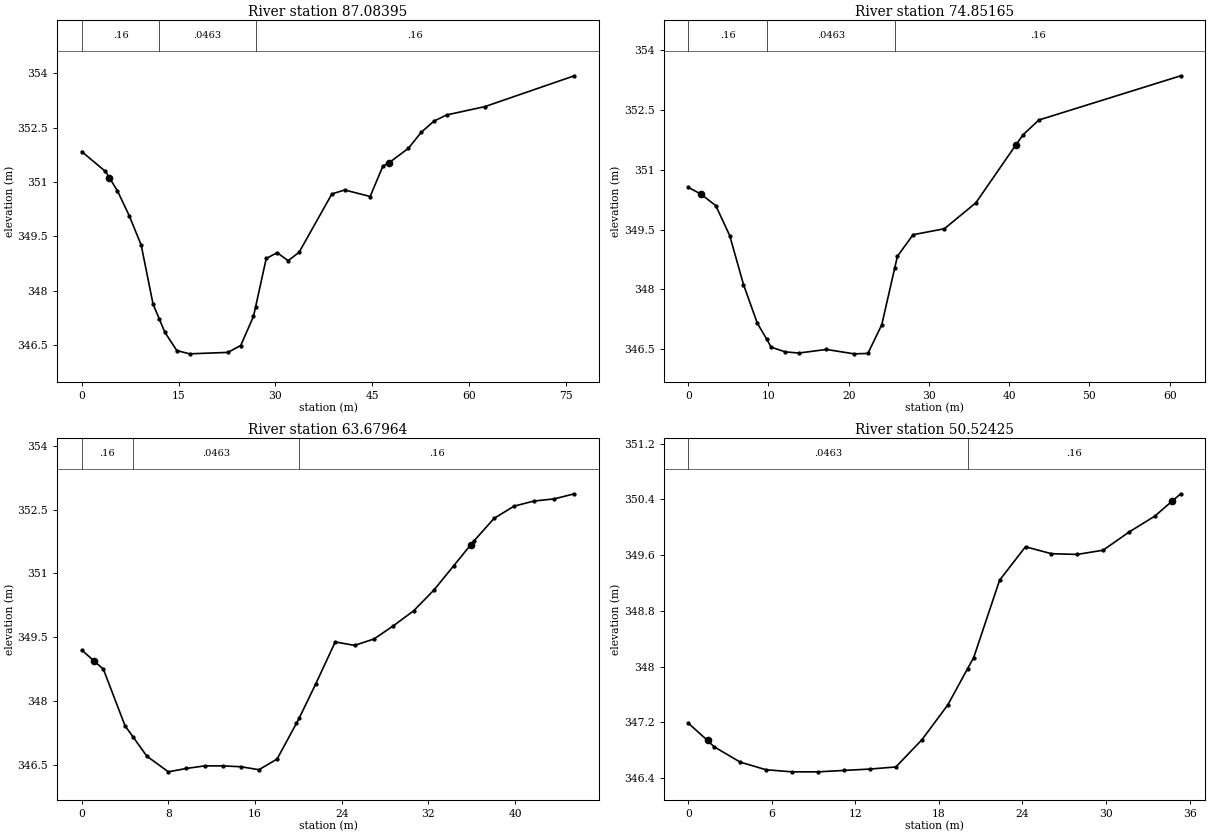
Type RM Length L Ch R = 1 ,87.08395,9.71,12.23,14.68
XS GIS Cut Line= 5
     320080.0055    4050599.8958     320079.0598    4050614.5937
     320072.6152    4050626.8593      320066.001    4050634.5826
     320032.3946     4050651.348
#Sta/Elev= 30
       0  351.84    3.68  351.29    4.27  351.12    5.52  350.76    7.36  350.07
    9.21  349.26   11.05  347.63   12.02  347.22   12.89  346.85   14.73  346.35
   16.71  346.26   22.65   346.3   24.63  346.49    26.6  347.29   26.94  347.56
   28.58  348.89   30.28  349.05   31.97  348.83   33.67  349.06   38.75  350.67
   40.73  350.78   44.68   350.6   46.66  351.44    47.6  351.53   50.61  351.93
   52.59  352.37   54.57  352.68   56.54  352.85   62.47  353.08   76.31  353.93
#Mann= 3 ,-1 , 0
       0     .16       0   12.02   .0463       0   26.94     .16       0
Bank Sta=4.27,47.6
XS Rating Curve= 0 ,0
Exp/Cntr=0.3,0.1

Type RM Length L Ch R = 1 ,74.85165,10.7,11.17,9.52
XS GIS Cut Line= 5
     320070.9412    4050598.7874     320068.5241    4050610.5976
     320060.7536    4050619.8212     320053.0692    4050625.8412
     320028.7965    4050638.7647
#Sta/Elev= 23
       0  350.56    1.58  350.39    3.44   350.1    5.17  349.35    6.89  348.12
    8.61  347.15    9.78  346.75   10.33  346.55   12.06  346.43   13.78   346.4
   17.22  346.49   20.67  346.38   22.39  346.39   24.12  347.11   25.73  348.53
   26.07  348.83   28.02  349.37   31.92  349.52   35.84  350.17   40.85  351.63
   41.73  351.88    43.7  352.25   61.38  353.36
#Mann= 3 ,-1 , 0
       0     .16       0    9.78   .0463       0   25.73     .16       0
Bank Sta=1.58,40.85
XS Rating Curve= 0 ,0
Exp/Cntr=0.3,0.1

Type RM Length L Ch R = 1 ,63.67964,9.19,13.16,9.67
XS GIS Cut Line= 5
     320060.3787    4050597.6496     320058.2182    4050605.3508
       320052.38      4050613.51      320045.073    4050621.3843
     320029.6308    4050627.7458
#Sta/Elev= 30
       0   349.2    1.11  348.95       2  348.75       4  347.42    4.74  347.16
       6  346.71       8  346.34    9.67  346.42   11.34  346.48   13.01  346.48
   14.69  346.46   16.36  346.39   18.03  346.64   19.82  347.48   20.07   347.6
   21.61  348.41    23.4  349.39   25.19  349.31   26.98  349.46   28.77  349.77
   30.63  350.12   32.48   350.6   34.34  351.18    35.9  351.67    36.2  351.76
   38.05  352.29   39.91  352.58   41.76   352.7   43.62  352.75   45.47  352.87
#Mann= 3 ,-1 , 0
       0     .16       0    4.74   .0463       0   20.07     .16       0
Bank Sta=1.11,35.9
XS Rating Curve= 0 ,0
Exp/Cntr=0.3,0.1

Type RM Length L Ch R = 1 ,50.52425,0.47,50.52,0.27
XS GIS Cut Line= 3
     320052.4888    4050593.3402      320039.956    4050607.1391
     320028.3079    4050619.1469
#Sta/Elev= 23
       0  347.19    1.39  346.94    1.86  346.85    3.73  346.63    5.59  346.52
    7.46  346.49    9.32  346.49   11.18  346.51   13.05  346.53   14.91  346.56
   16.78  346.95   18.64  347.45   20.06  347.97    20.5  348.13   22.36  349.24
   24.22  349.72   26.08  349.62   27.93  349.61   29.79  349.67   31.65  349.93
   33.51  350.16   34.72  350.37   35.37  350.48
#Mann= 2 ,-1 , 0
       0   .0463       0   20.06     .16       0
Bank Sta=1.39,34.72
XS Rating Curve= 0 ,0
Exp/Cntr=0.3,0.1

River Reach=Clinch River    ,Lower Reach
Reach XY= 30
     320000.1957    4050577.6458     319847.7558    4050617.2619
     319707.8946    4050642.1325     319668.8344    4050638.9712
     319436.8483    4050544.9867     319306.1571     4050483.246
      319130.716    4050382.8303     318939.1759    4050299.2019
     318809.4861    4050222.6029     318785.0756    4050203.5528
     318713.1661    4050103.3932     318685.5272    4050047.3097
     318643.2763    4049921.8283     318635.1553     4049861.796
      318641.373    4049766.1517     318640.4305    4049635.7152
      318627.629    4049515.4248     318600.2204    4049419.0128
     318551.2724    4049358.9523     318494.9381    4049335.5035
     318435.0816    4049323.3942     317700.7958    4049243.8598
     317610.1851    4049221.1857     317533.7163    4049190.5122
     317434.2463    4049129.4022      317346.219    4049049.9606
     317284.8663    4048966.4423     317252.1242    4048860.3893
     317256.8353    4048821.8354     317271.9132    4048776.6754

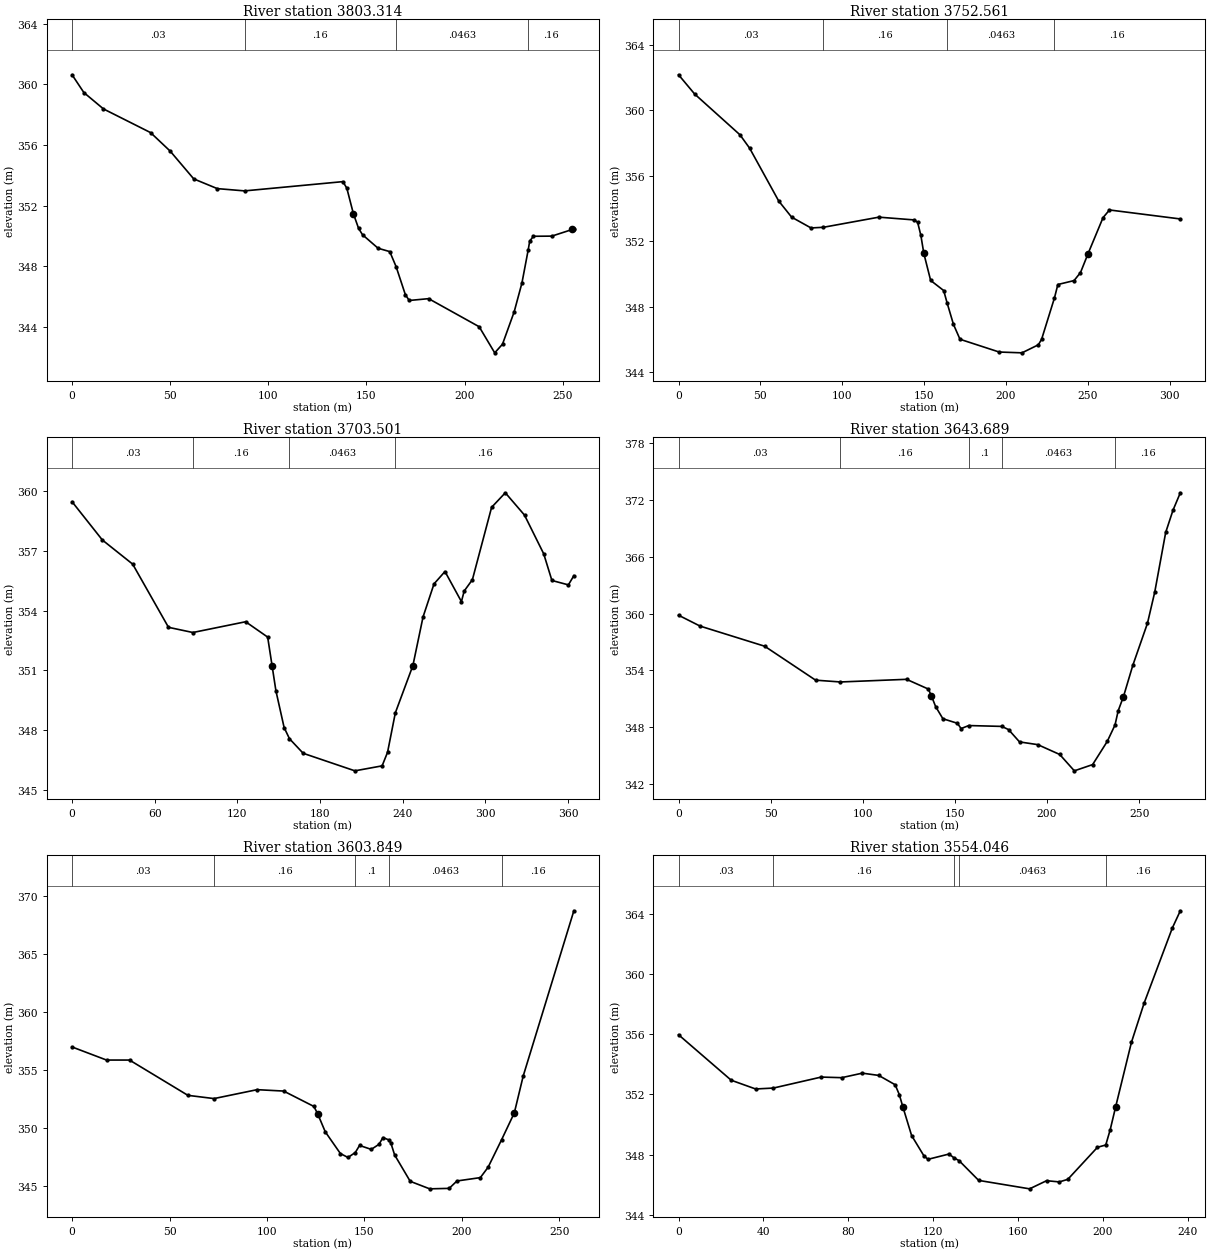
Type RM Length L Ch R = 1 ,3803.314,53.02,50.75,38.45
XS GIS Cut Line= 4
      319953.586     4050383.901     319988.1391     4050529.867
     320007.3026    4050610.8214     320028.1876    4050619.1885
#Sta/Elev= 30
       0  360.63       6  359.46      16  358.38      40  356.82      50   355.6
      62  353.77      74  353.13   87.91  352.98     138  353.59     140  353.16
  143.36  351.47     146  350.51     148  350.09  155.94   349.2  161.88  348.98
  165.11  347.99  169.81  346.15  171.79  345.76  181.69  345.88  207.44  344.03
  215.36  342.31  219.33  342.88  225.27  345.01  229.23  346.91  232.45  349.11
  233.19  349.67  235.07  349.99  244.44     350  254.94  350.44  255.69   350.5
#Mann= 4 ,-1 , 0
       0     .03       0   87.91     .16       0  165.11   .0463       0
  232.45     .16       0
Bank Sta=143.36,254.94
XS Rating Curve= 0 ,0
Exp/Cntr=0.3,0.1

Type RM Length L Ch R = 1 ,3752.561,49.63,49.06,67.83
XS GIS Cut Line= 4
     319899.2076     4050396.827      319937.508    4050541.8549
      319959.387    4050624.7017     320028.7848    4050638.7674
#Sta/Elev= 30
       0  362.18    9.87     361    37.5  358.51   43.42  357.69   61.18  354.46
   69.08  353.47   80.92  352.81   88.45  352.85  122.37  353.47  144.08   353.3
  146.05  353.15  148.03  352.35  149.83  351.25  153.99   349.6  161.96  348.98
  164.03  348.23  167.93  346.91  171.92     346  195.83  345.22  209.78  345.17
  219.75  345.66  221.74  345.99  229.62  348.53   231.7  349.35  241.59  349.59
  245.52  350.08  250.15  351.24  259.29  353.44  263.22  353.91   306.5  353.36
#Mann= 4 ,-1 , 0
       0     .03       0   88.45     .16       0  164.03   .0463       0
  229.62     .16       0
Bank Sta=149.83,250.15
XS Rating Curve= 0 ,0
Exp/Cntr=0.3,0.1

Type RM Length L Ch R = 1 ,3703.501,54.69,59.81,74.06
XS GIS Cut Line= 4
     319851.7715    4050409.3446     319890.0719    4050554.3724
     319914.2879    4050646.0686     320032.5468    4050662.8149
#Sta/Elev= 30
       0  359.46      22  357.54      44  356.33      70  353.16   87.71   352.9
     126  353.44     142  352.67  145.23  351.22     148  349.97  153.95  348.13
  157.84  347.57  167.78  346.84  205.32  345.96  225.08  346.21  229.03  346.89
  234.68  348.87  247.42  351.24  254.79  353.68  262.76  355.34  270.72  355.96
  282.66  354.45  284.65  354.98  290.62  355.55  304.56  359.18  314.51  359.91
  328.45  358.79  342.38  356.85  348.35  355.51   360.3  355.29  364.28  355.75
#Mann= 4 ,-1 , 0
       0     .03       0   87.71     .16       0  157.84   .0463       0
  234.68     .16       0
Bank Sta=145.23,247.42
XS Rating Curve= 0 ,0
Exp/Cntr=0.3,0.1

Type RM Length L Ch R = 1 ,3643.689,39.95,39.84,39.84
XS GIS Cut Line= 4
     319787.2797    4050425.2006      319816.474    4050461.7289
     319835.9722    4050568.5346     319856.9908    4050683.6686
#Sta/Elev= 30
       0  359.82   11.69  358.67   46.76  356.54    74.4  352.95    87.9  352.76
  123.75  353.04  135.59  352.01  137.19  351.32  139.54  350.16  143.49  348.87
  151.38  348.39  153.36  347.83  157.54  348.15  175.49  348.06  179.14  347.72
  185.09  346.42  195.01  346.13  206.91  345.09  214.84  343.36  224.76  344.02
   232.7  346.47  236.92  348.21  238.65  349.72  241.52  351.22  246.58  354.52
  254.52  358.96  258.48  362.26  264.43  368.58   268.4  370.93  272.37  372.77
#Mann= 5 ,-1 , 0
       0     .03       0    87.9     .16       0  157.54      .1       0
  175.49   .0463       0  236.92     .16       0
Bank Sta=137.19,241.52
XS Rating Curve= 0 ,0
Exp/Cntr=0.3,0.1

Type RM Length L Ch R = 1 ,3603.849,52.59,49.8,50.38
XS GIS Cut Line= 5
      319762.478     4050445.651      319786.478    4050462.7566
     319785.2773    4050512.6773     319796.7898    4050575.7398
     319817.2549    4050687.8417
#Sta/Elev= 30
       0  356.99   17.68  355.86   29.47  355.86   59.43  352.81   72.84  352.53
   94.95   353.3  108.55  353.18  124.09  351.85  126.03  351.21  129.91  349.66
  137.68  347.78  141.57  347.44  145.33  347.87  147.51  348.48  153.51  348.14
  157.51  348.58  159.51  349.16  162.38  348.97   163.5  348.73   165.5  347.66
   173.5  345.38   183.5  344.73  193.49  344.77  197.49  345.41  209.49   345.7
  213.48   346.6  220.44  348.99  226.93   351.3  231.48  354.48  257.47  368.76
#Mann= 5 ,-1 , 0
       0     .03       0   72.84     .16       0  145.33      .1       0
  162.38   .0463       0  220.44     .16       0
Bank Sta=126.03,226.93
XS Rating Curve= 0 ,0
Exp/Cntr=0.3,0.1

Type RM Length L Ch R = 1 ,3554.046,27.87,48.27,66.62
XS GIS Cut Line= 6
     319740.5663    4050466.0877     319733.6833    4050497.8211
      319733.427    4050536.4477     319748.4031    4050584.5456
     319765.1369    4050683.1355     319767.6532    4050697.9607
#Sta/Elev= 30
       0  355.96   24.83  352.94   36.33  352.36   44.68  352.42   67.24  353.15
   76.91  353.11    86.6  353.41   94.35  353.26   102.1  352.64  104.04  351.99
  105.78  351.15  109.85  349.27  115.66  347.92   117.6  347.69  127.47  348.04
  129.91  347.78  132.24   347.6  141.47  346.29  165.47  345.73  173.47  346.27
  179.47  346.19  183.47  346.36  197.47  348.49  201.36  348.64  203.47  349.66
     206  351.16  213.47  355.46  219.47  358.07  232.75  363.05  236.51  364.19
#Mann= 5 ,-1 , 0
       0     .03       0   44.68     .16       0  129.91      .1       0
  132.24   .0463       0  201.36     .16       0
Bank Sta=105.78,206
XS Rating Curve= 0 ,0
Exp/Cntr=0.3,0.1

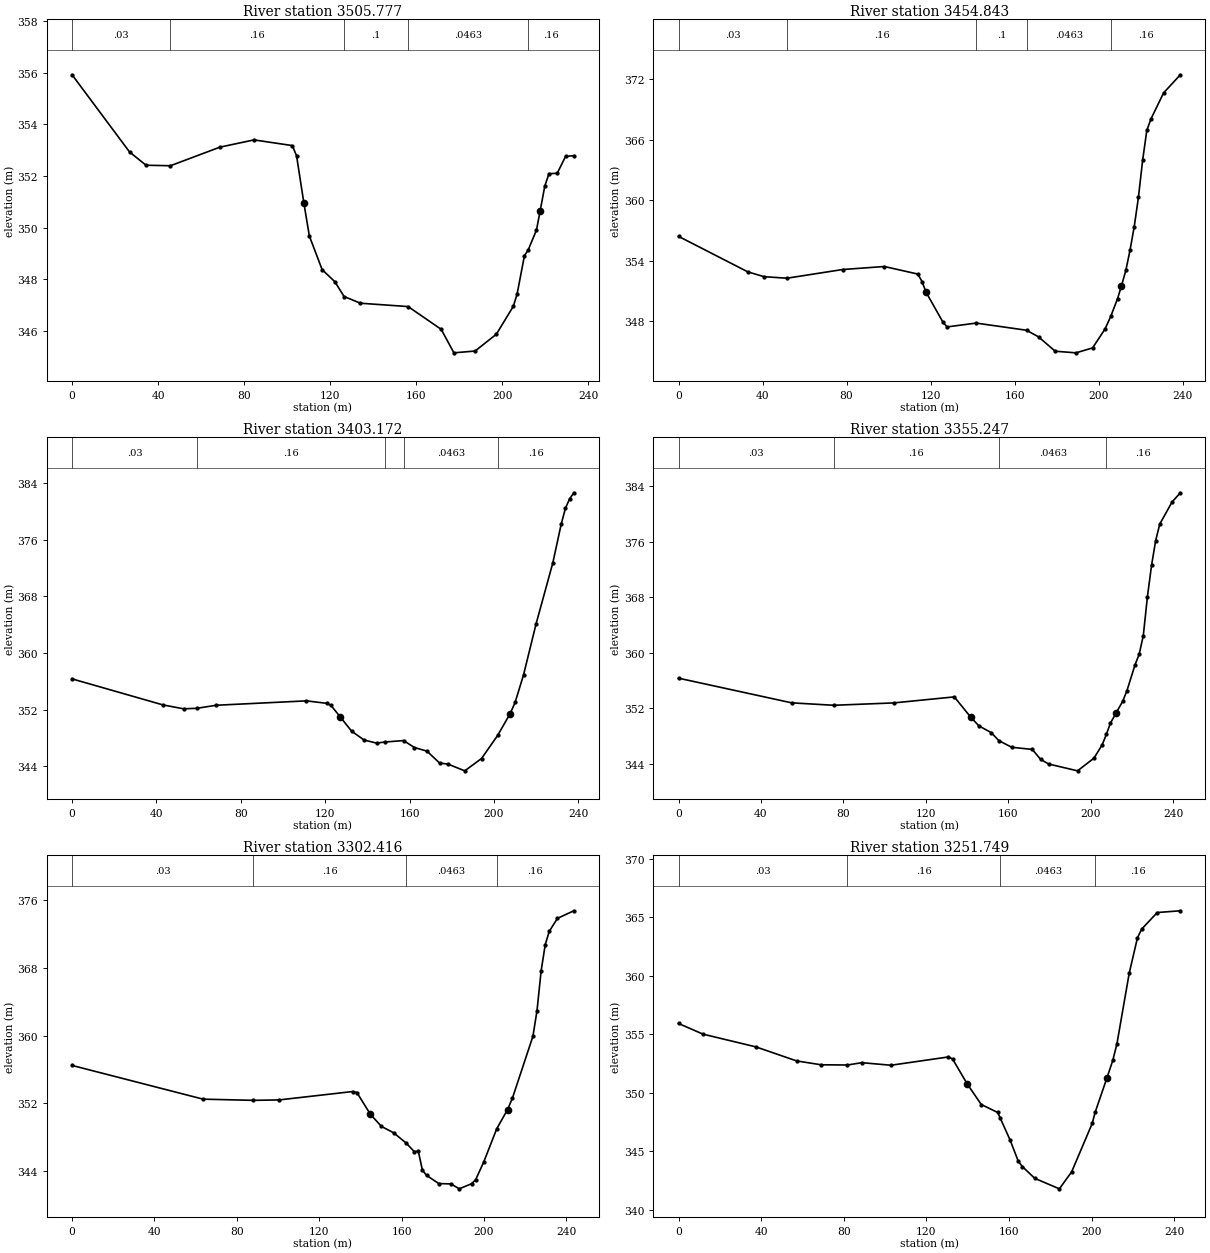
Type RM Length L Ch R = 1 ,3505.777,29.63,50.93,52.42
XS GIS Cut Line= 6
     319722.9439    4050463.1834     319714.2927    4050496.4799
     319715.0937    4050526.8719     319709.0757    4050667.0516
       319703.63     4050671.307     319693.9375    4050690.2194
#Sta/Elev= 30
       0  355.92   26.76  352.93    34.4  352.42   45.74   352.4   68.77  353.12
   84.61   353.4  102.43  353.18  104.41  352.78  107.79  350.96  110.35  349.68
  116.29  348.38  122.23  347.91  126.49  347.34  134.12  347.08  156.28  346.95
  171.65  346.07  177.57  345.16  187.43  345.23   197.3  345.88  205.19  346.96
  206.92  347.42  210.37  348.92   212.1  349.14  215.96  349.91  217.67  350.65
  219.83  351.61  221.76  352.09  225.62  352.11  229.49  352.76  233.35  352.79
#Mann= 5 ,-1 , 0
       0     .03       0   45.74     .16       0  126.49      .1       0
  156.28   .0463       0   212.1     .16       0
Bank Sta=107.79,217.67
XS Rating Curve= 0 ,0
Exp/Cntr=0.3,0.1

Type RM Length L Ch R = 1 ,3454.843,47.55,51.67,53.98
XS GIS Cut Line= 6
      319709.207    4050456.3079     319695.3164     4050496.657
     319696.3082    4050526.0918     319675.0953    4050588.2779
     319651.4717    4050657.5312     319642.5664    4050684.0017
#Sta/Elev= 30
       0  356.43   32.97  352.91   40.73  352.43   51.62  352.28    78.1  353.14
   98.01  353.44  113.94  352.69  115.93  351.95  117.88  350.88  125.88  347.93
  127.87  347.45   141.7  347.83   165.7  347.12  171.45  346.46  179.36  345.04
  189.25  344.88  197.16  345.37  203.09  347.25  205.79  348.49  209.02  350.24
   210.9  351.52     213  353.07  214.99  355.07  216.99   357.4  218.98   360.3
  220.98  363.97  222.97  366.93  224.97  368.08  230.95  370.65  238.93  372.45
#Mann= 5 ,-1 , 0
       0     .03       0   51.62     .16       0   141.7      .1       0
   165.7   .0463       0  205.79     .16       0
Bank Sta=117.88,210.9
XS Rating Curve= 0 ,0
Exp/Cntr=0.3,0.1

Type RM Length L Ch R = 1 ,3403.172,48.14,47.92,48.07
XS GIS Cut Line= 5
     319676.3162    4050445.5927     319657.4279    4050492.8681
     319656.4585    4050510.2555      319630.456    4050571.0264
     319589.7533    4050666.1535
#Sta/Elev= 30
       0  356.35   43.08  352.68   52.84  352.13   59.15   352.2   68.32  352.63
  111.09  353.25  120.81   352.9  122.76   352.6  127.21  350.96  132.48  348.99
   138.4  347.73  144.37  347.29  148.14  347.44  157.18  347.65  162.28  346.67
  168.25  346.16  174.22  344.48   178.2  344.33  186.16  343.38  194.12  345.12
  201.77  348.38  207.68  351.45  210.04  353.03  214.02   356.9  219.98  364.11
  227.94  372.74  231.92  378.22  233.91  380.43   235.9  381.76  237.89   382.6
#Mann= 5 ,-1 , 0
       0     .03       0   59.15     .16       0  148.14      .1       0
  157.18   .0463       0  201.77     .16       0
Bank Sta=127.21,207.68
XS Rating Curve= 0 ,0
Exp/Cntr=0.3,0.1

Type RM Length L Ch R = 1 ,3355.247,54.16,52.83,52.17
XS GIS Cut Line= 5
     319631.3389     4050425.065     319606.6334    4050484.8609
     319604.1327      4050510.72     319586.4121    4050552.1352
     319544.0408    4050651.1619
#Sta/Elev= 30
       0  356.34    54.9  352.78   75.29  352.43  104.39  352.77  133.77  353.64
  141.78  350.71   145.7  349.46  151.68  348.49   155.4  347.33  161.66  346.37
  171.63  346.06  175.62  344.63  179.61  343.95  193.57  342.97  201.55   344.8
  205.54  346.73  207.62  348.28  209.53  349.85   212.3  351.33  215.51  353.02
  217.51  354.51   221.5   358.3  223.49   359.8  225.48  362.49  227.48  368.11
  229.47   372.6  231.47  376.18  233.46  378.57  239.45  381.77  243.44  383.09
#Mann= 4 ,-1 , 0
       0     .03       0   75.29     .16       0   155.4   .0463       0
  207.62     .16       0
Bank Sta=141.78,212.3
XS Rating Curve= 0 ,0
Exp/Cntr=0.3,0.1

Type RM Length L Ch R = 1 ,3302.416,50.67,50.67,50.67
XS GIS Cut Line= 4
      319585.983    4050409.5122     319552.5564     4050483.837
     319549.9534    4050498.6644     319494.8524    4050635.0074
#Sta/Elev= 30
       0  356.48   63.61  352.51   87.94  352.37  100.52  352.42  136.29  353.41
  138.28  353.29  144.84  350.72  150.21   349.3  156.17  348.54  162.29  347.32
   166.1  346.34  168.09  346.38  170.08  344.15  172.07  343.54  178.03  342.57
  183.99  342.53  187.96  341.95  193.92  342.55  195.91  343.01  199.89  345.13
  206.18  349.03  211.44  351.29   213.8  352.64  223.73  359.91  225.72  362.93
  227.71  367.59   229.7  370.69  231.68  372.28  235.66   373.8  243.61  374.69
#Mann= 4 ,-1 , 0
       0     .03       0   87.94     .16       0  162.29   .0463       0
  206.18     .16       0
Bank Sta=144.84,211.44
XS Rating Curve= 0 ,0
Exp/Cntr=0.3,0.1

Type RM Length L Ch R = 1 ,3251.749,46.85,50.25,52.4
XS GIS Cut Line= 5
     319536.0694    4050397.7958     319508.7342    4050484.2603
     319498.4863    4050490.7921     319452.2697    4050605.1513
     319445.9772    4050620.7217
#Sta/Elev= 30
       0  355.91   11.83     355   37.46  353.91   57.17  352.71      69  352.38
   81.81  352.36   88.71  352.56  102.84  352.34  130.69  353.05  132.68  352.88
  139.88  350.71   146.6  348.98  154.56   348.3  155.74  347.83  160.53  345.95
  164.51  344.13   166.5  343.67  172.47  342.67   184.4  341.77  190.37  343.23
  200.32  347.37  201.73  348.32  207.46  351.27  210.26  352.75  212.25  354.15
  218.22  360.21   222.2  363.23  224.19  363.97  231.78   365.4  242.97  365.55
#Mann= 4 ,-1 , 0
       0     .03       0   81.81     .16       0  155.74   .0463       0
  201.73     .16       0
Bank Sta=139.88,207.46
XS Rating Curve= 0 ,0
Exp/Cntr=0.3,0.1

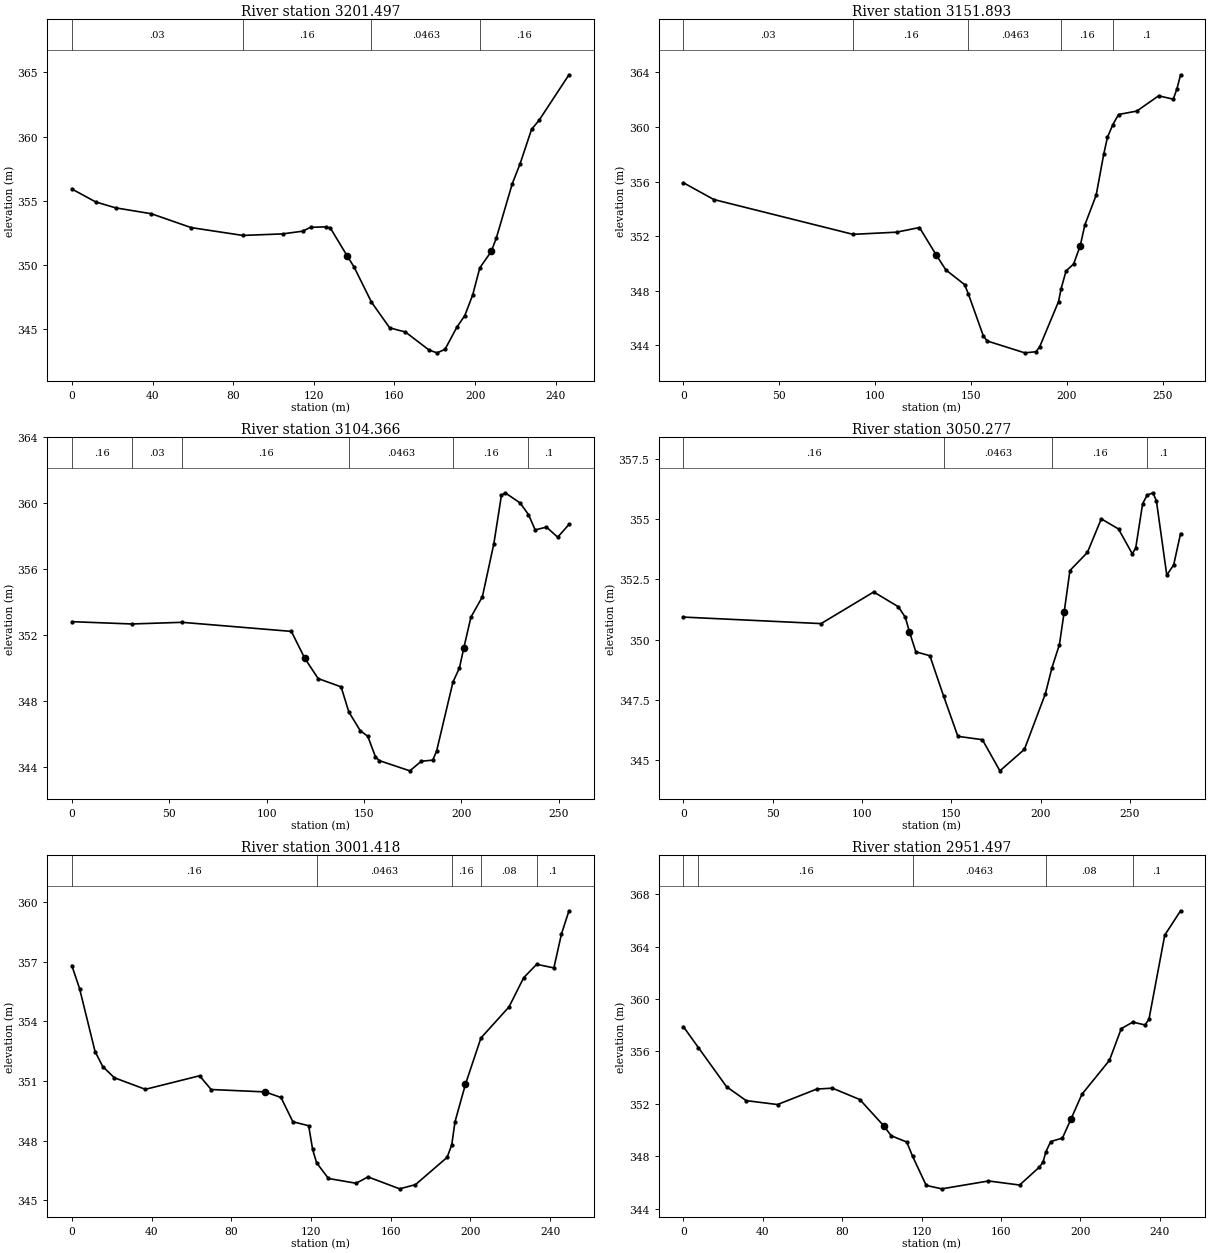
Type RM Length L Ch R = 1 ,3201.497,49.7,49.6,49.62
XS GIS Cut Line= 4
     319499.1396    4050381.7339     319446.0596    4050494.0925
     319403.3446    4050584.5106     319393.8387    4050604.6324
#Sta/Elev= 30
       0  355.92   11.83  354.91    21.7  354.45   39.45  353.99   59.17  352.91
   84.78   352.3  104.54  352.42   114.4  352.63  118.35  352.93  126.23  352.97
  128.19  352.88  136.55   350.7  139.95  349.84  148.59   347.1   157.6   345.1
  165.44  344.77  177.21  343.36  181.13  343.15  185.05  343.42  190.93  345.15
  194.85  346.05  198.78  347.66  202.29  349.77  207.99  351.05  210.54  352.12
  218.38  356.32   222.3  357.89  227.97  360.57  231.68  361.27  246.52  364.82
#Mann= 4 ,-1 , 0
       0     .03       0   84.78     .16       0  148.59   .0463       0
  202.29     .16       0
Bank Sta=136.55,207.99
XS Rating Curve= 0 ,0
Exp/Cntr=0.3,0.1

Type RM Length L Ch R = 1 ,3151.893,47.69,47.53,47.54
XS GIS Cut Line= 4
     319453.8122    4050361.5539      319401.229    4050472.8609
      319358.514     4050563.279     319343.0635    4050595.9842
#Sta/Elev= 30
       0  355.92   15.88  354.69   88.46  352.14  111.19   352.3   123.1  352.64
  131.84  350.63  136.83  349.54  146.63  348.46  148.61  347.77  156.44  344.69
   158.4  344.33     178  343.46  183.89  343.54  185.85  343.92  195.65  347.22
  196.99  348.17  199.57  349.46  203.49  349.97   206.9  351.28  209.38  352.84
  215.26  355.01  219.18     358  221.14  359.25  223.97  360.18  226.91  360.92
  236.43  361.17  247.85  362.29  255.47  362.04  257.37   362.8  259.27  363.83
#Mann= 5 ,-1 , 0
       0     .03       0   88.46     .16       0  148.61   .0463       0
  196.99     .16       0  223.97      .1       0
Bank Sta=131.84,206.9
XS Rating Curve= 0 ,0
Exp/Cntr=0.3,0.1

Type RM Length L Ch R = 1 ,3104.366,48.71,54.09,57.46
XS GIS Cut Line= 4
      319408.478    4050345.0518     319358.2559    4050452.5597
     319315.5409    4050542.9778     319299.8982    4050576.0899
#Sta/Elev= 30
       0  352.82   30.77  352.68   56.62  352.78  112.73  352.23  119.61   350.6
   126.5  349.37  138.27  348.87  142.23  347.35  148.07  346.22  151.99  345.87
  155.91  344.63  157.88   344.4  173.56  343.78  179.44  344.36  185.33  344.43
  187.29  344.97  195.71  349.16  199.05  350.02  201.28  351.23  204.93  353.09
  210.82  354.33   216.7  357.54  220.59  360.47  222.51  360.63  230.22  360.01
  234.49  359.31  237.93  358.38  243.72  358.55   249.5  357.94  255.28  358.71
#Mann= 6 ,-1 , 0
       0     .16       0   30.77     .03       0   56.62     .16       0
  142.23   .0463       0  195.71     .16       0  234.49      .1       0
Bank Sta=119.61,201.28
XS Rating Curve= 0 ,0
Exp/Cntr=0.3,0.1

Type RM Length L Ch R = 1 ,3050.277,51.37,48.86,49.09
XS GIS Cut Line= 6
     319361.9565    4050327.1648      319329.907     4050356.206
     319342.8556    4050378.6857     319313.5532    4050429.8814
     319263.8782    4050516.6708     319222.8484    4050545.5577
#Sta/Elev= 30
       0  350.93   77.06  350.66  106.55  351.97  120.32  351.36  124.25  350.92
  126.54  350.32  130.14  349.49  137.98  349.33  145.76  347.64  153.67  345.99
   167.4  345.85   177.2  344.56  190.93  345.45  202.69  347.76  206.38  348.84
  210.53  349.79  213.19  351.14  216.42  352.86  226.22  353.61  233.97     355
  243.62  354.58  251.34  353.55  253.27   353.8  257.13  355.63  259.65  355.98
  262.92  356.08  264.85  355.74  270.64  352.67   274.5  353.09  278.36  354.39
#Mann= 4 ,-1 , 0
       0     .16       0  145.76   .0463       0  206.38     .16       0
  259.65      .1       0
Bank Sta=126.54,213.19
XS Rating Curve= 0 ,0
Exp/Cntr=0.3,0.1

Type RM Length L Ch R = 1 ,3001.418,47.54,49.92,50.15
XS GIS Cut Line= 6
     319324.2646    4050312.8093     319282.8286    4050361.6974
     319277.6681    4050394.2201     319221.4792    4050492.3904
     319207.3586    4050501.1674     319203.6342    4050523.5684
#Sta/Elev= 30
       0   356.8    3.88  355.64   11.65  352.48   15.54  351.72   21.36  351.16
    36.9  350.58   64.09  351.26    69.9  350.57   97.02  350.45  104.95  350.17
  110.91  348.95  118.84  348.75  120.83  347.56  122.81  346.89  128.77   346.1
  142.66  345.86  148.61  346.18  164.49  345.58  172.42  345.79   188.3  347.16
  190.64  347.79  192.27  348.95  197.53  350.84  205.29  353.16  219.37  354.72
  226.75  356.19  233.26  356.86  241.89  356.68  245.68  358.38  249.46  359.55
#Mann= 5 ,-1 , 0
       0     .16       0  122.81   .0463       0  190.64     .16       0
  205.29     .08       0  233.26      .1       0
Bank Sta=97.02,197.53
XS Rating Curve= 0 ,0
Exp/Cntr=0.3,0.1

Type RM Length L Ch R = 1 ,2951.497,52.02,51.67,51.91
XS GIS Cut Line= 4
     319279.8315    4050289.9456     319227.8283    4050380.8029
     319178.1533    4050467.5923     319155.4066    4050507.3343
#Sta/Elev= 30
       0  357.89    7.56  356.29   21.73  353.31    31.6  352.25   47.41  351.95
   67.16  353.13   75.06   353.2   88.89  352.33  100.85  350.34  104.69  349.57
  112.53  349.09  115.47     348  122.33  345.78  130.18  345.52  153.71  346.12
  169.39  345.81   179.2  347.16  181.16  347.54  182.61  348.34  185.08  349.13
  190.96  349.39  195.23  350.83  200.77  352.73  214.64  355.32  220.61  357.74
  226.44  358.24  232.56  358.02  234.55  358.45  242.51  364.87  250.48  366.73
#Mann= 5 ,-1 , 0
       0     .03       0    7.56     .16       0  115.47   .0463       0
  182.61     .08       0  226.44      .1       0
Bank Sta=100.85,195.23
XS Rating Curve= 0 ,0
Exp/Cntr=0.3,0.1

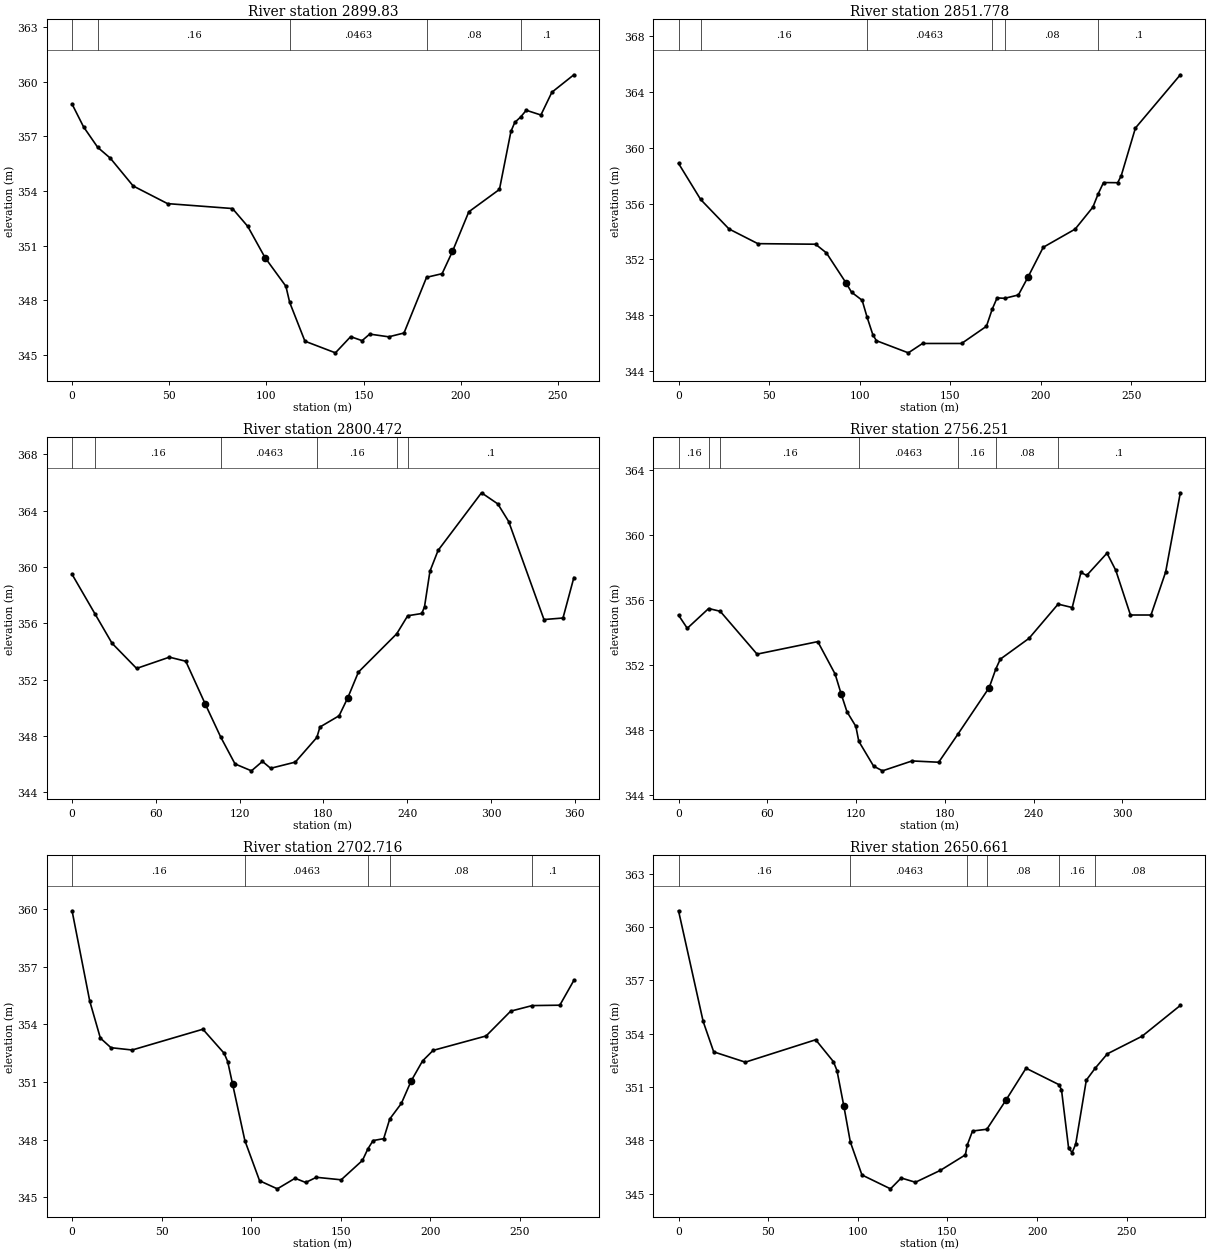
Type RM Length L Ch R = 1 ,2899.83 ,54.58,48.05,43.43
XS GIS Cut Line= 5
     319232.7725    4050268.1537     319182.9865    4050355.1372
     319133.3115    4050441.9266     319116.6712    4050470.9997
      319110.478    4050494.7036
#Sta/Elev= 30
       0  358.78     5.9  357.53   13.21   356.4   19.65  355.81   31.44  354.28
   49.13  353.31   82.54  353.04    90.4  352.06   99.32  350.34  110.03  348.77
  111.99  347.88  119.83  345.75  135.52  345.11  143.36     346  149.24  345.78
  153.16  346.14  162.97  345.99  170.81   346.2  182.42  349.26  190.42  349.46
  195.74  350.68  204.16  352.86  219.93  354.09  225.84  357.28  227.81  357.77
  230.84  358.07  233.72  358.44  241.26  358.18  246.91  359.43  258.22  360.39
#Mann= 5 ,-1 , 0
       0     .03       0   13.21     .16       0  111.99   .0463       0
  182.42     .08       0  230.84      .1       0
Bank Sta=99.32,195.74
XS Rating Curve= 0 ,0
Exp/Cntr=0.3,0.1

Type RM Length L Ch R = 1 ,2851.778,51.31,51.31,49.47
XS GIS Cut Line= 5
     319172.3017    4050246.4891     319135.6531    4050330.4279
     319095.6397    4050422.0736      319060.478    4050476.2687
     319062.9214    4050497.0106
#Sta/Elev= 30
       0  358.87   12.21  356.29   27.88  354.18    43.8  353.13   75.66  353.09
   81.64  352.47    92.5  350.32   95.51  349.66  101.39  349.08  104.07  347.89
  107.28  346.62  109.24  346.19  126.88  345.32  134.73  345.99   156.3  345.99
  170.02  347.22  173.22  348.45   175.9  349.25  180.09  349.22  187.67  349.46
  192.85  350.71  201.38  352.87     219  354.17  228.79  355.74  231.68  356.68
  234.66   357.5  242.49  357.49  244.45  357.99  252.28   361.4  277.08  365.21
#Mann= 6 ,-1 , 0
       0     .03       0   12.21     .16       0  104.07   .0463       0
  173.22     .16       0  180.09     .08       0  231.68      .1       0
Bank Sta=92.5,192.85
XS Rating Curve= 0 ,0
Exp/Cntr=0.3,0.1

Type RM Length L Ch R = 1 ,2800.472,44.29,44.22,44.22
XS GIS Cut Line= 6
     319115.4442      4050220.86     319116.7445    4050245.5142
     319088.5703    4050310.0436     319029.5432    4050445.2378
     318989.6214    4050476.1835     318923.8778    4050483.2626
#Sta/Elev= 30
       0  359.47    16.6  356.63    28.6  354.58    46.2  352.79   69.67  353.59
   81.41   353.3   95.27  350.28  106.36  347.93  116.67  346.01  128.43  345.52
  136.28  346.19  142.16   345.7  159.81  346.14  175.25  347.89  177.45  348.63
  191.18  349.43  197.41  350.71     205  352.53  232.43  355.25   240.3  356.53
  250.39  356.69  252.33  357.17  256.22  359.69  262.05  361.17  293.13  365.26
   304.8  364.47  312.58  363.22  337.86  356.26  351.47  356.37  359.25  359.24
#Mann= 6 ,-1 , 0
       0     .03       0    16.6     .16       0  106.36   .0463       0
  175.25     .16       0  232.43     .08       0   240.3      .1       0
Bank Sta=95.27,197.41
XS Rating Curve= 0 ,0
Exp/Cntr=0.3,0.1

Type RM Length L Ch R = 1 ,2756.251,53.65,53.53,57.4
XS GIS Cut Line= 6
       319068.84     4050192.048     319073.9231    4050233.0765
     319008.0938    4050383.8501     318989.4643    4050426.5185
     318964.8828    4050454.4528     318915.3191    4050455.2069
#Sta/Elev= 30
       0  355.07    5.91  354.26   20.35  355.48   28.16  355.31   53.07  352.67
   94.13  353.44  105.86  351.44  109.96  350.21  113.86  349.12  119.86  348.22
  121.85   347.3  131.86  345.77  137.86  345.48  157.86  346.09  175.86  346.01
   188.7  347.72  210.01  350.61  214.49  351.76   217.5  352.36   236.9  353.64
  256.58  355.75  266.13  355.54     272   357.7  275.92  357.52  289.63  358.89
  295.58  357.83  305.49  355.08  319.37  355.08  329.28  357.73   339.2  362.61
#Mann= 7 ,-1 , 0
       0     .16       0   20.35     .03       0   28.16     .16       0
  121.85   .0463       0   188.7     .16       0  214.49     .08       0
  256.58      .1       0
Bank Sta=109.96,210.01
XS Rating Curve= 0 ,0
Exp/Cntr=0.3,0.1

Type RM Length L Ch R = 1 ,2702.716,47.73,52.06,57.4
XS GIS Cut Line= 5
     319031.4181    4050196.6362     318999.0447    4050270.7833
     318964.9818    4050348.8001     318930.9907    4050404.2458
     318882.6555    4050412.2255
#Sta/Elev= 30
       0  359.91    9.87  355.21   15.79  353.29   21.71  352.79   33.55  352.67
   73.01  353.75   84.87   352.5   86.85  352.07   89.58   350.9   96.44  347.96
  104.66  345.87  114.56  345.45  124.46     346   130.4  345.78  136.34  346.05
   150.2  345.92  162.08  346.93  165.11  347.53  168.01  347.96  173.92  348.06
  177.29  349.08  183.77  349.89  189.31  351.07   195.6   352.1  201.51  352.65
  231.07   353.4  244.79  354.69  256.81  354.98  272.22     355  280.06  356.29
#Mann= 5 ,-1 , 0
       0     .16       0   96.44   .0463       0  165.11     .16       0
  177.29     .08       0  256.81      .1       0
Bank Sta=89.58,189.31
XS Rating Curve= 0 ,0
Exp/Cntr=0.3,0.1

Type RM Length L Ch R = 1 ,2650.661,48.33,48.33,53.76
XS GIS Cut Line= 5
      318994.451    4050180.7748     318955.7425    4050251.2559
     318901.1611    4050350.6387     318861.7282    4050347.2982
     318823.0923    4050373.1647
#Sta/Elev= 30
       0  360.91   13.73  354.69   19.61  352.98   37.26   352.4   76.49  353.66
   86.38  352.43   88.37  351.93    92.2  349.93    95.8  347.92  102.29  346.06
  118.21  345.28  124.17  345.89  132.13  345.65  146.05  346.32  159.98  347.19
  161.02  347.74  163.96  348.53  171.96  348.63  182.63  350.27   193.8  352.06
   212.1  351.14  213.58  350.85  217.54  347.58  219.52  347.32   221.5  347.79
  227.43  351.39  232.29  352.05  239.18  352.87  258.55  353.86  279.86  355.59
#Mann= 6 ,-1 , 0
       0     .16       0    95.8   .0463       0  161.02     .16       0
  171.96     .08       0   212.1     .16       0  232.29     .08       0
Bank Sta=92.2,182.63
XS Rating Curve= 0 ,0
Exp/Cntr=0.3,0.1

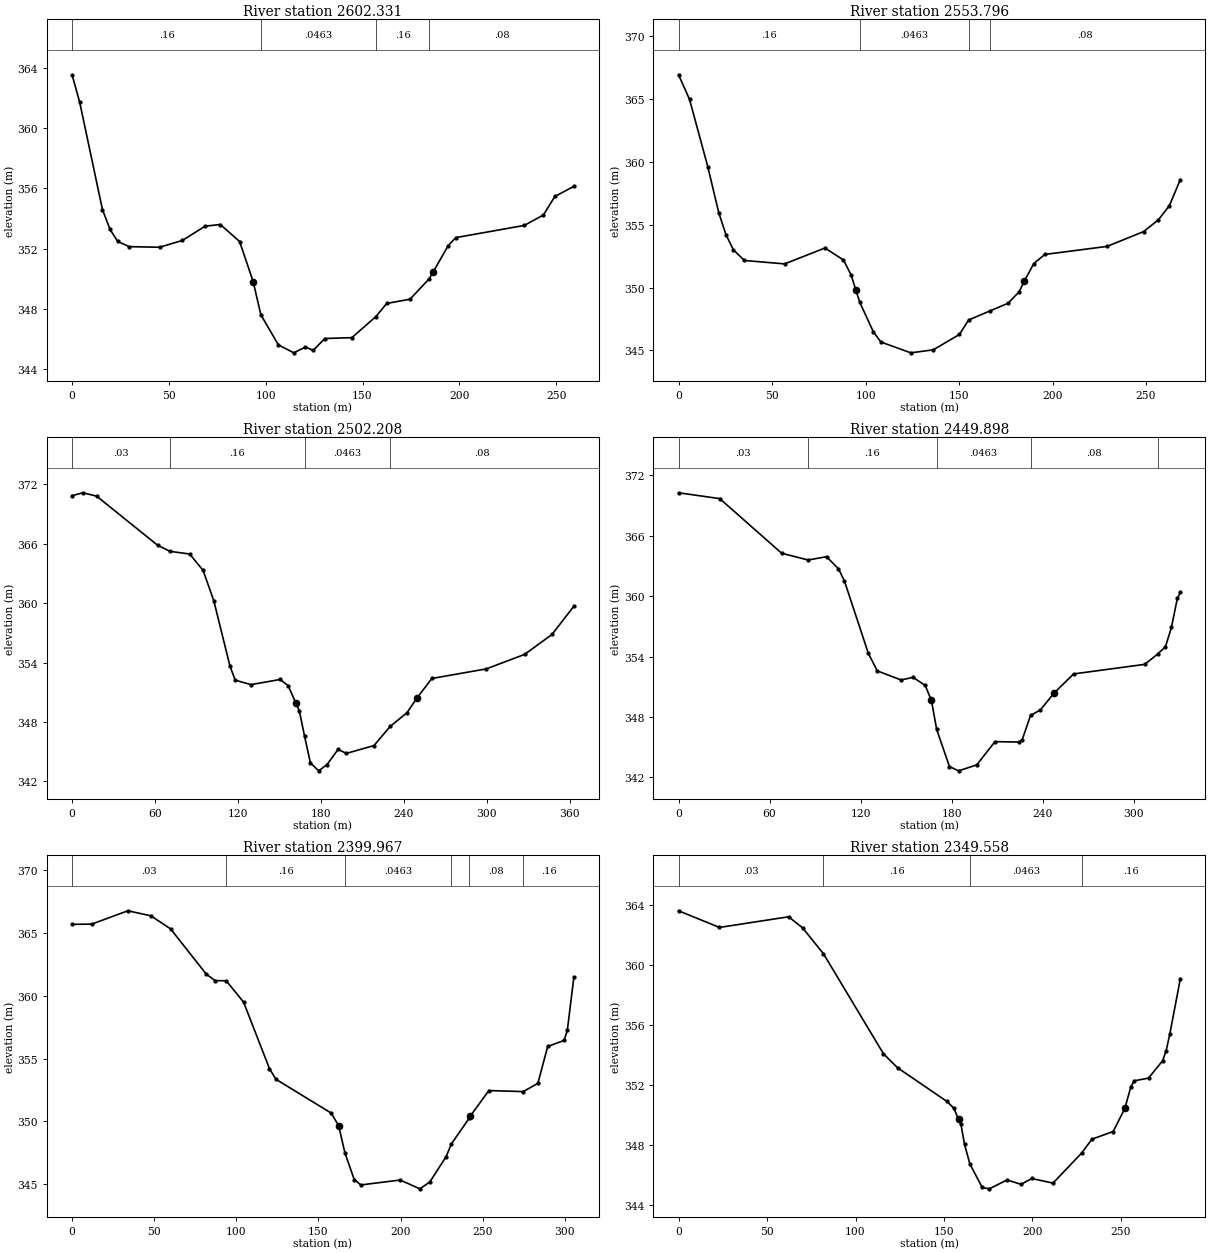
Type RM Length L Ch R = 1 ,2602.331,44.95,48.53,51.93
XS GIS Cut Line= 4
      318951.185    4050159.1563     318913.3808    4050227.9908
     318865.2426    4050315.6418     318795.1189    4050355.4071
#Sta/Elev= 30
       0  363.54    3.93  361.72   15.71  354.58   19.63  353.27   23.56  352.48
   29.45  352.13   45.16  352.09   56.94  352.54   68.72  353.49   76.57   353.6
   86.53  352.47   93.53  349.81   97.49  347.61  106.53  345.61  114.53  345.08
  120.53  345.47  124.53  345.24  130.53  346.03  144.53  346.09  156.93  347.49
  162.53  348.36  174.53  348.64   184.4  349.99  186.44  350.44  194.26   352.2
  198.19  352.73  233.59  353.54  243.42  354.23  249.32  355.46  259.15  356.13
#Mann= 4 ,-1 , 0
       0     .16       0   97.49   .0463       0  156.93     .16       0
   184.4     .08       0
Bank Sta=93.53,186.44
XS Rating Curve= 0 ,0
Exp/Cntr=0.3,0.1

Type RM Length L Ch R = 1 ,2553.796,47.38,51.59,52.86
XS GIS Cut Line= 4
     318918.3744    4050138.0873      318874.685      4050205.37
     318820.2251    4050289.2396      318741.843    4050329.5272
#Sta/Elev= 30
       0  366.91    5.87  364.96   15.65   359.6   21.52  355.94   25.44  354.17
   29.35     353   35.22  352.15   56.74  351.88   78.27  353.14   88.22  352.19
   92.22  351.02   94.89  349.77   96.94  348.82  104.22  346.47  108.22  345.67
  124.22  344.81  136.22  345.05  150.22  346.27  155.13  347.42  166.38  348.13
  176.22  348.75  182.18  349.67  184.93  350.51  190.01  351.91  195.89  352.63
  229.18  353.27  248.77  354.45   256.6  355.38  262.48   356.5  268.35  358.58
#Mann= 4 ,-1 , 0
       0     .16       0   96.94   .0463       0  155.13     .16       0
  166.38     .08       0
Bank Sta=94.89,184.93
XS Rating Curve= 0 ,0
Exp/Cntr=0.3,0.1

Type RM Length L Ch R = 1 ,2502.208,41.25,52.31,70.71
XS GIS Cut Line= 6
     318927.7726    4050060.8062     318904.7116    4050095.3072
     318851.8902    4050146.9689     318773.7739    4050258.1385
     318724.9338    4050287.9253      318673.013    4050275.3072
#Sta/Elev= 30
       0  370.84     7.9  371.13   17.79  370.79   61.84  365.84   70.86  365.22
   85.11  364.95    94.8   363.3  102.55  360.24  114.18  353.68  118.04  352.22
  129.51  351.77  150.55  352.29  156.47  351.65  162.01  349.87  164.47  349.12
  168.27  346.54  172.47  343.87  178.47  343.07  184.47   343.7  192.47  345.23
  198.47  344.83  218.47  345.62  230.19  347.55  242.47  348.95   249.4  350.39
  260.36  352.39  299.81  353.36  327.48  354.82  347.27  356.83  363.11  359.68
#Mann= 4 ,-1 , 0
       0     .03       0   70.86     .16       0  168.27   .0463       0
  230.19     .08       0
Bank Sta=162.01,249.4
XS Rating Curve= 0 ,0
Exp/Cntr=0.3,0.1

Type RM Length L Ch R = 1 ,2449.898,45.05,49.93,56.51
XS GIS Cut Line= 6
     318923.5062     4050056.581     318869.4264    4050087.0996
     318813.1538    4050136.4338     318806.6824    4050150.6671
     318728.7998    4050213.3911     318651.2398    4050223.2862
#Sta/Elev= 30
       0  370.28   27.17   369.7      68  364.27   85.42   363.6   97.55  363.93
  105.42  362.73  109.36  361.51  125.12  354.32  131.02  352.58  146.71  351.68
  154.57  351.94  162.57  351.14  166.69  349.65  170.16  346.76  178.57  343.08
  184.57  342.65  196.57  343.24  208.57  345.55  224.57  345.51  226.57  345.76
  232.02  348.15  238.57  348.71  247.59  350.39  260.39  352.28   307.3  353.23
  315.79  354.25  320.98  354.99  324.89   356.9   328.8  359.78  330.76   360.4
#Mann= 5 ,-1 , 0
       0     .03       0   85.42     .16       0  170.16   .0463       0
  232.02     .08       0  315.79     .16       0
Bank Sta=166.69,247.59
XS Rating Curve= 0 ,0
Exp/Cntr=0.3,0.1

Type RM Length L Ch R = 1 ,2399.967,44.95,50.41,50.66
XS GIS Cut Line= 6
      318892.478    4050027.8745     318827.8978     4050071.571
     318824.7173    4050085.8502     318780.0808     4050114.748
      318696.137    4050169.0935     318637.2737    4050179.2523
#Sta/Elev= 30
       0  365.69      12  365.71   33.99  366.77   47.98  366.37   59.98  365.33
   81.63  361.74   87.12  361.21   93.86   361.2  104.42   359.5  120.18  354.21
  124.11  353.36  157.78  350.67  162.35  349.65  166.08  347.52  171.78  345.38
  175.78  344.95  199.78  345.34  211.78  344.64  217.78  345.18  227.78  347.21
  230.91  348.21  241.73  350.25  242.34  350.41  253.74  352.46  274.72  352.38
  283.61  353.04  289.58  355.97  299.54  356.45  301.53  357.25  305.51  361.48
#Mann= 6 ,-1 , 0
       0     .03       0   93.86     .16       0  166.08   .0463       0
  230.91     .16       0  241.73     .08       0  274.72     .16       0
Bank Sta=162.35,242.34
XS Rating Curve= 0 ,0
Exp/Cntr=0.3,0.1

Type RM Length L Ch R = 1 ,2349.558,48.63,48.6,49.12
XS GIS Cut Line= 5
     318880.1432    4050003.2819     318844.9899    4050033.3978
     318755.9173    4050077.2943     318666.2184    4050121.4994
     318632.1909    4050138.2687
#Sta/Elev= 30
       0   363.6   23.14  362.49   62.18   363.2   70.12  362.46   81.88  360.74
   115.8  354.07  123.74  353.14  151.59   350.9  155.59  350.44  158.19   349.7
  159.59  349.36  161.59  348.04  164.58  346.74  171.59  345.16  175.59  345.07
  185.59  345.66  193.59  345.37  199.59  345.76  211.59  345.45   227.8  347.46
  233.59  348.38  245.59  348.89   252.2  350.43  255.57  351.87  257.57  352.27
  265.56  352.45  273.54  353.61  275.54  354.28  277.54  355.36  283.53  359.07
#Mann= 4 ,-1 , 0
       0     .03       0   81.88     .16       0  164.58   .0463       0
   227.8     .16       0
Bank Sta=158.19,252.2
XS Rating Curve= 0 ,0
Exp/Cntr=0.3,0.1