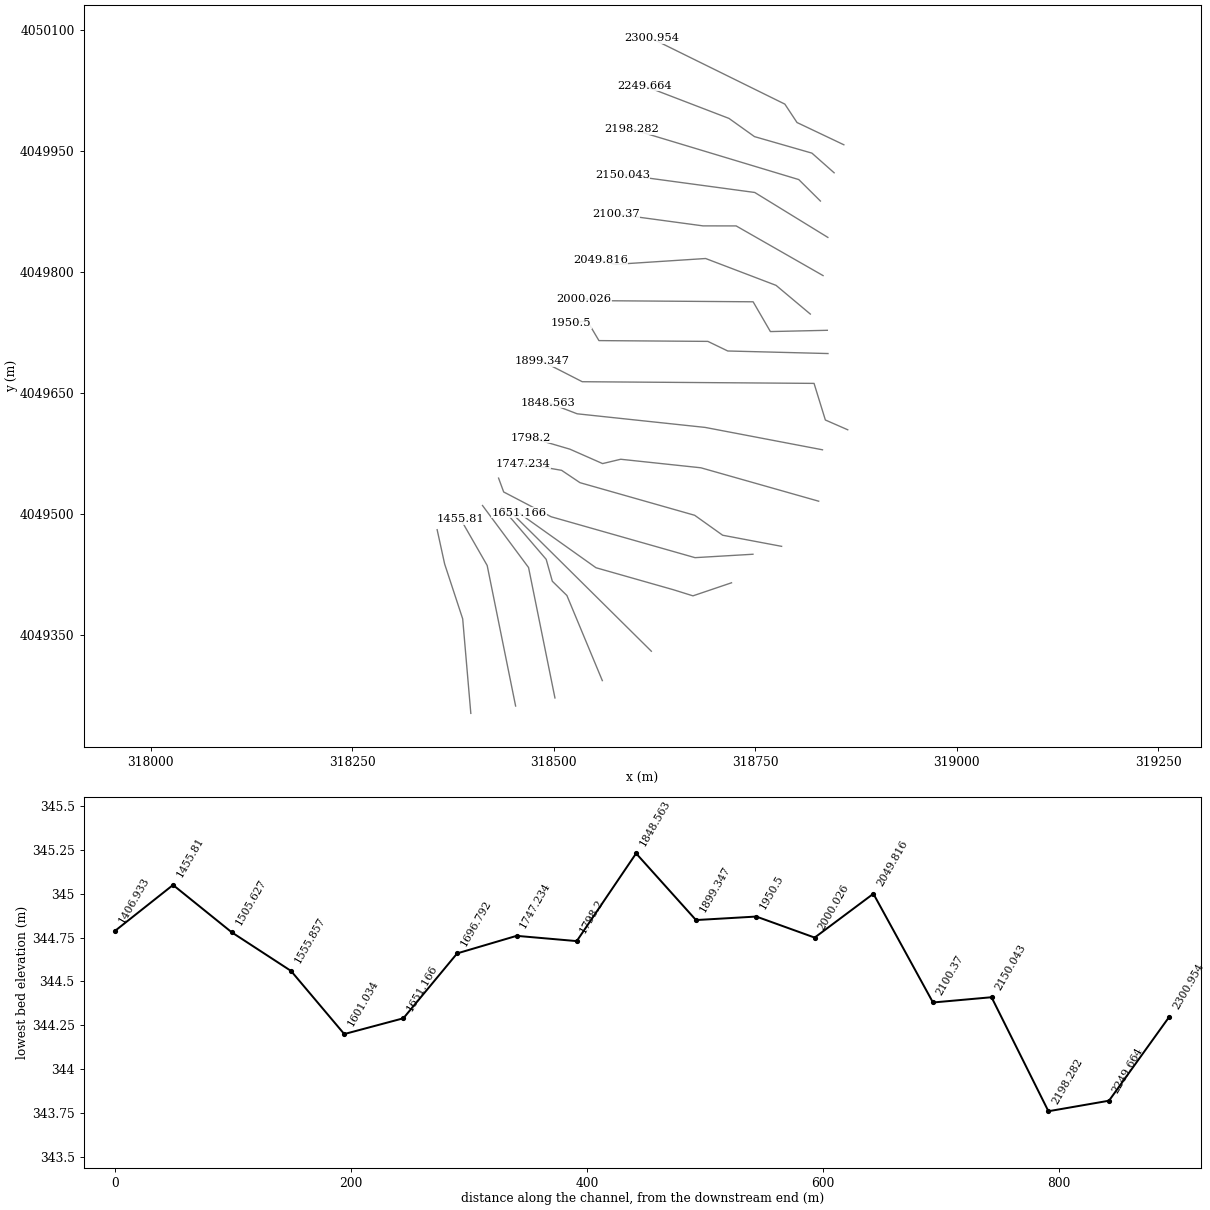
HEC-RAS study WBmod1D.prj: WBmod1D

--- WBmod1D.g03 (geometry) --- (continued)

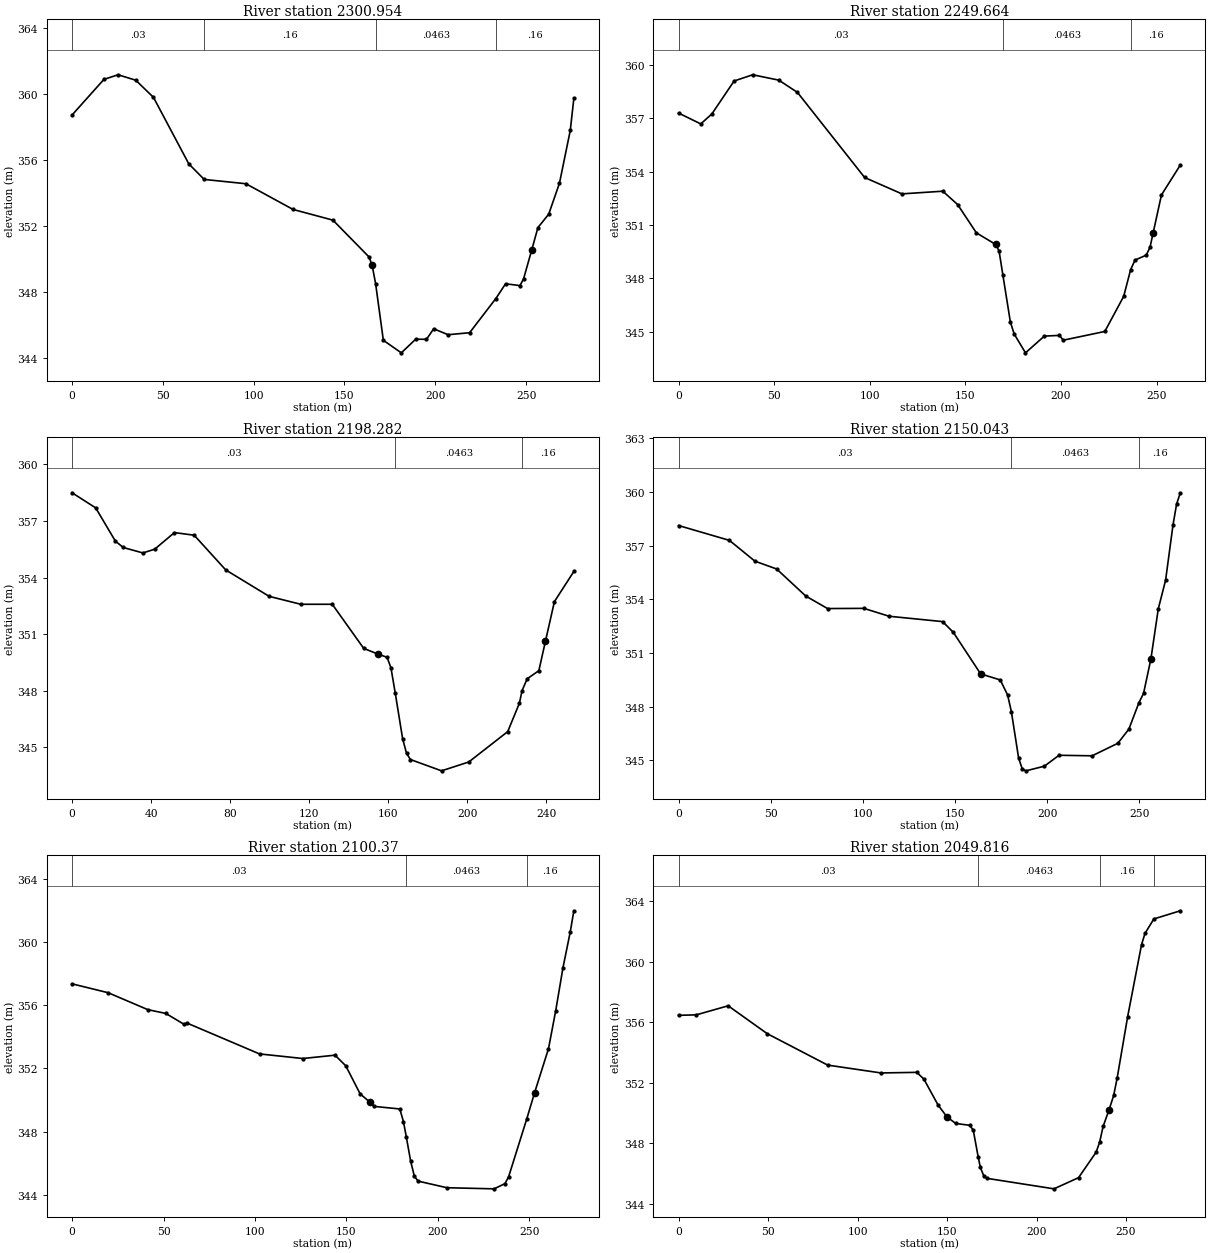
Type RM Length L Ch R = 1 ,2300.954,47.85,51.29,56.79
XS GIS Cut Line= 5
     318859.6942    4049957.5883     318801.6164    4049985.1864
     318786.4969    4050008.0391     318734.5357    4050033.6464
     318620.9135    4050089.6414
#Sta/Elev= 30
       0  358.73   17.54  360.89   25.33  361.17   35.07  360.84   44.82   359.8
    64.3  355.76   72.77  354.82    95.7  354.56  121.67     353  143.64  352.35
  163.49  350.12  165.21  349.62  167.16  348.48   171.4  345.06   181.3   344.3
  189.22  345.13  195.15  345.12  199.11  345.76  207.03   345.4   218.9  345.52
  233.31  347.59   238.7  348.49  246.61  348.38  248.59  348.78   253.1  350.54
  256.51   351.9  262.45  352.71  268.39   354.6  274.32  357.79   276.3  359.74
#Mann= 4 ,-1 , 0
       0     .03       0   72.77     .16       0  167.16   .0463       0
  233.31     .16       0
Bank Sta=165.21,253.1
XS Rating Curve= 0 ,0
Exp/Cntr=0.3,0.1

Type RM Length L Ch R = 1 ,2249.664,47.55,51.38,55.49
XS GIS Cut Line= 5
     318847.6424    4049922.8352     318820.0814    4049947.2244
     318748.8152    4049967.7108     318717.1994    4049990.2924
     318612.1204    4050030.6233
#Sta/Elev= 30
       0  357.29   11.62  356.68   17.43  357.24   29.05  359.09   38.75  359.44
   52.41  359.14   62.17  358.45    97.3  353.67  116.78  352.75  138.15   352.9
  145.92  352.15  155.73  350.56  165.81  349.91  167.58  349.55   169.6  348.18
   173.5  345.55  175.48  344.88   181.4  343.82  191.27  344.76  199.17   344.8
  201.15  344.53  222.87  345.02  232.74  346.99   236.4   348.5  238.66  349.03
  244.59  349.31  246.56  349.77  248.09  350.53  252.49  352.69  262.36  354.37
#Mann= 3 ,-1 , 0
       0     .03       0   169.6   .0463       0   236.4     .16       0
Bank Sta=165.81,248.09
XS Rating Curve= 0 ,0
Exp/Cntr=0.3,0.1

Type RM Length L Ch R = 1 ,2198.282,38.78,48.24,55.68
XS GIS Cut Line= 4
     318830.6259     4049887.789     318803.7583    4049914.4223
      318702.453    4049944.9611     318596.8726    4049976.7887
#Sta/Elev= 30
       0   358.5   11.95   357.7    21.9  355.94   25.88   355.6   35.84  355.31
   41.82  355.51   51.81  356.39   61.79  356.25   77.76  354.41   99.72  353.01
  115.69  352.59  131.66  352.59  147.58  350.25  154.77  349.95  159.39  349.78
  161.36  349.22  163.53  347.88  167.27  345.46  169.24  344.69  171.21  344.36
  186.96  343.76  200.75  344.23  220.44  345.84  226.34  347.34   227.7  348.01
  230.28  348.64  236.19  349.07  239.55  350.64  244.07  352.73  253.91  354.33
#Mann= 3 ,-1 , 0
       0     .03       0  163.53   .0463       0   227.7     .16       0
Bank Sta=154.77,239.55
XS Rating Curve= 0 ,0
Exp/Cntr=0.3,0.1

Type RM Length L Ch R = 1 ,2150.043,48.19,49.67,49.67
XS GIS Cut Line= 4
     318839.8565    4049842.6695     318749.1719    4049898.4104
      318691.617    4049906.1962     318584.9571    4049920.6248
#Sta/Elev= 30
       0  358.12    27.6  357.29    41.4  356.13   53.22  355.69   68.99  354.18
   80.82  353.48  100.53  353.49  114.19  353.05  143.23  352.75  149.04  352.15
  163.84  349.83  174.49  349.49  178.48  348.65  180.52  347.72  184.46  345.12
  186.45  344.51  188.44  344.41  198.41  344.67  206.38  345.28  224.32  345.25
  238.27  345.95  244.25  346.74  249.67  348.21  252.22  348.74  256.21  350.67
   260.2  353.46  264.18  355.07  268.17  358.14  270.16  359.33  272.16  359.95
#Mann= 3 ,-1 , 0
       0     .03       0  180.52   .0463       0  249.67     .16       0
Bank Sta=163.84,256.21
XS Rating Curve= 0 ,0
Exp/Cntr=0.3,0.1

Type RM Length L Ch R = 1 ,2100.37 ,44.63,50.55,60.01
XS GIS Cut Line= 4
      318833.906    4049795.3003     318726.1013    4049856.9219
     318684.9581    4049856.9712     318576.8943    4049871.5897
#Sta/Elev= 30
       0  357.34   19.71  356.78   41.39  355.71   51.25  355.47    61.1  354.79
   63.07  354.85  102.49  352.91  126.13  352.62  143.77  352.83  149.64  352.16
  157.48  350.39  162.92  349.85  165.32  349.59   179.2  349.43  181.18  348.63
  182.74  347.67  185.14  346.12  187.13  345.19  189.11  344.87  204.97  344.45
  230.75  344.38  236.69  344.71  238.68  345.14  248.55  348.78  252.84  350.44
  260.49  353.24  264.45  355.65  268.42  358.37  272.38  360.62  274.36  361.96
#Mann= 3 ,-1 , 0
       0     .03       0  182.74   .0463       0  248.55     .16       0
Bank Sta=162.92,252.84
XS Rating Curve= 0 ,0
Exp/Cntr=0.3,0.1

Type RM Length L Ch R = 1 ,2049.816,49.42,49.79,46.05
XS GIS Cut Line= 6
     318818.1038    4049747.5574     318775.6035    4049783.1735
     318688.2066    4049816.4837     318588.4172    4049809.9965
     318576.8438    4049809.2442     318557.6794     4049814.048
#Sta/Elev= 30
       0  356.47     9.9   356.5   27.73   357.1   49.51  355.26   83.31  353.18
  113.16  352.66  133.06   352.7  137.04  352.26     145  350.54  149.93  349.76
  154.86  349.32  162.71   349.2  164.67  348.87  167.41  347.11  168.59  346.43
  170.55  345.85  172.51  345.69  209.76     345  223.49  345.74  233.29  347.42
  235.23  348.07  237.22  349.13  240.54  350.23   243.1  351.17  245.06  352.33
  250.91  356.38  258.65  361.13  260.58  361.88  265.55  362.84  280.34  363.38
#Mann= 4 ,-1 , 0
       0     .03       0  167.41   .0463       0  235.23     .16       0
  265.55     .03       0
Bank Sta=149.93,240.54
XS Rating Curve= 0 ,0
Exp/Cntr=0.3,0.1

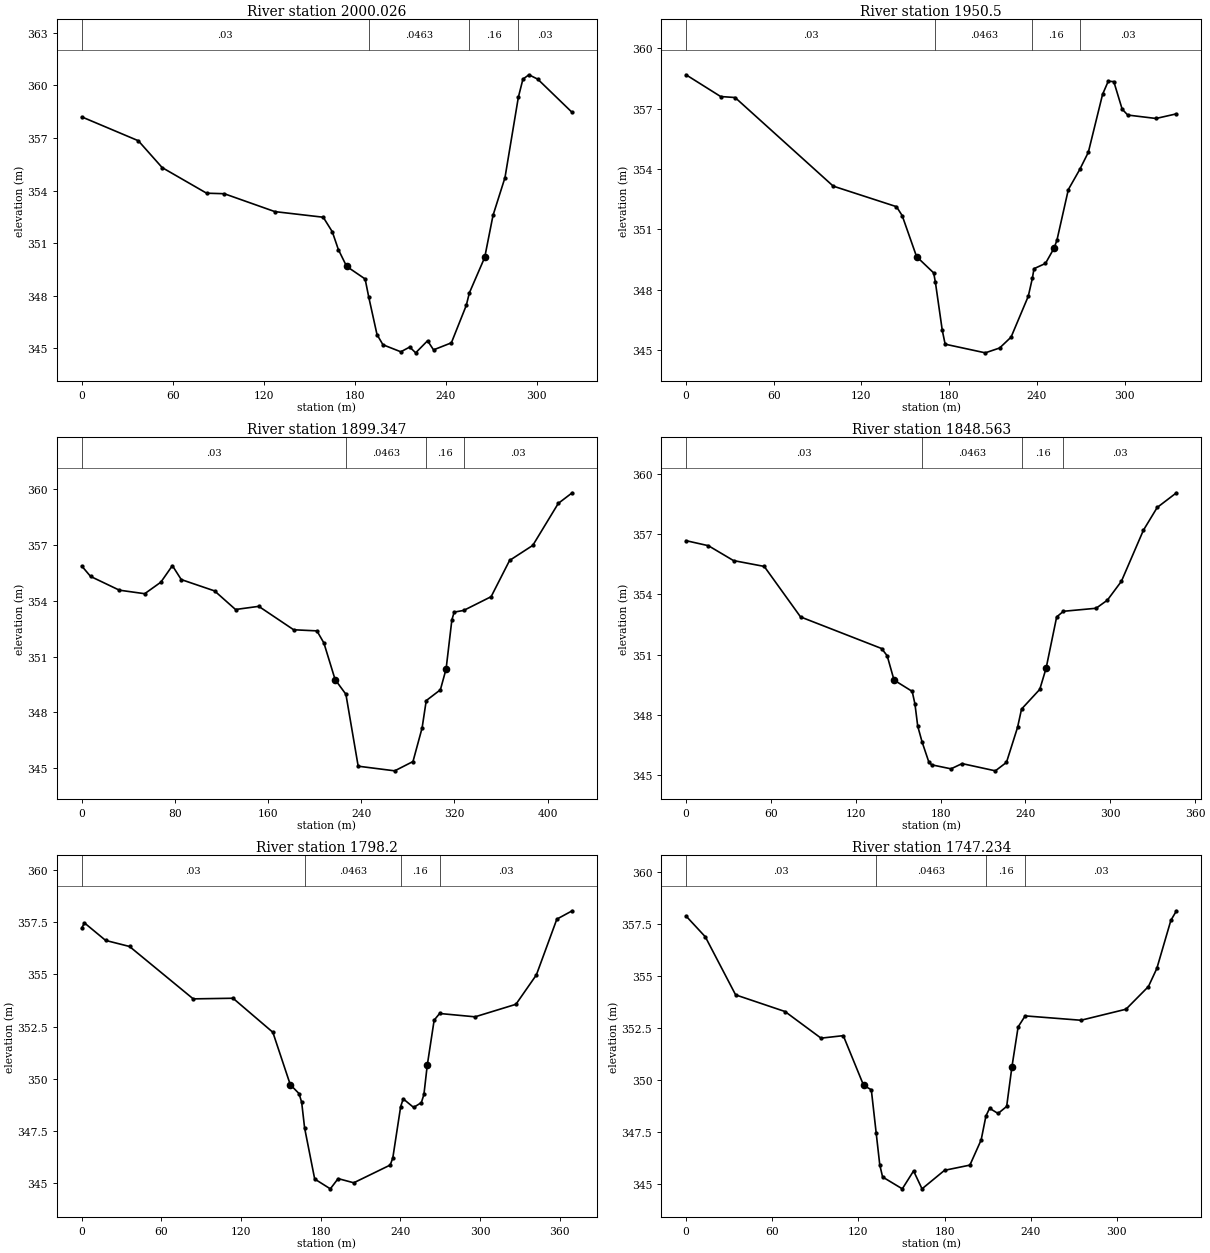
Type RM Length L Ch R = 1 ,2000.026,54.6,49.53,49.66
XS GIS Cut Line= 6
     318839.2136    4049727.4253     318768.5697    4049725.8378
     318747.1444    4049762.7848     318691.3529     4049763.188
      318561.793    4049764.1242       318537.31    4049766.6826
#Sta/Elev= 30
       0   358.2   37.29  356.84      53  355.31   82.31  353.85   93.96  353.82
  127.32   352.8   159.2  352.48  165.18  351.65  169.16  350.64  174.61  349.68
  186.81  348.96   189.2  347.93  194.65  345.79  198.58  345.21  210.34  344.81
  216.22  345.08  220.14  344.75  227.99  345.44  231.91  344.92  243.67  345.32
  253.48  347.45  255.55  348.17  265.65  350.19  271.14  352.59  279.02  354.74
  287.83  359.32  290.84  360.35  294.79   360.6  300.62  360.35  323.34  358.45
#Mann= 4 ,-1 , 0
       0     .03       0   189.2   .0463       0  255.55     .16       0
  287.83     .03       0
Bank Sta=174.61,265.65
XS Rating Curve= 0 ,0
Exp/Cntr=0.3,0.1

Type RM Length L Ch R = 1 ,1950.5  ,46.08,51.15,51.29
XS GIS Cut Line= 6
     318840.0073    4049698.5856     318715.6529    4049701.7606
      318690.995    4049713.6627     318555.8456    4049714.6393
     318541.2649    4049739.2611     318521.4989    4049736.4683
#Sta/Elev= 30
       0  358.68   23.69   357.6   33.57  357.55   100.7  353.15  143.95  352.13
  147.86  351.69  157.72  349.65  169.42  348.84  170.61  348.37   175.3  345.99
  177.27   345.3  204.72  344.87  214.52  345.11  222.36  345.65  234.13  347.68
  236.92  348.57  238.05  349.05  245.89  349.31  251.78  350.07  253.73  350.46
  261.54  352.98  269.37  353.98  275.21  354.83  284.97  357.71  288.84  358.36
  292.65  358.34  298.37  356.97  302.19  356.68  321.53  356.51  335.51  356.74
#Mann= 4 ,-1 , 0
       0     .03       0  170.61   .0463       0  236.92     .16       0
  269.37     .03       0
Bank Sta=157.72,251.78
XS Rating Curve= 0 ,0
Exp/Cntr=0.3,0.1

Type RM Length L Ch R = 1 ,1899.347,57.64,50.78,44.36
XS GIS Cut Line= 6
     318864.5217    4049604.0043     318836.7618    4049616.1435
     318822.7285    4049661.5572     318786.4815    4049661.8191
     318535.1352    4049663.6354     318485.4904    4049689.0356
#Sta/Elev= 30
       0  355.87    7.57  355.31   32.28  354.57   54.06  354.38   67.93     355
   77.83  355.89   85.46  355.14  114.08  354.53  132.05  353.53  152.02   353.7
  181.98  352.44  201.95  352.38  207.94  351.73  217.58  349.76  226.85  348.97
  237.39   345.1  268.76  344.85  284.45  345.35  292.29  347.16  295.84  348.63
  307.98  349.21  312.89  350.33  317.87  352.98  319.85  353.39  327.98  353.48
  351.56  354.22  367.42  356.17  387.34  356.98  409.25  359.24   421.2  359.81
#Mann= 4 ,-1 , 0
       0     .03       0  226.85   .0463       0  295.84     .16       0
  327.98     .03       0
Bank Sta=217.58,312.89
XS Rating Curve= 0 ,0
Exp/Cntr=0.3,0.1

Type RM Length L Ch R = 1 ,1848.563,50.87,50.36,55.83
XS GIS Cut Line= 5
        318833.2    4049579.1734     318687.6495    4049606.9305
      318588.211    4049617.5129     318528.8381    4049623.8314
      318492.478     4049637.791
#Sta/Elev= 30
       0  356.67   15.81  356.42   33.59  355.68   55.32  355.39      81  352.88
   138.3  351.31  142.25  350.95  147.11  349.74  159.94  349.18   161.9  348.55
  163.86  347.45  166.92  346.67   171.7  345.67  173.66  345.53  187.39  345.33
  195.23  345.59  218.76  345.23  226.61  345.65  234.45  347.39  237.27   348.3
  250.16  349.28  254.64  350.33  262.11  352.88   266.9  353.16  289.97  353.31
  297.93  353.71  307.88  354.65  323.46  357.19   333.2  358.32  346.83  359.05
#Mann= 4 ,-1 , 0
       0     .03       0  166.92   .0463       0  237.27     .16       0
   266.9     .03       0
Bank Sta=147.11,254.64
XS Rating Curve= 0 ,0
Exp/Cntr=0.3,0.1

Type RM Length L Ch R = 1 ,1798.2  ,61.42,50.97,34.12
XS GIS Cut Line= 6
      318828.478    4049515.3933       318682.32    4049556.8509
     318582.8815    4049567.4333     318560.3773    4049562.0599
     318519.8959    4049579.9193     318471.8311     4049594.048
#Sta/Elev= 30
       0  357.22       2  357.47   17.99  356.63   35.98  356.34   83.96  353.83
  113.94  353.86  143.93  352.23  157.06  349.72  163.69  349.29  165.65  348.87
  167.84  347.65  175.45   345.2  187.22  344.73   193.1  345.22  204.87  345.02
  232.32  345.87  234.28  346.21   240.2  348.67  242.12  349.04  249.96  348.63
  255.78  348.86  257.71  349.25  260.21  350.64  265.42  352.81  269.54  353.13
  296.22  352.97  327.01  353.57  342.43  354.98  357.84  357.65  369.41  358.05
#Mann= 4 ,-1 , 0
       0     .03       0  167.84   .0463       0   240.2     .16       0
  269.54     .03       0
Bank Sta=157.06,260.21
XS Rating Curve= 0 ,0
Exp/Cntr=0.3,0.1

Type RM Length L Ch R = 1 ,1747.234,48.53,50.44,50.44
XS GIS Cut Line= 6
      318782.478    4049459.3949     318709.3482    4049473.1778
     318674.6335    4049497.9187     318532.3789    4049538.3598
     318509.5489    4049553.6942     318461.4479     4049562.048
#Sta/Elev= 30
       0  357.87   13.43  356.87   34.54  354.08   68.91  353.28      94     352
   109.5  352.12  123.66  349.73  129.01  349.52   132.4  347.44   134.9  345.91
  136.86  345.33  150.58  344.76  158.43  345.62  164.31  344.76  179.99  345.65
  197.64   345.9  205.48  347.11  208.81  348.26  211.37  348.63  217.25  348.38
  223.24  348.72  226.88  350.61  231.22  352.54  236.12  353.07  274.96  352.86
  306.31  353.39  321.94  354.48  327.79  355.35  337.56  357.66  341.46  358.12
#Mann= 4 ,-1 , 0
       0     .03       0   132.4   .0463       0  208.81     .16       0
  236.12     .03       0
Bank Sta=123.66,226.88
XS Rating Curve= 0 ,0
Exp/Cntr=0.3,0.1

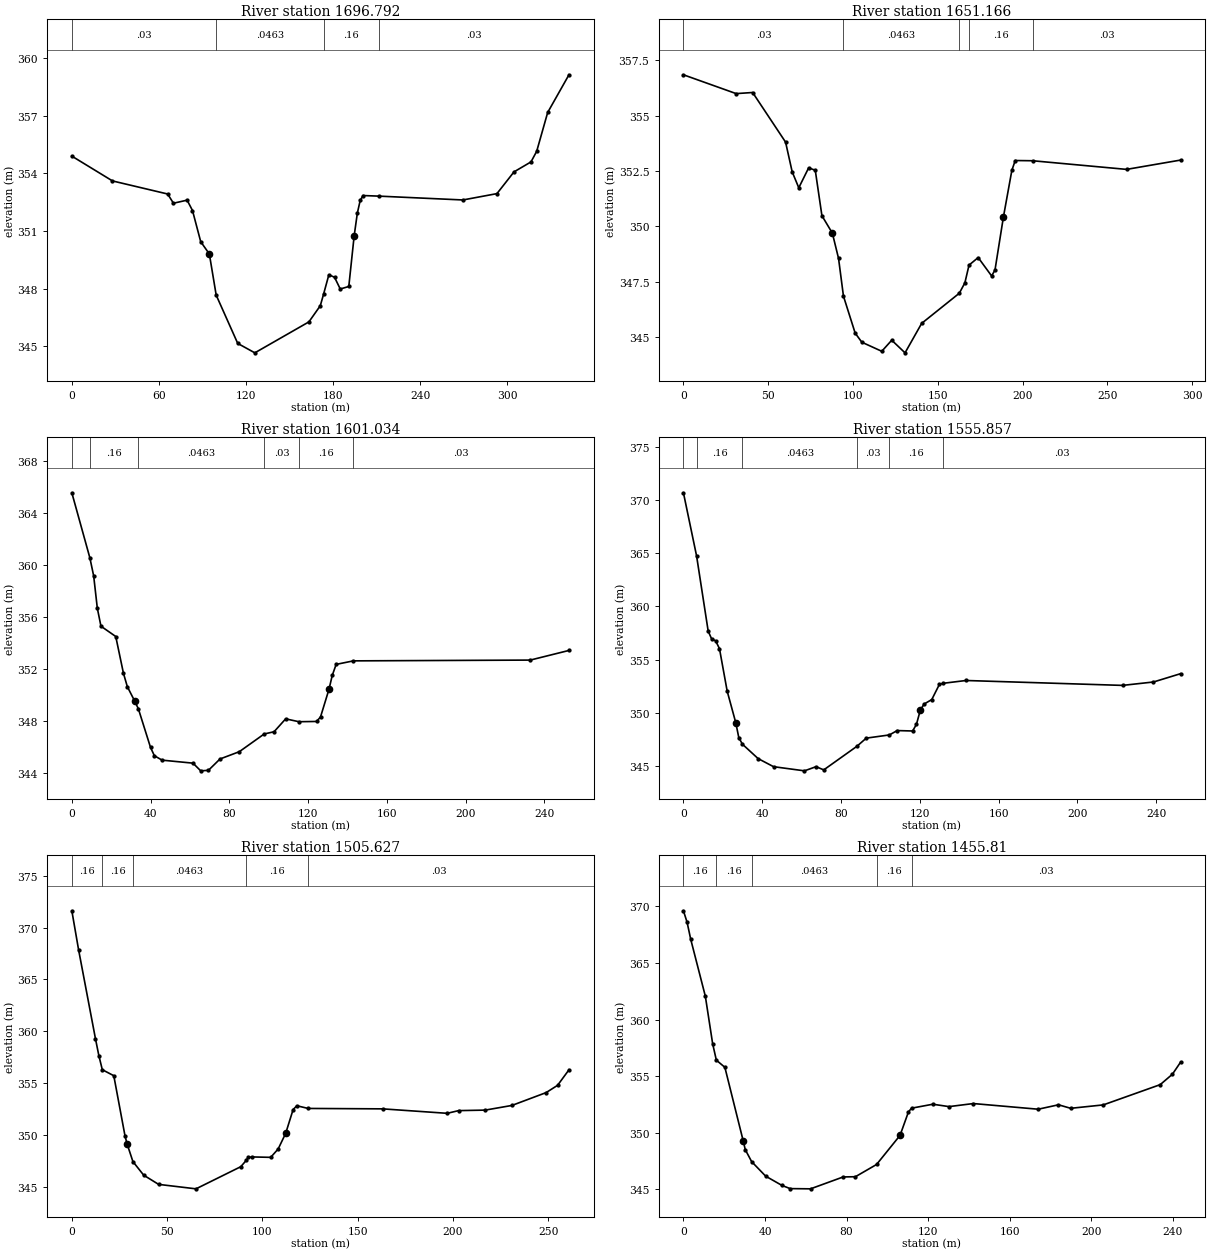
Type RM Length L Ch R = 1 ,1696.792,45.87,45.63,39.26
XS GIS Cut Line= 6
     318746.9404    4049449.5856      318675.091    4049445.3481
     318564.6515    4049476.7446     318496.5699    4049496.0992
     318437.6668    4049526.8592     318431.3435     4049544.048
#Sta/Elev= 30
       0  354.89   27.99   353.6   65.98  352.92   69.97  352.44   79.38   352.6
   83.09  352.06   88.75  350.44    94.7   349.8   99.41  347.66  114.24  345.15
  126.01  344.66  163.26  346.27   171.1  347.11  173.39  347.72  176.99  348.72
  180.91  348.59  184.83  347.98  190.72  348.11  194.43  350.75  196.62  351.93
  198.59  352.59  200.55  352.84  211.25  352.81   269.3  352.61  292.75  352.94
  304.48  354.07   316.2  354.59  320.11  355.14  327.68  357.16  342.34  359.12
#Mann= 4 ,-1 , 0
       0     .03       0   99.41   .0463       0  173.39     .16       0
  211.25     .03       0
Bank Sta=94.7,194.43
XS Rating Curve= 0 ,0
Exp/Cntr=0.3,0.1

Type RM Length L Ch R = 1 ,1651.166,73.74,50.13,23.38
XS GIS Cut Line= 5
     318720.3453    4049414.1807      318672.478    4049397.9778
     318648.3637    4049405.5127     318552.1751    4049432.8579
      318456.478    4049500.8648
#Sta/Elev= 30
       0  356.84    31.1  355.99   40.82  356.04   60.25   353.8   64.14  352.46
   68.03  351.74   73.86  352.64   77.76  352.53   81.68  350.48   87.85  349.69
   91.49  348.55   94.38  346.85  101.29  345.18  105.21  344.77  116.98  344.36
  122.86  344.86   130.7  344.29  140.51  345.62  162.71  346.98     166  347.45
  168.44  348.25  173.84  348.59  181.77  347.76  183.76  348.03  188.72  350.42
  193.71  352.53   195.7  352.97  205.93  352.96  261.36  352.57   293.2  352.99
#Mann= 5 ,-1 , 0
       0     .03       0   94.38   .0463       0  162.71     .03       0
  168.44     .16       0  205.93     .03       0
Bank Sta=87.85,188.72
XS Rating Curve= 0 ,0
Exp/Cntr=0.3,0.1

Type RM Length L Ch R = 1 ,1601.034,64.6,45.18,24.81
XS GIS Cut Line= 5
     318620.8666    4049329.2663     318606.4135    4049343.5777
     318535.3553    4049413.9392     318498.7329    4049450.2027
     318441.4889    4049506.8855
#Sta/Elev= 30
       0  365.54    9.15  360.55   11.09  359.16   12.94  356.68   14.79   355.3
    22.3  354.51   26.22  351.68   28.18  350.66   31.96  349.54   33.81  348.95
   39.95     346   41.91  345.36   45.83  345.02   61.52  344.79   65.44   344.2
   69.36  344.24   75.24  345.11   85.05  345.67   97.69  347.03  102.69   347.2
  108.58  348.19  115.31  347.97   124.3  347.99  126.29  348.34  130.62  350.48
  132.23  351.52  134.22  352.37  142.97  352.64  232.79   352.7  252.44  353.44
#Mann= 6 ,-1 , 0
       0     .16       0    9.15     .16       0   33.81   .0463       0
   97.69     .03       0  115.31     .16       0  142.97     .03       0
Bank Sta=31.96,130.62
XS Rating Curve= 0 ,0
Exp/Cntr=0.3,0.1

Type RM Length L Ch R = 1 ,1555.857,59.12,50.23,34.94
XS GIS Cut Line= 6
     318560.0555    4049292.8238     318554.5329    4049306.0916
     318516.1047    4049398.4132     318498.0245    4049416.0875
     318490.4004    4049443.2773     318435.4596    4049507.3661
#Sta/Elev= 30
       0  370.66    6.68  364.73   12.57  357.67   14.37  356.92   16.33  356.77
   18.29  356.03   22.21  352.04   26.59  349.06    28.1  347.68   29.94  347.06
    37.9  345.71   45.74  344.95   61.43  344.56   67.31  344.95   71.23  344.65
   88.02  346.86    92.8  347.63  104.54  347.93  108.49  348.34  116.32   348.3
  118.26  348.92  120.25  350.27  122.15  350.83  126.04  351.25  129.93  352.68
  131.94  352.78  143.42  353.04  222.86  352.58  238.57   352.9  252.31  353.68
#Mann= 6 ,-1 , 0
       0     .16       0    6.68     .16       0   29.94   .0463       0
   88.02     .03       0  104.54     .16       0  131.94     .03       0
Bank Sta=26.59,120.25
XS Rating Curve= 0 ,0
Exp/Cntr=0.3,0.1

Type RM Length L Ch R = 1 ,1505.627,49.85,49.82,50.68
XS GIS Cut Line= 5
     318501.2791    4049271.3095      318498.468    4049285.2047
      318478.639    4049383.2191     318468.5513    4049433.0826
     318411.4033     4049510.048
#Sta/Elev= 30
       0  371.62    3.54  367.86    12.4  359.27   14.18  357.64   15.99  356.28
   22.02   355.7    27.9   349.9   29.01  349.11   32.06  347.41   37.71   346.1
   45.55  345.21   65.16  344.78   88.69  346.92   91.49  347.52   92.61  347.81
   94.57  347.86  104.37  347.82  108.29  348.63  112.24  350.14  116.13  352.43
  118.09   352.8  124.05  352.54  163.09   352.5     197  352.07     203  352.33
  216.98  352.38  230.96  352.83  248.93  354.07  254.92  354.77  260.91  356.27
#Mann= 5 ,-1 , 0
       0     .16       0   15.99     .16       0   32.06   .0463       0
   91.49     .16       0  124.05     .03       0
Bank Sta=29.01,112.24
XS Rating Curve= 0 ,0
Exp/Cntr=0.3,0.1

Type RM Length L Ch R = 1 ,1455.81 ,53.77,48.88,43.18
XS GIS Cut Line= 5
     318452.4803    4049261.2861     318449.6399    4049275.3265
     318429.8109    4049373.3408     318417.2051    4049435.6514
      318384.478    4049492.7732
#Sta/Elev= 30
       0   369.6    1.79  368.59    3.58  367.08   10.74  362.06   14.32  357.87
   16.14  356.41   20.32  355.78    29.3  349.29   30.32  348.51   33.45  347.45
   40.32  346.17   48.32  345.35   52.32  345.07   62.32  345.05   78.32   346.1
   84.32  346.12   94.69   347.2   106.2  349.77  110.32  351.84  111.82  352.17
  122.27  352.52  130.22  352.31  142.14  352.58  173.92  352.08  183.88  352.47
  189.87  352.16  205.83  352.46  233.76  354.25  239.74  355.17  243.73  356.23
#Mann= 5 ,-1 , 0
       0     .16       0   16.14     .16       0   33.45   .0463       0
   94.69     .16       0  111.82     .03       0
Bank Sta=29.3,106.2
XS Rating Curve= 0 ,0
Exp/Cntr=0.3,0.1

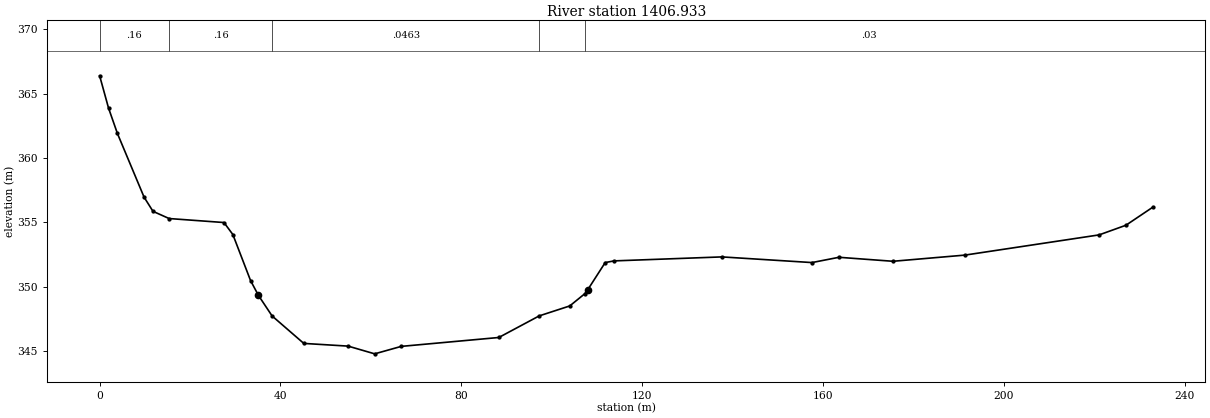
Type RM Length L Ch R = 1 ,1406.933,48.17,48.14,48.14
XS GIS Cut Line= 5
     318396.9074    4049252.1645     318395.3908    4049269.7952
     318386.8202    4049369.4273     318364.4181    4049437.5496
     318355.1249     4049480.048
#Sta/Elev= 30
       0  366.39    1.97  363.88    3.93  361.91    9.83  356.96    11.8  355.86
   15.37   355.3    27.5  354.99   29.46  354.06   33.38  350.48   35.12  349.33
   38.15  347.73   45.15   345.6   54.95  345.39   60.83  344.79   66.72  345.37
   88.28  346.06   97.23  347.74  103.97  348.51   107.3  349.46  107.97  349.78
  111.81  351.88  113.77  352.01  137.62  352.32  157.54  351.88  163.51  352.29
  175.46  351.98  191.38  352.46  221.05  354.03  226.98  354.78  232.91  356.18
#Mann= 5 ,-1 , 0
       0     .16       0   15.37     .16       0   38.15   .0463       0
   97.23     .16       0   107.3     .03       0
Bank Sta=35.12,107.97
XS Rating Curve= 0 ,0
Exp/Cntr=0.3,0.1