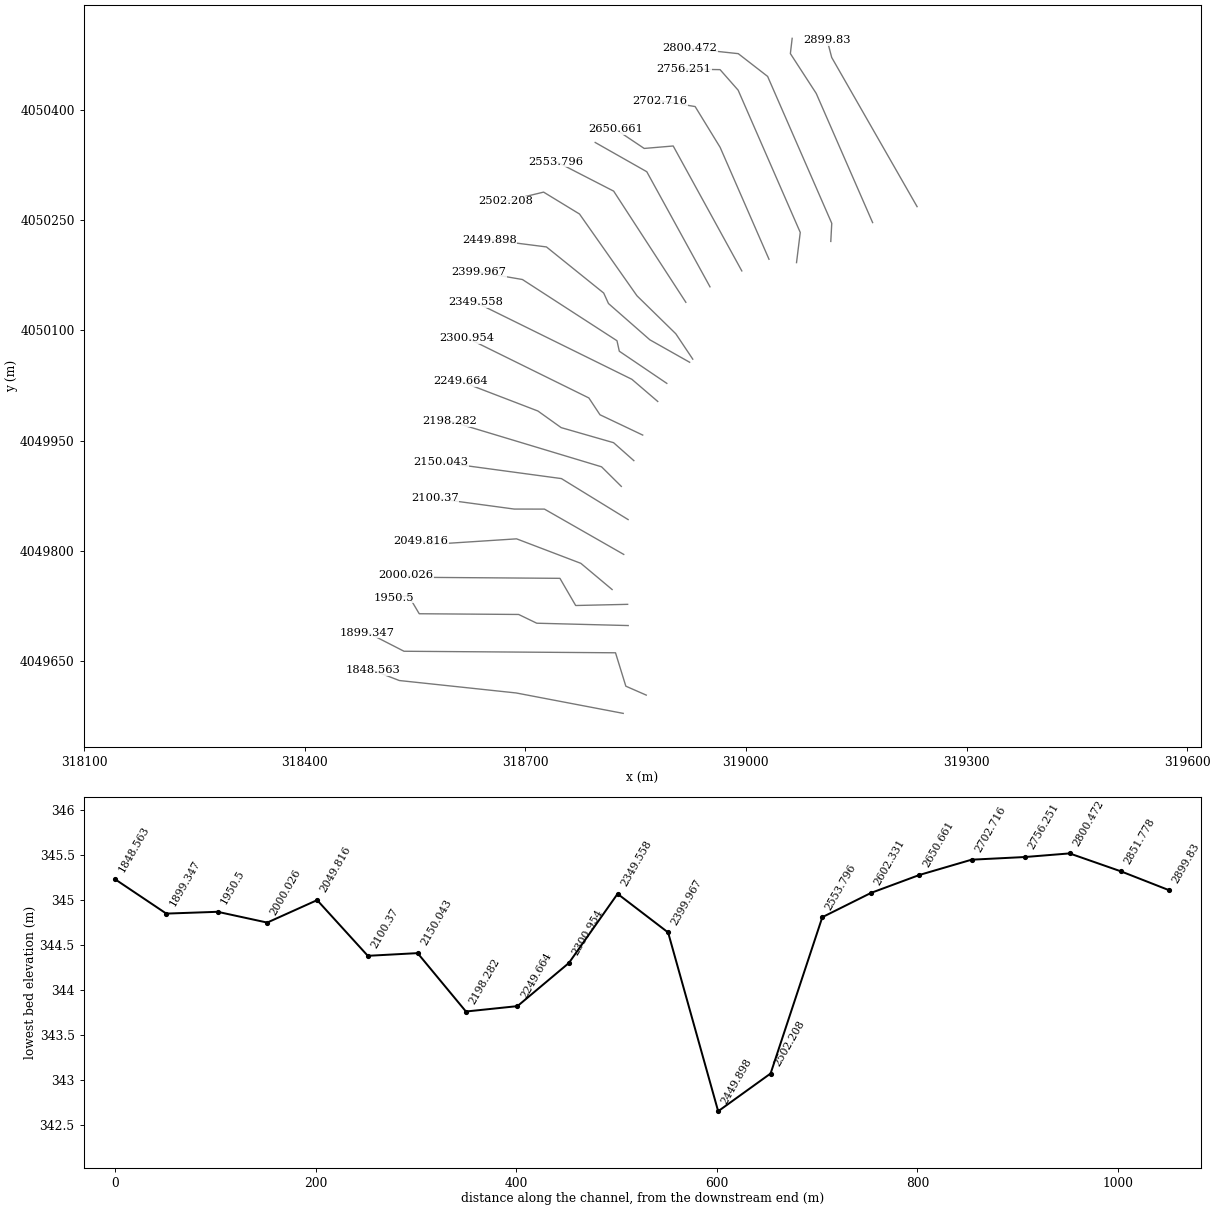
HEC-RAS study WBmod1D.prj: WBmod1D

--- WBmod1D.g02 (geometry) --- (continued)

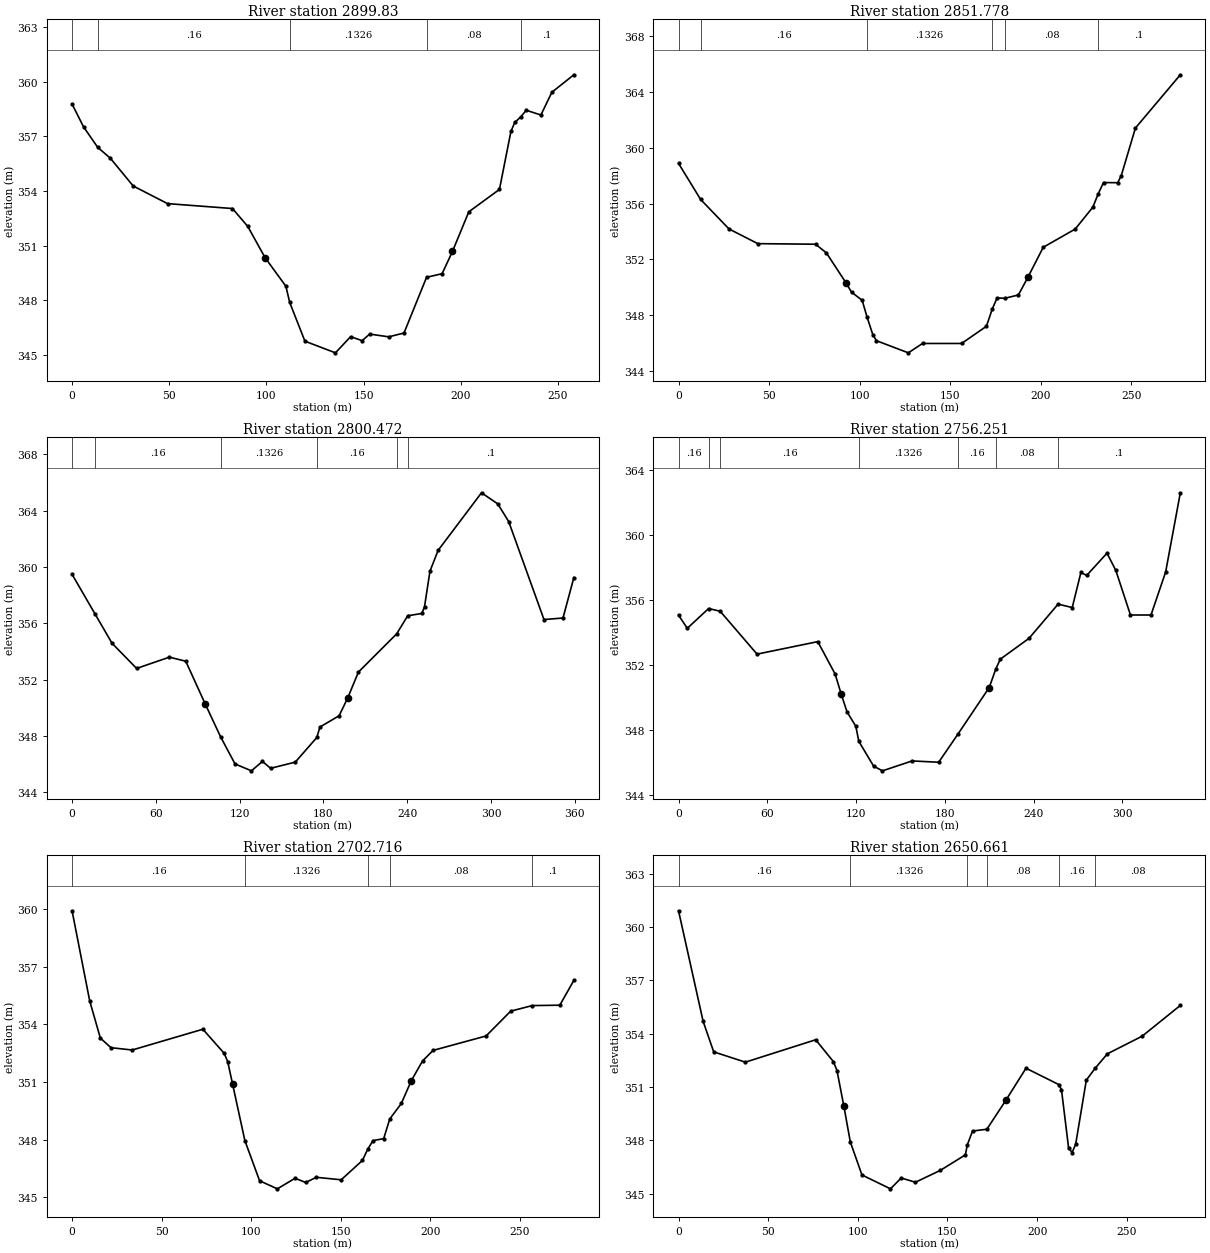
Type RM Length L Ch R = 1 ,2899.83 ,54.58,48.05,43.43
XS GIS Cut Line= 5
     319232.7725    4050268.1537     319182.9865    4050355.1372
     319133.3115    4050441.9266     319116.6712    4050470.9997
      319110.478    4050494.7036
#Sta/Elev= 30
       0  358.78     5.9  357.53   13.21   356.4   19.65  355.81   31.44  354.28
   49.13  353.31   82.54  353.04    90.4  352.06   99.32  350.34  110.03  348.77
  111.99  347.88  119.83  345.75  135.52  345.11  143.36     346  149.24  345.78
  153.16  346.14  162.97  345.99  170.81   346.2  182.42  349.26  190.42  349.46
  195.74  350.68  204.16  352.86  219.93  354.09  225.84  357.28  227.81  357.77
  230.84  358.07  233.72  358.44  241.26  358.18  246.91  359.43  258.22  360.39
#Mann= 5 ,-1 , 0
       0     .03       0   13.21     .16       0  111.99   .1326       0
  182.42     .08       0  230.84      .1       0
Bank Sta=99.32,195.74
XS Rating Curve= 0 ,0
Exp/Cntr=0.3,0.1

Type RM Length L Ch R = 1 ,2851.778,51.31,51.31,49.47
XS GIS Cut Line= 5
     319172.3017    4050246.4891     319135.6531    4050330.4279
     319095.6397    4050422.0736      319060.478    4050476.2687
     319062.9214    4050497.0106
#Sta/Elev= 30
       0  358.87   12.21  356.29   27.88  354.18    43.8  353.13   75.66  353.09
   81.64  352.47    92.5  350.32   95.51  349.66  101.39  349.08  104.07  347.89
  107.28  346.62  109.24  346.19  126.88  345.32  134.73  345.99   156.3  345.99
  170.02  347.22  173.22  348.45   175.9  349.25  180.09  349.22  187.67  349.46
  192.85  350.71  201.38  352.87     219  354.17  228.79  355.74  231.68  356.68
  234.66   357.5  242.49  357.49  244.45  357.99  252.28   361.4  277.08  365.21
#Mann= 6 ,-1 , 0
       0     .03       0   12.21     .16       0  104.07   .1326       0
  173.22     .16       0  180.09     .08       0  231.68      .1       0
Bank Sta=92.5,192.85
XS Rating Curve= 0 ,0
Exp/Cntr=0.3,0.1

Type RM Length L Ch R = 1 ,2800.472,44.29,44.22,44.22
XS GIS Cut Line= 6
     319115.4442      4050220.86     319116.7445    4050245.5142
     319088.5703    4050310.0436     319029.5432    4050445.2378
     318989.6214    4050476.1835     318923.8778    4050483.2626
#Sta/Elev= 30
       0  359.47    16.6  356.63    28.6  354.58    46.2  352.79   69.67  353.59
   81.41   353.3   95.27  350.28  106.36  347.93  116.67  346.01  128.43  345.52
  136.28  346.19  142.16   345.7  159.81  346.14  175.25  347.89  177.45  348.63
  191.18  349.43  197.41  350.71     205  352.53  232.43  355.25   240.3  356.53
  250.39  356.69  252.33  357.17  256.22  359.69  262.05  361.17  293.13  365.26
   304.8  364.47  312.58  363.22  337.86  356.26  351.47  356.37  359.25  359.24
#Mann= 6 ,-1 , 0
       0     .03       0    16.6     .16       0  106.36   .1326       0
  175.25     .16       0  232.43     .08       0   240.3      .1       0
Bank Sta=95.27,197.41
XS Rating Curve= 0 ,0
Exp/Cntr=0.3,0.1

Type RM Length L Ch R = 1 ,2756.251,53.65,53.53,57.4
XS GIS Cut Line= 6
       319068.84     4050192.048     319073.9231    4050233.0765
     319008.0938    4050383.8501     318989.4643    4050426.5185
     318964.8828    4050454.4528     318915.3191    4050455.2069
#Sta/Elev= 30
       0  355.07    5.91  354.26   20.35  355.48   28.16  355.31   53.07  352.67
   94.13  353.44  105.86  351.44  109.96  350.21  113.86  349.12  119.86  348.22
  121.85   347.3  131.86  345.77  137.86  345.48  157.86  346.09  175.86  346.01
   188.7  347.72  210.01  350.61  214.49  351.76   217.5  352.36   236.9  353.64
  256.58  355.75  266.13  355.54     272   357.7  275.92  357.52  289.63  358.89
  295.58  357.83  305.49  355.08  319.37  355.08  329.28  357.73   339.2  362.61
#Mann= 7 ,-1 , 0
       0     .16       0   20.35     .03       0   28.16     .16       0
  121.85   .1326       0   188.7     .16       0  214.49     .08       0
  256.58      .1       0
Bank Sta=109.96,210.01
XS Rating Curve= 0 ,0
Exp/Cntr=0.3,0.1

Type RM Length L Ch R = 1 ,2702.716,47.73,52.06,57.4
XS GIS Cut Line= 5
     319031.4181    4050196.6362     318999.0447    4050270.7833
     318964.9818    4050348.8001     318930.9907    4050404.2458
     318882.6555    4050412.2255
#Sta/Elev= 30
       0  359.91    9.87  355.21   15.79  353.29   21.71  352.79   33.55  352.67
   73.01  353.75   84.87   352.5   86.85  352.07   89.58   350.9   96.44  347.96
  104.66  345.87  114.56  345.45  124.46     346   130.4  345.78  136.34  346.05
   150.2  345.92  162.08  346.93  165.11  347.53  168.01  347.96  173.92  348.06
  177.29  349.08  183.77  349.89  189.31  351.07   195.6   352.1  201.51  352.65
  231.07   353.4  244.79  354.69  256.81  354.98  272.22     355  280.06  356.29
#Mann= 5 ,-1 , 0
       0     .16       0   96.44   .1326       0  165.11     .16       0
  177.29     .08       0  256.81      .1       0
Bank Sta=89.58,189.31
XS Rating Curve= 0 ,0
Exp/Cntr=0.3,0.1

Type RM Length L Ch R = 1 ,2650.661,48.33,48.33,53.76
XS GIS Cut Line= 5
      318994.451    4050180.7748     318955.7425    4050251.2559
     318901.1611    4050350.6387     318861.7282    4050347.2982
     318823.0923    4050373.1647
#Sta/Elev= 30
       0  360.91   13.73  354.69   19.61  352.98   37.26   352.4   76.49  353.66
   86.38  352.43   88.37  351.93    92.2  349.93    95.8  347.92  102.29  346.06
  118.21  345.28  124.17  345.89  132.13  345.65  146.05  346.32  159.98  347.19
  161.02  347.74  163.96  348.53  171.96  348.63  182.63  350.27   193.8  352.06
   212.1  351.14  213.58  350.85  217.54  347.58  219.52  347.32   221.5  347.79
  227.43  351.39  232.29  352.05  239.18  352.87  258.55  353.86  279.86  355.59
#Mann= 6 ,-1 , 0
       0     .16       0    95.8   .1326       0  161.02     .16       0
  171.96     .08       0   212.1     .16       0  232.29     .08       0
Bank Sta=92.2,182.63
XS Rating Curve= 0 ,0
Exp/Cntr=0.3,0.1

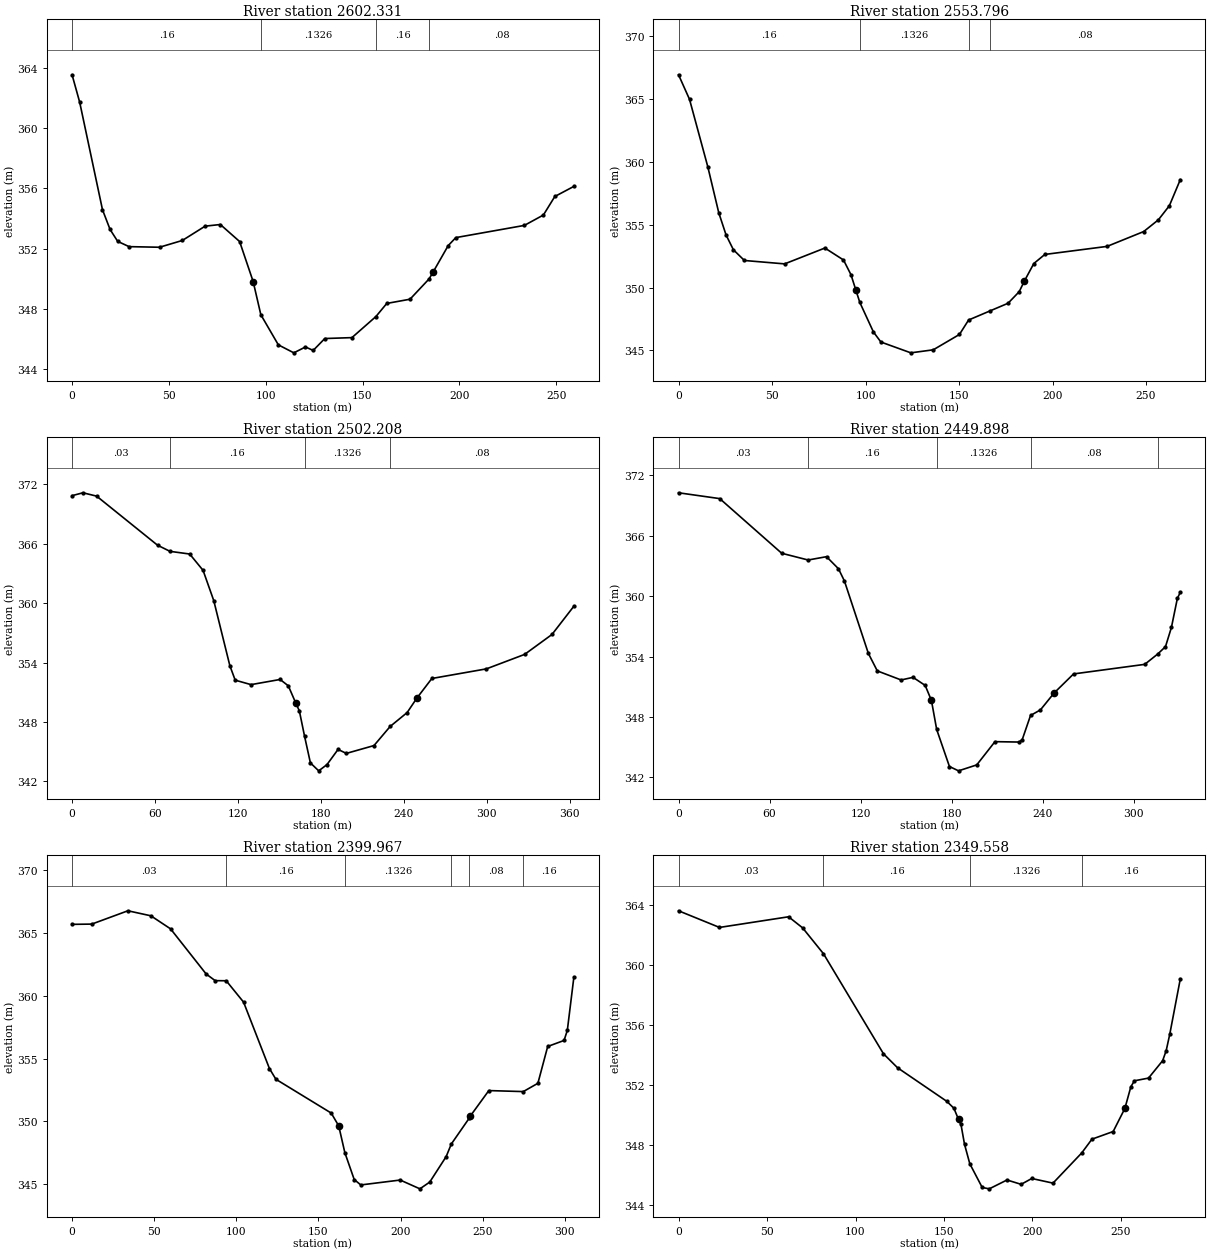
Type RM Length L Ch R = 1 ,2602.331,44.95,48.53,51.93
XS GIS Cut Line= 4
      318951.185    4050159.1563     318913.3808    4050227.9908
     318865.2426    4050315.6418     318795.1189    4050355.4071
#Sta/Elev= 30
       0  363.54    3.93  361.72   15.71  354.58   19.63  353.27   23.56  352.48
   29.45  352.13   45.16  352.09   56.94  352.54   68.72  353.49   76.57   353.6
   86.53  352.47   93.53  349.81   97.49  347.61  106.53  345.61  114.53  345.08
  120.53  345.47  124.53  345.24  130.53  346.03  144.53  346.09  156.93  347.49
  162.53  348.36  174.53  348.64   184.4  349.99  186.44  350.44  194.26   352.2
  198.19  352.73  233.59  353.54  243.42  354.23  249.32  355.46  259.15  356.13
#Mann= 4 ,-1 , 0
       0     .16       0   97.49   .1326       0  156.93     .16       0
   184.4     .08       0
Bank Sta=93.53,186.44
XS Rating Curve= 0 ,0
Exp/Cntr=0.3,0.1

Type RM Length L Ch R = 1 ,2553.796,47.38,51.59,52.86
XS GIS Cut Line= 4
     318918.3744    4050138.0873      318874.685      4050205.37
     318820.2251    4050289.2396      318741.843    4050329.5272
#Sta/Elev= 30
       0  366.91    5.87  364.96   15.65   359.6   21.52  355.94   25.44  354.17
   29.35     353   35.22  352.15   56.74  351.88   78.27  353.14   88.22  352.19
   92.22  351.02   94.89  349.77   96.94  348.82  104.22  346.47  108.22  345.67
  124.22  344.81  136.22  345.05  150.22  346.27  155.13  347.42  166.38  348.13
  176.22  348.75  182.18  349.67  184.93  350.51  190.01  351.91  195.89  352.63
  229.18  353.27  248.77  354.45   256.6  355.38  262.48   356.5  268.35  358.58
#Mann= 4 ,-1 , 0
       0     .16       0   96.94   .1326       0  155.13     .16       0
  166.38     .08       0
Bank Sta=94.89,184.93
XS Rating Curve= 0 ,0
Exp/Cntr=0.3,0.1

Type RM Length L Ch R = 1 ,2502.208,41.25,52.31,70.71
XS GIS Cut Line= 6
     318927.7726    4050060.8062     318904.7116    4050095.3072
     318851.8902    4050146.9689     318773.7739    4050258.1385
     318724.9338    4050287.9253      318673.013    4050275.3072
#Sta/Elev= 30
       0  370.84     7.9  371.13   17.79  370.79   61.84  365.84   70.86  365.22
   85.11  364.95    94.8   363.3  102.55  360.24  114.18  353.68  118.04  352.22
  129.51  351.77  150.55  352.29  156.47  351.65  162.01  349.87  164.47  349.12
  168.27  346.54  172.47  343.87  178.47  343.07  184.47   343.7  192.47  345.23
  198.47  344.83  218.47  345.62  230.19  347.55  242.47  348.95   249.4  350.39
  260.36  352.39  299.81  353.36  327.48  354.82  347.27  356.83  363.11  359.68
#Mann= 4 ,-1 , 0
       0     .03       0   70.86     .16       0  168.27   .1326       0
  230.19     .08       0
Bank Sta=162.01,249.4
XS Rating Curve= 0 ,0
Exp/Cntr=0.3,0.1

Type RM Length L Ch R = 1 ,2449.898,45.05,49.93,56.51
XS GIS Cut Line= 6
     318923.5062     4050056.581     318869.4264    4050087.0996
     318813.1538    4050136.4338     318806.6824    4050150.6671
     318728.7998    4050213.3911     318651.2398    4050223.2862
#Sta/Elev= 30
       0  370.28   27.17   369.7      68  364.27   85.42   363.6   97.55  363.93
  105.42  362.73  109.36  361.51  125.12  354.32  131.02  352.58  146.71  351.68
  154.57  351.94  162.57  351.14  166.69  349.65  170.16  346.76  178.57  343.08
  184.57  342.65  196.57  343.24  208.57  345.55  224.57  345.51  226.57  345.76
  232.02  348.15  238.57  348.71  247.59  350.39  260.39  352.28   307.3  353.23
  315.79  354.25  320.98  354.99  324.89   356.9   328.8  359.78  330.76   360.4
#Mann= 5 ,-1 , 0
       0     .03       0   85.42     .16       0  170.16   .1326       0
  232.02     .08       0  315.79     .16       0
Bank Sta=166.69,247.59
XS Rating Curve= 0 ,0
Exp/Cntr=0.3,0.1

Type RM Length L Ch R = 1 ,2399.967,44.95,50.41,50.66
XS GIS Cut Line= 6
      318892.478    4050027.8745     318827.8978     4050071.571
     318824.7173    4050085.8502     318780.0808     4050114.748
      318696.137    4050169.0935     318637.2737    4050179.2523
#Sta/Elev= 30
       0  365.69      12  365.71   33.99  366.77   47.98  366.37   59.98  365.33
   81.63  361.74   87.12  361.21   93.86   361.2  104.42   359.5  120.18  354.21
  124.11  353.36  157.78  350.67  162.35  349.65  166.08  347.52  171.78  345.38
  175.78  344.95  199.78  345.34  211.78  344.64  217.78  345.18  227.78  347.21
  230.91  348.21  241.73  350.25  242.34  350.41  253.74  352.46  274.72  352.38
  283.61  353.04  289.58  355.97  299.54  356.45  301.53  357.25  305.51  361.48
#Mann= 6 ,-1 , 0
       0     .03       0   93.86     .16       0  166.08   .1326       0
  230.91     .16       0  241.73     .08       0  274.72     .16       0
Bank Sta=162.35,242.34
XS Rating Curve= 0 ,0
Exp/Cntr=0.3,0.1

Type RM Length L Ch R = 1 ,2349.558,48.63,48.6,49.12
XS GIS Cut Line= 5
     318880.1432    4050003.2819     318844.9899    4050033.3978
     318755.9173    4050077.2943     318666.2184    4050121.4994
     318632.1909    4050138.2687
#Sta/Elev= 30
       0   363.6   23.14  362.49   62.18   363.2   70.12  362.46   81.88  360.74
   115.8  354.07  123.74  353.14  151.59   350.9  155.59  350.44  158.19   349.7
  159.59  349.36  161.59  348.04  164.58  346.74  171.59  345.16  175.59  345.07
  185.59  345.66  193.59  345.37  199.59  345.76  211.59  345.45   227.8  347.46
  233.59  348.38  245.59  348.89   252.2  350.43  255.57  351.87  257.57  352.27
  265.56  352.45  273.54  353.61  275.54  354.28  277.54  355.36  283.53  359.07
#Mann= 4 ,-1 , 0
       0     .03       0   81.88     .16       0  164.58   .1326       0
   227.8     .16       0
Bank Sta=158.19,252.2
XS Rating Curve= 0 ,0
Exp/Cntr=0.3,0.1

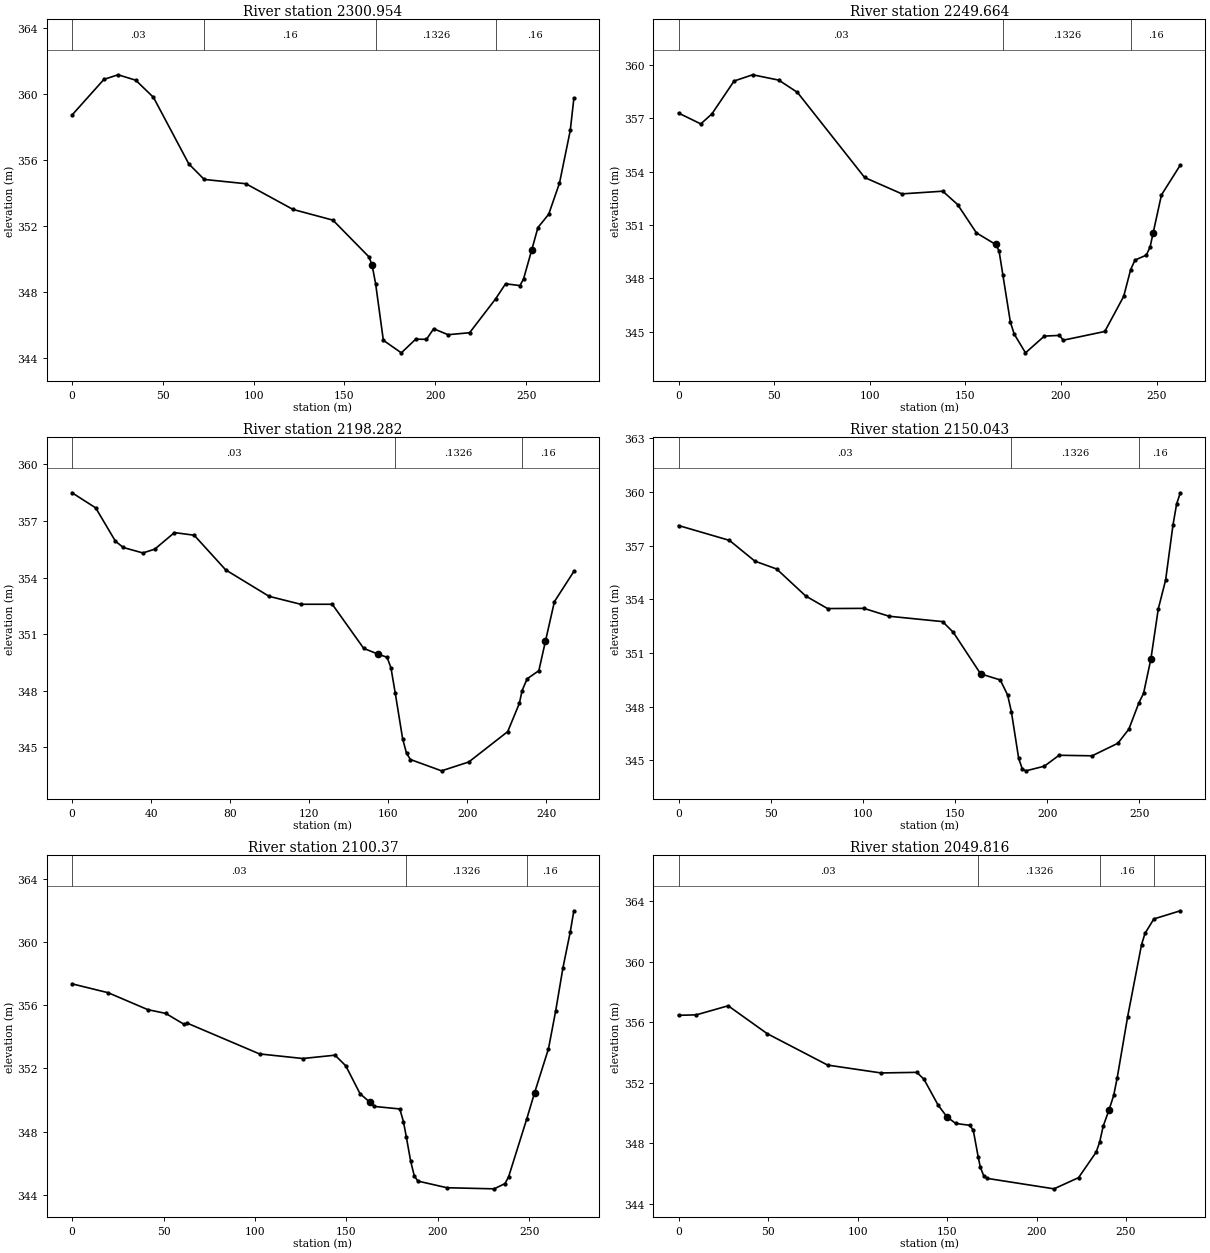
Type RM Length L Ch R = 1 ,2300.954,47.85,51.29,56.79
XS GIS Cut Line= 5
     318859.6942    4049957.5883     318801.6164    4049985.1864
     318786.4969    4050008.0391     318734.5357    4050033.6464
     318620.9135    4050089.6414
#Sta/Elev= 30
       0  358.73   17.54  360.89   25.33  361.17   35.07  360.84   44.82   359.8
    64.3  355.76   72.77  354.82    95.7  354.56  121.67     353  143.64  352.35
  163.49  350.12  165.21  349.62  167.16  348.48   171.4  345.06   181.3   344.3
  189.22  345.13  195.15  345.12  199.11  345.76  207.03   345.4   218.9  345.52
  233.31  347.59   238.7  348.49  246.61  348.38  248.59  348.78   253.1  350.54
  256.51   351.9  262.45  352.71  268.39   354.6  274.32  357.79   276.3  359.74
#Mann= 4 ,-1 , 0
       0     .03       0   72.77     .16       0  167.16   .1326       0
  233.31     .16       0
Bank Sta=165.21,253.1
XS Rating Curve= 0 ,0
Exp/Cntr=0.3,0.1

Type RM Length L Ch R = 1 ,2249.664,47.55,51.38,55.49
XS GIS Cut Line= 5
     318847.6424    4049922.8352     318820.0814    4049947.2244
     318748.8152    4049967.7108     318717.1994    4049990.2924
     318612.1204    4050030.6233
#Sta/Elev= 30
       0  357.29   11.62  356.68   17.43  357.24   29.05  359.09   38.75  359.44
   52.41  359.14   62.17  358.45    97.3  353.67  116.78  352.75  138.15   352.9
  145.92  352.15  155.73  350.56  165.81  349.91  167.58  349.55   169.6  348.18
   173.5  345.55  175.48  344.88   181.4  343.82  191.27  344.76  199.17   344.8
  201.15  344.53  222.87  345.02  232.74  346.99   236.4   348.5  238.66  349.03
  244.59  349.31  246.56  349.77  248.09  350.53  252.49  352.69  262.36  354.37
#Mann= 3 ,-1 , 0
       0     .03       0   169.6   .1326       0   236.4     .16       0
Bank Sta=165.81,248.09
XS Rating Curve= 0 ,0
Exp/Cntr=0.3,0.1

Type RM Length L Ch R = 1 ,2198.282,38.78,48.24,55.68
XS GIS Cut Line= 4
     318830.6259     4049887.789     318803.7583    4049914.4223
      318702.453    4049944.9611     318596.8726    4049976.7887
#Sta/Elev= 30
       0   358.5   11.95   357.7    21.9  355.94   25.88   355.6   35.84  355.31
   41.82  355.51   51.81  356.39   61.79  356.25   77.76  354.41   99.72  353.01
  115.69  352.59  131.66  352.59  147.58  350.25  154.77  349.95  159.39  349.78
  161.36  349.22  163.53  347.88  167.27  345.46  169.24  344.69  171.21  344.36
  186.96  343.76  200.75  344.23  220.44  345.84  226.34  347.34   227.7  348.01
  230.28  348.64  236.19  349.07  239.55  350.64  244.07  352.73  253.91  354.33
#Mann= 3 ,-1 , 0
       0     .03       0  163.53   .1326       0   227.7     .16       0
Bank Sta=154.77,239.55
XS Rating Curve= 0 ,0
Exp/Cntr=0.3,0.1

Type RM Length L Ch R = 1 ,2150.043,48.19,49.67,49.67
XS GIS Cut Line= 4
     318839.8565    4049842.6695     318749.1719    4049898.4104
      318691.617    4049906.1962     318584.9571    4049920.6248
#Sta/Elev= 30
       0  358.12    27.6  357.29    41.4  356.13   53.22  355.69   68.99  354.18
   80.82  353.48  100.53  353.49  114.19  353.05  143.23  352.75  149.04  352.15
  163.84  349.83  174.49  349.49  178.48  348.65  180.52  347.72  184.46  345.12
  186.45  344.51  188.44  344.41  198.41  344.67  206.38  345.28  224.32  345.25
  238.27  345.95  244.25  346.74  249.67  348.21  252.22  348.74  256.21  350.67
   260.2  353.46  264.18  355.07  268.17  358.14  270.16  359.33  272.16  359.95
#Mann= 3 ,-1 , 0
       0     .03       0  180.52   .1326       0  249.67     .16       0
Bank Sta=163.84,256.21
XS Rating Curve= 0 ,0
Exp/Cntr=0.3,0.1

Type RM Length L Ch R = 1 ,2100.37 ,44.63,50.55,60.01
XS GIS Cut Line= 4
      318833.906    4049795.3003     318726.1013    4049856.9219
     318684.9581    4049856.9712     318576.8943    4049871.5897
#Sta/Elev= 30
       0  357.34   19.71  356.78   41.39  355.71   51.25  355.47    61.1  354.79
   63.07  354.85  102.49  352.91  126.13  352.62  143.77  352.83  149.64  352.16
  157.48  350.39  162.92  349.85  165.32  349.59   179.2  349.43  181.18  348.63
  182.74  347.67  185.14  346.12  187.13  345.19  189.11  344.87  204.97  344.45
  230.75  344.38  236.69  344.71  238.68  345.14  248.55  348.78  252.84  350.44
  260.49  353.24  264.45  355.65  268.42  358.37  272.38  360.62  274.36  361.96
#Mann= 3 ,-1 , 0
       0     .03       0  182.74   .1326       0  248.55     .16       0
Bank Sta=162.92,252.84
XS Rating Curve= 0 ,0
Exp/Cntr=0.3,0.1

Type RM Length L Ch R = 1 ,2049.816,49.42,49.79,46.05
XS GIS Cut Line= 6
     318818.1038    4049747.5574     318775.6035    4049783.1735
     318688.2066    4049816.4837     318588.4172    4049809.9965
     318576.8438    4049809.2442     318557.6794     4049814.048
#Sta/Elev= 30
       0  356.47     9.9   356.5   27.73   357.1   49.51  355.26   83.31  353.18
  113.16  352.66  133.06   352.7  137.04  352.26     145  350.54  149.93  349.76
  154.86  349.32  162.71   349.2  164.67  348.87  167.41  347.11  168.59  346.43
  170.55  345.85  172.51  345.69  209.76     345  223.49  345.74  233.29  347.42
  235.23  348.07  237.22  349.13  240.54  350.23   243.1  351.17  245.06  352.33
  250.91  356.38  258.65  361.13  260.58  361.88  265.55  362.84  280.34  363.38
#Mann= 4 ,-1 , 0
       0     .03       0  167.41   .1326       0  235.23     .16       0
  265.55     .03       0
Bank Sta=149.93,240.54
XS Rating Curve= 0 ,0
Exp/Cntr=0.3,0.1

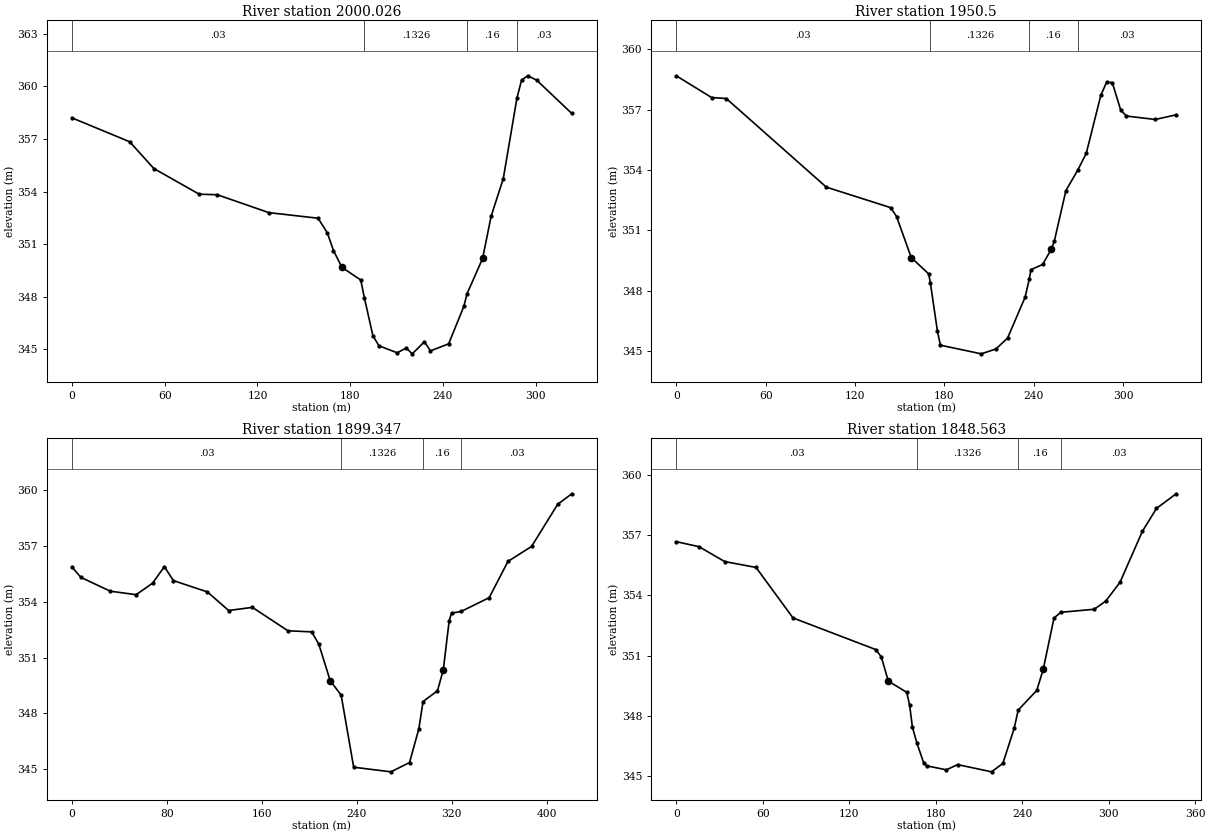
Type RM Length L Ch R = 1 ,2000.026,54.6,49.53,49.66
XS GIS Cut Line= 6
     318839.2136    4049727.4253     318768.5697    4049725.8378
     318747.1444    4049762.7848     318691.3529     4049763.188
      318561.793    4049764.1242       318537.31    4049766.6826
#Sta/Elev= 30
       0   358.2   37.29  356.84      53  355.31   82.31  353.85   93.96  353.82
  127.32   352.8   159.2  352.48  165.18  351.65  169.16  350.64  174.61  349.68
  186.81  348.96   189.2  347.93  194.65  345.79  198.58  345.21  210.34  344.81
  216.22  345.08  220.14  344.75  227.99  345.44  231.91  344.92  243.67  345.32
  253.48  347.45  255.55  348.17  265.65  350.19  271.14  352.59  279.02  354.74
  287.83  359.32  290.84  360.35  294.79   360.6  300.62  360.35  323.34  358.45
#Mann= 4 ,-1 , 0
       0     .03       0   189.2   .1326       0  255.55     .16       0
  287.83     .03       0
Bank Sta=174.61,265.65
XS Rating Curve= 0 ,0
Exp/Cntr=0.3,0.1

Type RM Length L Ch R = 1 ,1950.5  ,46.08,51.15,51.29
XS GIS Cut Line= 6
     318840.0073    4049698.5856     318715.6529    4049701.7606
      318690.995    4049713.6627     318555.8456    4049714.6393
     318541.2649    4049739.2611     318521.4989    4049736.4683
#Sta/Elev= 30
       0  358.68   23.69   357.6   33.57  357.55   100.7  353.15  143.95  352.13
  147.86  351.69  157.72  349.65  169.42  348.84  170.61  348.37   175.3  345.99
  177.27   345.3  204.72  344.87  214.52  345.11  222.36  345.65  234.13  347.68
  236.92  348.57  238.05  349.05  245.89  349.31  251.78  350.07  253.73  350.46
  261.54  352.98  269.37  353.98  275.21  354.83  284.97  357.71  288.84  358.36
  292.65  358.34  298.37  356.97  302.19  356.68  321.53  356.51  335.51  356.74
#Mann= 4 ,-1 , 0
       0     .03       0  170.61   .1326       0  236.92     .16       0
  269.37     .03       0
Bank Sta=157.72,251.78
XS Rating Curve= 0 ,0
Exp/Cntr=0.3,0.1

Type RM Length L Ch R = 1 ,1899.347,57.64,50.78,44.36
XS GIS Cut Line= 6
     318864.5217    4049604.0043     318836.7618    4049616.1435
     318822.7285    4049661.5572     318786.4815    4049661.8191
     318535.1352    4049663.6354     318485.4904    4049689.0356
#Sta/Elev= 30
       0  355.87    7.57  355.31   32.28  354.57   54.06  354.38   67.93     355
   77.83  355.89   85.46  355.14  114.08  354.53  132.05  353.53  152.02   353.7
  181.98  352.44  201.95  352.38  207.94  351.73  217.58  349.76  226.85  348.97
  237.39   345.1  268.76  344.85  284.45  345.35  292.29  347.16  295.84  348.63
  307.98  349.21  312.89  350.33  317.87  352.98  319.85  353.39  327.98  353.48
  351.56  354.22  367.42  356.17  387.34  356.98  409.25  359.24   421.2  359.81
#Mann= 4 ,-1 , 0
       0     .03       0  226.85   .1326       0  295.84     .16       0
  327.98     .03       0
Bank Sta=217.58,312.89
XS Rating Curve= 0 ,0
Exp/Cntr=0.3,0.1

Type RM Length L Ch R = 1 ,1848.563,50.87,50.36,55.83
XS GIS Cut Line= 5
        318833.2    4049579.1734     318687.6495    4049606.9305
      318588.211    4049617.5129     318528.8381    4049623.8314
      318492.478     4049637.791
#Sta/Elev= 30
       0  356.67   15.81  356.42   33.59  355.68   55.32  355.39      81  352.88
   138.3  351.31  142.25  350.95  147.11  349.74  159.94  349.18   161.9  348.55
  163.86  347.45  166.92  346.67   171.7  345.67  173.66  345.53  187.39  345.33
  195.23  345.59  218.76  345.23  226.61  345.65  234.45  347.39  237.27   348.3
  250.16  349.28  254.64  350.33  262.11  352.88   266.9  353.16  289.97  353.31
  297.93  353.71  307.88  354.65  323.46  357.19   333.2  358.32  346.83  359.05
#Mann= 4 ,-1 , 0
       0     .03       0  166.92   .1326       0  237.27     .16       0
   266.9     .03       0
Bank Sta=147.11,254.64
XS Rating Curve= 0 ,0
Exp/Cntr=0.3,0.1