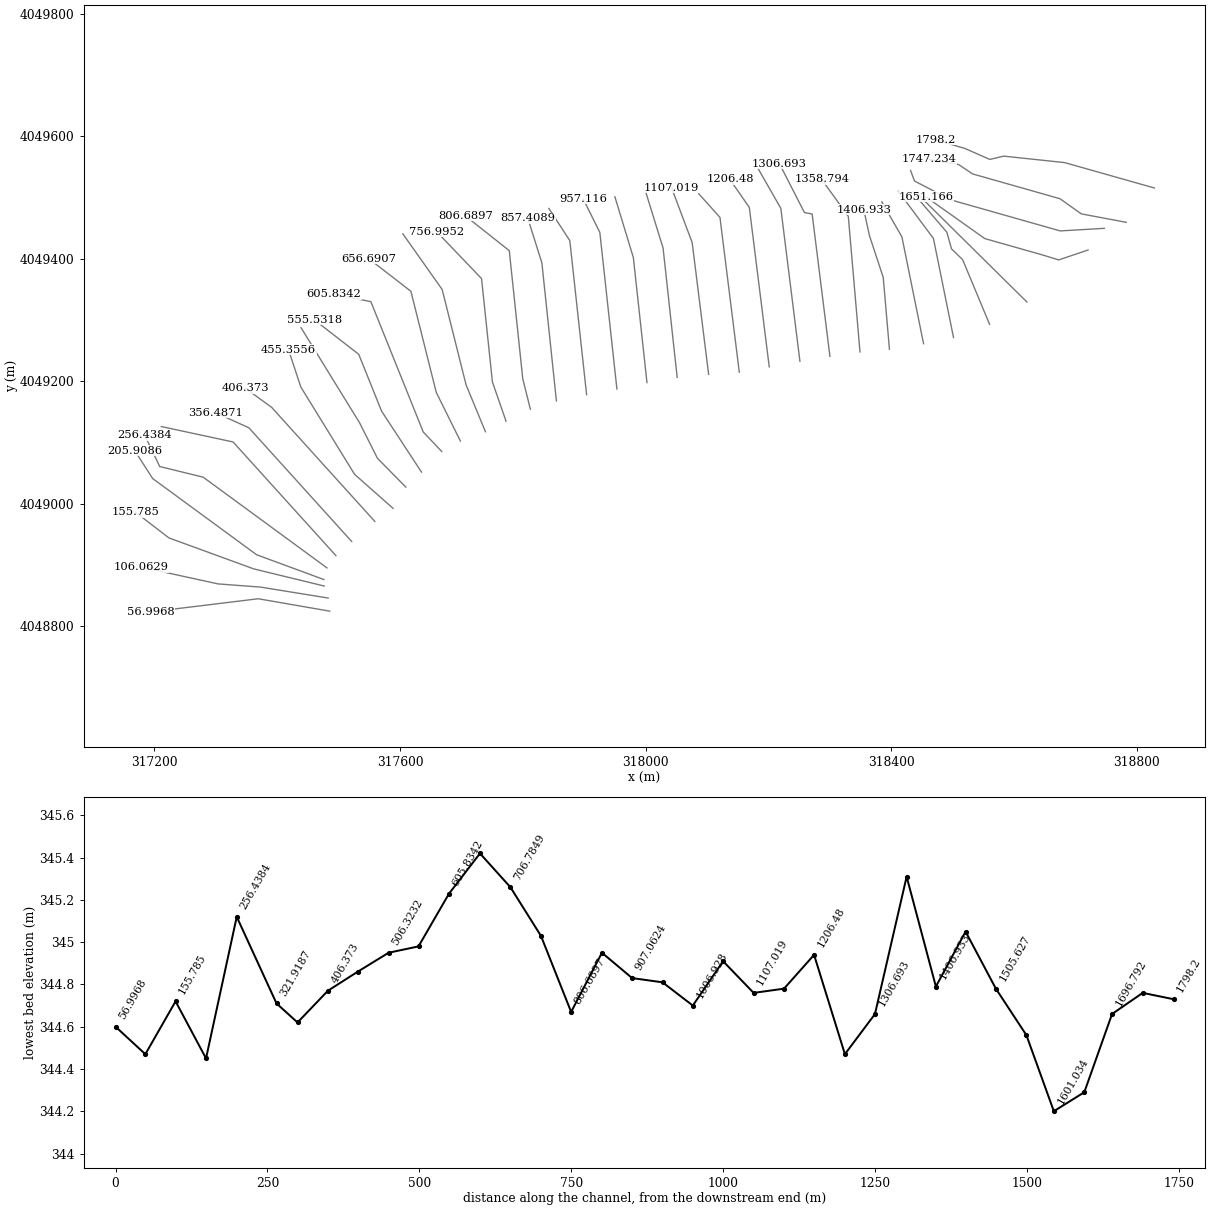
HEC-RAS study WBmod1D.prj: WBmod1D

--- WBmod1D.g02 (geometry) --- (continued)

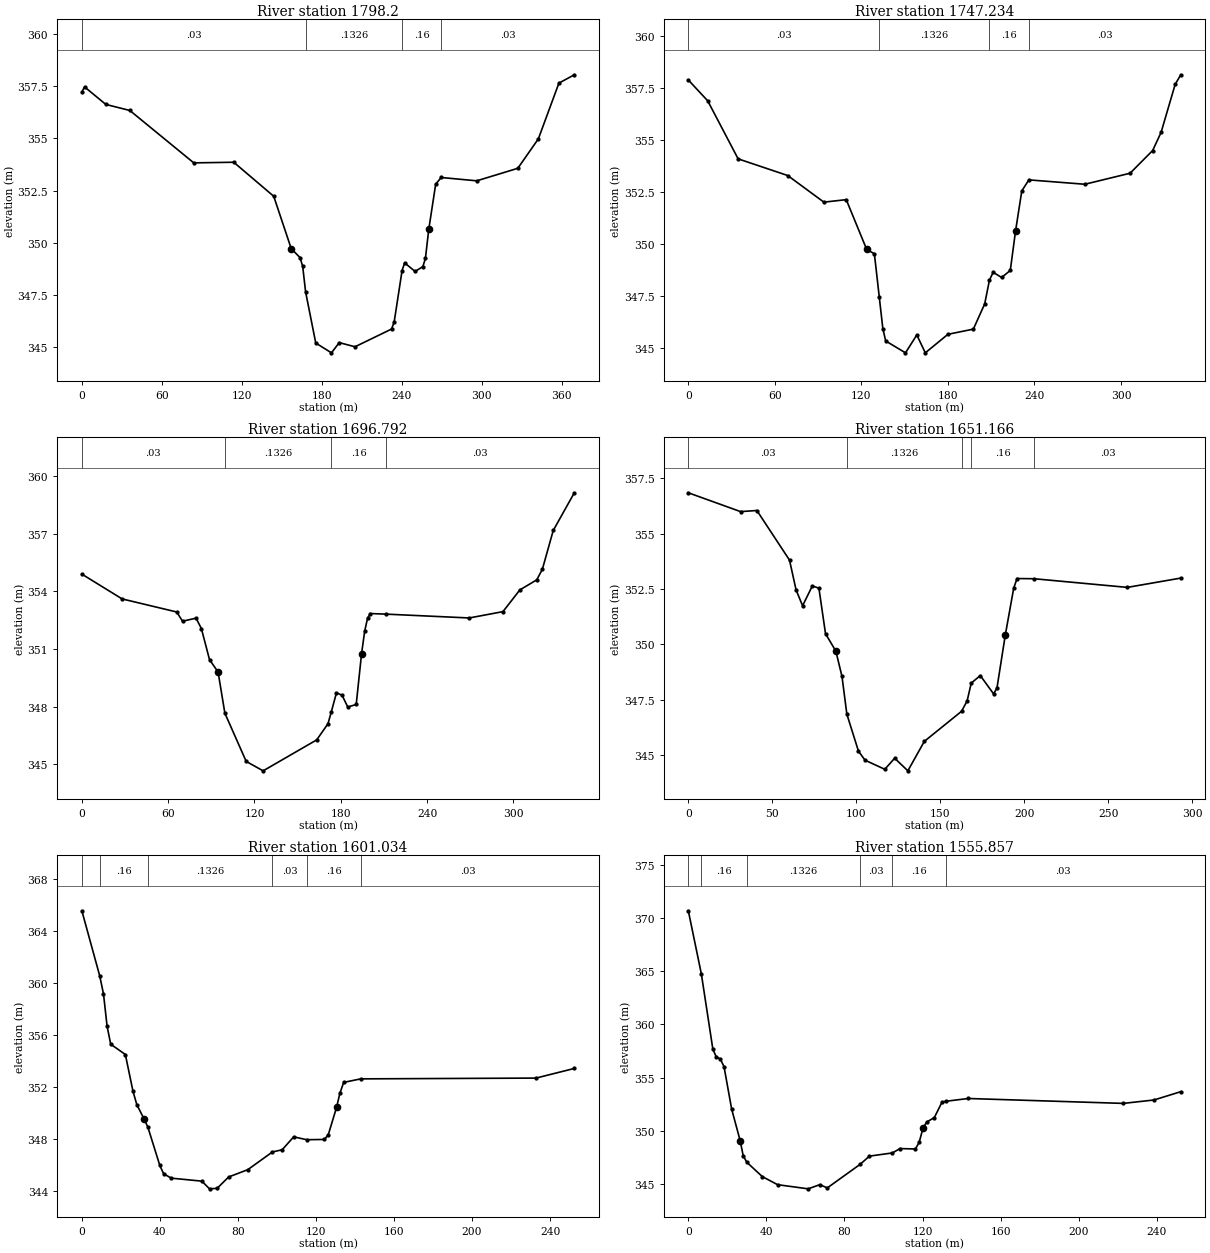
Type RM Length L Ch R = 1 ,1798.2  ,61.42,50.97,34.12
XS GIS Cut Line= 6
      318828.478    4049515.3933       318682.32    4049556.8509
     318582.8815    4049567.4333     318560.3773    4049562.0599
     318519.8959    4049579.9193     318471.8311     4049594.048
#Sta/Elev= 30
       0  357.22       2  357.47   17.99  356.63   35.98  356.34   83.96  353.83
  113.94  353.86  143.93  352.23  157.06  349.72  163.69  349.29  165.65  348.87
  167.84  347.65  175.45   345.2  187.22  344.73   193.1  345.22  204.87  345.02
  232.32  345.87  234.28  346.21   240.2  348.67  242.12  349.04  249.96  348.63
  255.78  348.86  257.71  349.25  260.21  350.64  265.42  352.81  269.54  353.13
  296.22  352.97  327.01  353.57  342.43  354.98  357.84  357.65  369.41  358.05
#Mann= 4 ,-1 , 0
       0     .03       0  167.84   .1326       0   240.2     .16       0
  269.54     .03       0
Bank Sta=157.06,260.21
XS Rating Curve= 0 ,0
Exp/Cntr=0.3,0.1

Type RM Length L Ch R = 1 ,1747.234,48.53,50.44,50.44
XS GIS Cut Line= 6
      318782.478    4049459.3949     318709.3482    4049473.1778
     318674.6335    4049497.9187     318532.3789    4049538.3598
     318509.5489    4049553.6942     318461.4479     4049562.048
#Sta/Elev= 30
       0  357.87   13.43  356.87   34.54  354.08   68.91  353.28      94     352
   109.5  352.12  123.66  349.73  129.01  349.52   132.4  347.44   134.9  345.91
  136.86  345.33  150.58  344.76  158.43  345.62  164.31  344.76  179.99  345.65
  197.64   345.9  205.48  347.11  208.81  348.26  211.37  348.63  217.25  348.38
  223.24  348.72  226.88  350.61  231.22  352.54  236.12  353.07  274.96  352.86
  306.31  353.39  321.94  354.48  327.79  355.35  337.56  357.66  341.46  358.12
#Mann= 4 ,-1 , 0
       0     .03       0   132.4   .1326       0  208.81     .16       0
  236.12     .03       0
Bank Sta=123.66,226.88
XS Rating Curve= 0 ,0
Exp/Cntr=0.3,0.1

Type RM Length L Ch R = 1 ,1696.792,45.87,45.63,39.26
XS GIS Cut Line= 6
     318746.9404    4049449.5856      318675.091    4049445.3481
     318564.6515    4049476.7446     318496.5699    4049496.0992
     318437.6668    4049526.8592     318431.3435     4049544.048
#Sta/Elev= 30
       0  354.89   27.99   353.6   65.98  352.92   69.97  352.44   79.38   352.6
   83.09  352.06   88.75  350.44    94.7   349.8   99.41  347.66  114.24  345.15
  126.01  344.66  163.26  346.27   171.1  347.11  173.39  347.72  176.99  348.72
  180.91  348.59  184.83  347.98  190.72  348.11  194.43  350.75  196.62  351.93
  198.59  352.59  200.55  352.84  211.25  352.81   269.3  352.61  292.75  352.94
  304.48  354.07   316.2  354.59  320.11  355.14  327.68  357.16  342.34  359.12
#Mann= 4 ,-1 , 0
       0     .03       0   99.41   .1326       0  173.39     .16       0
  211.25     .03       0
Bank Sta=94.7,194.43
XS Rating Curve= 0 ,0
Exp/Cntr=0.3,0.1

Type RM Length L Ch R = 1 ,1651.166,73.74,50.13,23.38
XS GIS Cut Line= 5
     318720.3453    4049414.1807      318672.478    4049397.9778
     318648.3637    4049405.5127     318552.1751    4049432.8579
      318456.478    4049500.8648
#Sta/Elev= 30
       0  356.84    31.1  355.99   40.82  356.04   60.25   353.8   64.14  352.46
   68.03  351.74   73.86  352.64   77.76  352.53   81.68  350.48   87.85  349.69
   91.49  348.55   94.38  346.85  101.29  345.18  105.21  344.77  116.98  344.36
  122.86  344.86   130.7  344.29  140.51  345.62  162.71  346.98     166  347.45
  168.44  348.25  173.84  348.59  181.77  347.76  183.76  348.03  188.72  350.42
  193.71  352.53   195.7  352.97  205.93  352.96  261.36  352.57   293.2  352.99
#Mann= 5 ,-1 , 0
       0     .03       0   94.38   .1326       0  162.71     .03       0
  168.44     .16       0  205.93     .03       0
Bank Sta=87.85,188.72
XS Rating Curve= 0 ,0
Exp/Cntr=0.3,0.1

Type RM Length L Ch R = 1 ,1601.034,64.6,45.18,24.81
XS GIS Cut Line= 5
     318620.8666    4049329.2663     318606.4135    4049343.5777
     318535.3553    4049413.9392     318498.7329    4049450.2027
     318441.4889    4049506.8855
#Sta/Elev= 30
       0  365.54    9.15  360.55   11.09  359.16   12.94  356.68   14.79   355.3
    22.3  354.51   26.22  351.68   28.18  350.66   31.96  349.54   33.81  348.95
   39.95     346   41.91  345.36   45.83  345.02   61.52  344.79   65.44   344.2
   69.36  344.24   75.24  345.11   85.05  345.67   97.69  347.03  102.69   347.2
  108.58  348.19  115.31  347.97   124.3  347.99  126.29  348.34  130.62  350.48
  132.23  351.52  134.22  352.37  142.97  352.64  232.79   352.7  252.44  353.44
#Mann= 6 ,-1 , 0
       0     .16       0    9.15     .16       0   33.81   .1326       0
   97.69     .03       0  115.31     .16       0  142.97     .03       0
Bank Sta=31.96,130.62
XS Rating Curve= 0 ,0
Exp/Cntr=0.3,0.1

Type RM Length L Ch R = 1 ,1555.857,59.12,50.23,34.94
XS GIS Cut Line= 6
     318560.0555    4049292.8238     318554.5329    4049306.0916
     318516.1047    4049398.4132     318498.0245    4049416.0875
     318490.4004    4049443.2773     318435.4596    4049507.3661
#Sta/Elev= 30
       0  370.66    6.68  364.73   12.57  357.67   14.37  356.92   16.33  356.77
   18.29  356.03   22.21  352.04   26.59  349.06    28.1  347.68   29.94  347.06
    37.9  345.71   45.74  344.95   61.43  344.56   67.31  344.95   71.23  344.65
   88.02  346.86    92.8  347.63  104.54  347.93  108.49  348.34  116.32   348.3
  118.26  348.92  120.25  350.27  122.15  350.83  126.04  351.25  129.93  352.68
  131.94  352.78  143.42  353.04  222.86  352.58  238.57   352.9  252.31  353.68
#Mann= 6 ,-1 , 0
       0     .16       0    6.68     .16       0   29.94   .1326       0
   88.02     .03       0  104.54     .16       0  131.94     .03       0
Bank Sta=26.59,120.25
XS Rating Curve= 0 ,0
Exp/Cntr=0.3,0.1

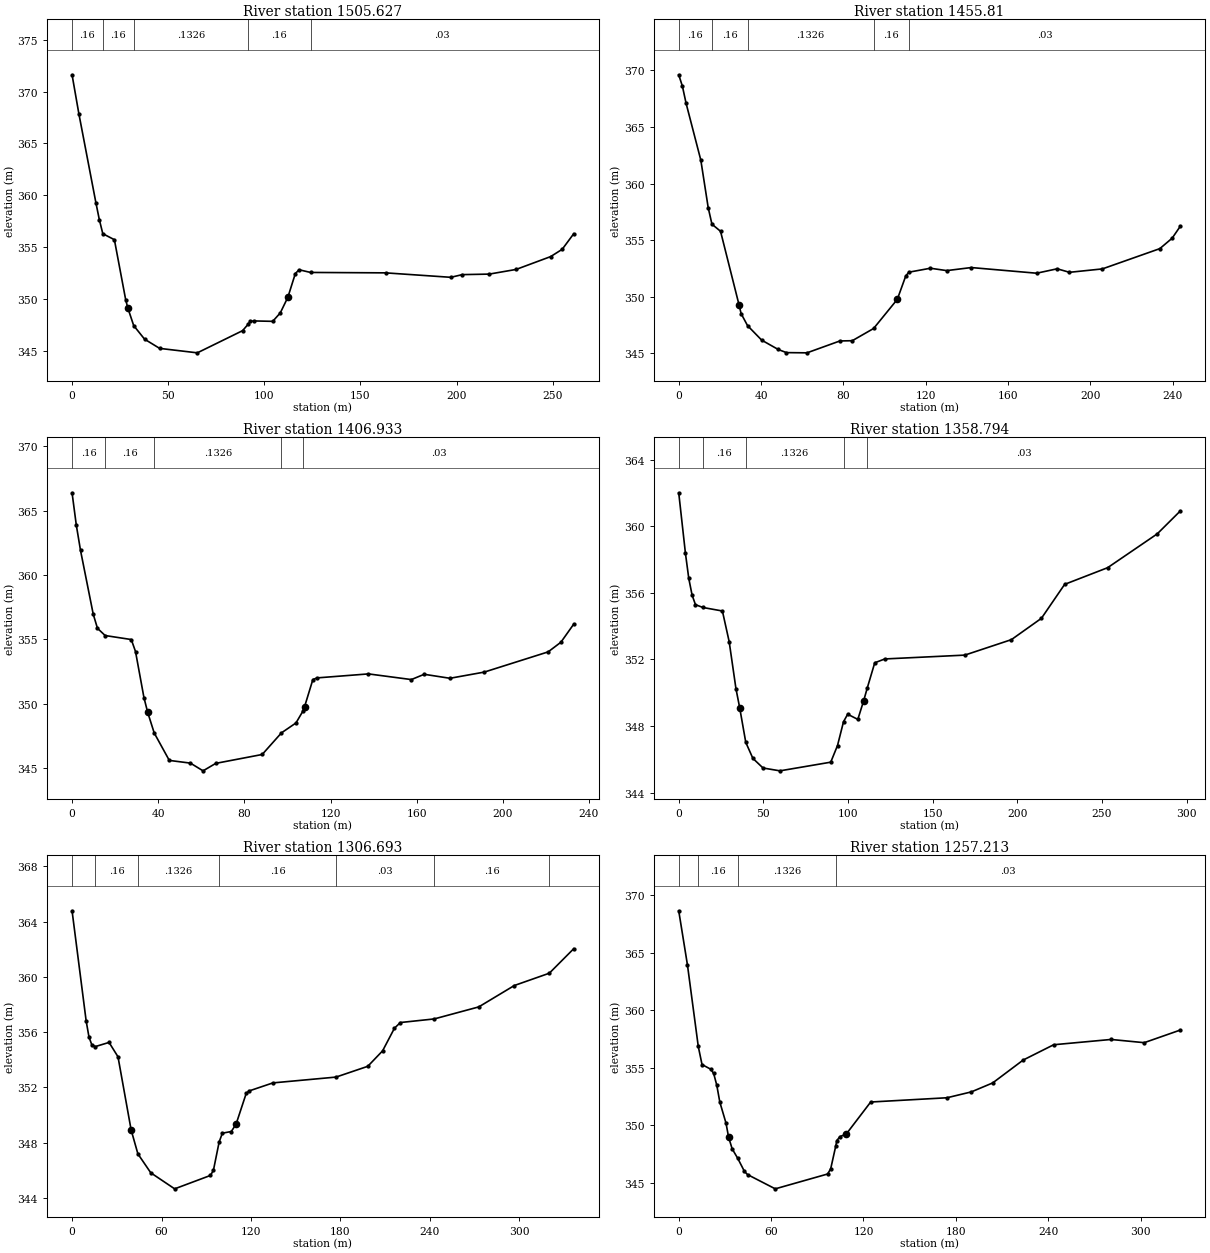
Type RM Length L Ch R = 1 ,1505.627,49.85,49.82,50.68
XS GIS Cut Line= 5
     318501.2791    4049271.3095      318498.468    4049285.2047
      318478.639    4049383.2191     318468.5513    4049433.0826
     318411.4033     4049510.048
#Sta/Elev= 30
       0  371.62    3.54  367.86    12.4  359.27   14.18  357.64   15.99  356.28
   22.02   355.7    27.9   349.9   29.01  349.11   32.06  347.41   37.71   346.1
   45.55  345.21   65.16  344.78   88.69  346.92   91.49  347.52   92.61  347.81
   94.57  347.86  104.37  347.82  108.29  348.63  112.24  350.14  116.13  352.43
  118.09   352.8  124.05  352.54  163.09   352.5     197  352.07     203  352.33
  216.98  352.38  230.96  352.83  248.93  354.07  254.92  354.77  260.91  356.27
#Mann= 5 ,-1 , 0
       0     .16       0   15.99     .16       0   32.06   .1326       0
   91.49     .16       0  124.05     .03       0
Bank Sta=29.01,112.24
XS Rating Curve= 0 ,0
Exp/Cntr=0.3,0.1

Type RM Length L Ch R = 1 ,1455.81 ,53.77,48.88,43.18
XS GIS Cut Line= 5
     318452.4803    4049261.2861     318449.6399    4049275.3265
     318429.8109    4049373.3408     318417.2051    4049435.6514
      318384.478    4049492.7732
#Sta/Elev= 30
       0   369.6    1.79  368.59    3.58  367.08   10.74  362.06   14.32  357.87
   16.14  356.41   20.32  355.78    29.3  349.29   30.32  348.51   33.45  347.45
   40.32  346.17   48.32  345.35   52.32  345.07   62.32  345.05   78.32   346.1
   84.32  346.12   94.69   347.2   106.2  349.77  110.32  351.84  111.82  352.17
  122.27  352.52  130.22  352.31  142.14  352.58  173.92  352.08  183.88  352.47
  189.87  352.16  205.83  352.46  233.76  354.25  239.74  355.17  243.73  356.23
#Mann= 5 ,-1 , 0
       0     .16       0   16.14     .16       0   33.45   .1326       0
   94.69     .16       0  111.82     .03       0
Bank Sta=29.3,106.2
XS Rating Curve= 0 ,0
Exp/Cntr=0.3,0.1

Type RM Length L Ch R = 1 ,1406.933,48.17,48.14,48.14
XS GIS Cut Line= 5
     318396.9074    4049252.1645     318395.3908    4049269.7952
     318386.8202    4049369.4273     318364.4181    4049437.5496
     318355.1249     4049480.048
#Sta/Elev= 30
       0  366.39    1.97  363.88    3.93  361.91    9.83  356.96    11.8  355.86
   15.37   355.3    27.5  354.99   29.46  354.06   33.38  350.48   35.12  349.33
   38.15  347.73   45.15   345.6   54.95  345.39   60.83  344.79   66.72  345.37
   88.28  346.06   97.23  347.74  103.97  348.51   107.3  349.46  107.97  349.78
  111.81  351.88  113.77  352.01  137.62  352.32  157.54  351.88  163.51  352.29
  175.46  351.98  191.38  352.46  221.05  354.03  226.98  354.78  232.91  356.18
#Mann= 5 ,-1 , 0
       0     .16       0   15.37     .16       0   38.15   .1326       0
   97.23     .16       0   107.3     .03       0
Bank Sta=35.12,107.97
XS Rating Curve= 0 ,0
Exp/Cntr=0.3,0.1

Type RM Length L Ch R = 1 ,1358.794,50.32,52.1,53.99
XS GIS Cut Line= 5
     318348.9606    4049247.8655     318347.4348    4049265.6028
     318338.8642    4049365.2348     318329.9237    4049469.1671
     318286.5775    4049529.3867
#Sta/Elev= 30
       0  362.01    3.96  358.38    5.93  356.87    7.91  355.86    9.89  355.29
   14.33  355.12    25.8  354.91    29.8  353.07    33.8  350.25   35.99  349.11
   39.61  347.02    43.8  346.06    49.8  345.48    59.8  345.31    89.8  345.83
    93.8  346.83   97.35  348.26    99.8  348.71   105.8   348.4  109.22  349.51
  111.42   350.3   115.8   351.8  121.74  352.03  168.98  352.26  196.53  353.19
  214.25  354.47  227.98  356.51  253.36  357.51  282.65  359.54  296.32  360.92
#Mann= 5 ,-1 , 0
       0     .16       0   14.33     .16       0   39.61   .1326       0
   97.35     .16       0  111.42     .03       0
Bank Sta=35.99,109.22
XS Rating Curve= 0 ,0
Exp/Cntr=0.3,0.1

Type RM Length L Ch R = 1 ,1306.693,49.48,49.48,49.49
XS GIS Cut Line= 6
     318300.0019    4049240.6546     318297.4281    4049261.3055
     318285.0601    4049360.5377      318271.045    4049472.9857
      318258.478    4049475.3072     318217.8011    4049555.0645
#Sta/Elev= 30
       0  364.79    9.46  356.81   11.35  355.65   13.24  355.09   15.63  354.96
   24.81  355.26   30.81  354.22   39.63  348.92   44.16  347.19   52.81  345.82
   68.81  344.66   92.81  345.63   94.81     346   98.65  348.05  100.81  348.69
  106.81  348.81  110.03  349.35  116.81  351.57  118.81  351.75  134.73  352.33
  177.03  352.75  198.34  353.53  208.28  354.65  216.24  356.29  220.21   356.7
  242.89  356.96  272.77  357.83  296.65  359.38   320.1  360.27  336.44  362.04
#Mann= 7 ,-1 , 0
       0     .16       0   15.63     .16       0   44.16   .1326       0
   98.65     .16       0  177.03     .03       0  242.89     .16       0
   320.1     .03       0
Bank Sta=39.63,110.03
XS Rating Curve= 0 ,0
Exp/Cntr=0.3,0.1

Type RM Length L Ch R = 1 ,1257.213,50.74,50.73,50.73
XS GIS Cut Line= 5
      318251.136    4049232.6627     318248.3288    4049255.1859
     318235.9608    4049354.4181     318220.0373    4049482.1784
     318183.2068    4049546.7632
#Sta/Elev= 30
       0  368.65    5.67  363.94    12.7  356.85   15.13  355.28   20.81  354.87
    22.7   354.5    24.7  353.49    26.7  352.01    30.7  350.19    32.4  348.96
    34.7  347.95   38.34  347.12    42.7  345.98    44.7  345.71    62.7  344.47
    96.7  345.76    98.7  346.21  101.95  348.17   102.7  348.67   104.7  349.01
   108.9  349.25  124.68  352.02   174.2  352.39  190.04   352.9  203.91  353.68
  223.72  355.67  243.52     357  280.79  357.46  302.32  357.18  325.79  358.28
#Mann= 4 ,-1 , 0
       0     .16       0    12.7     .16       0   38.34   .1326       0
  101.95     .03       0
Bank Sta=32.4,108.9
XS Rating Curve= 0 ,0
Exp/Cntr=0.3,0.1

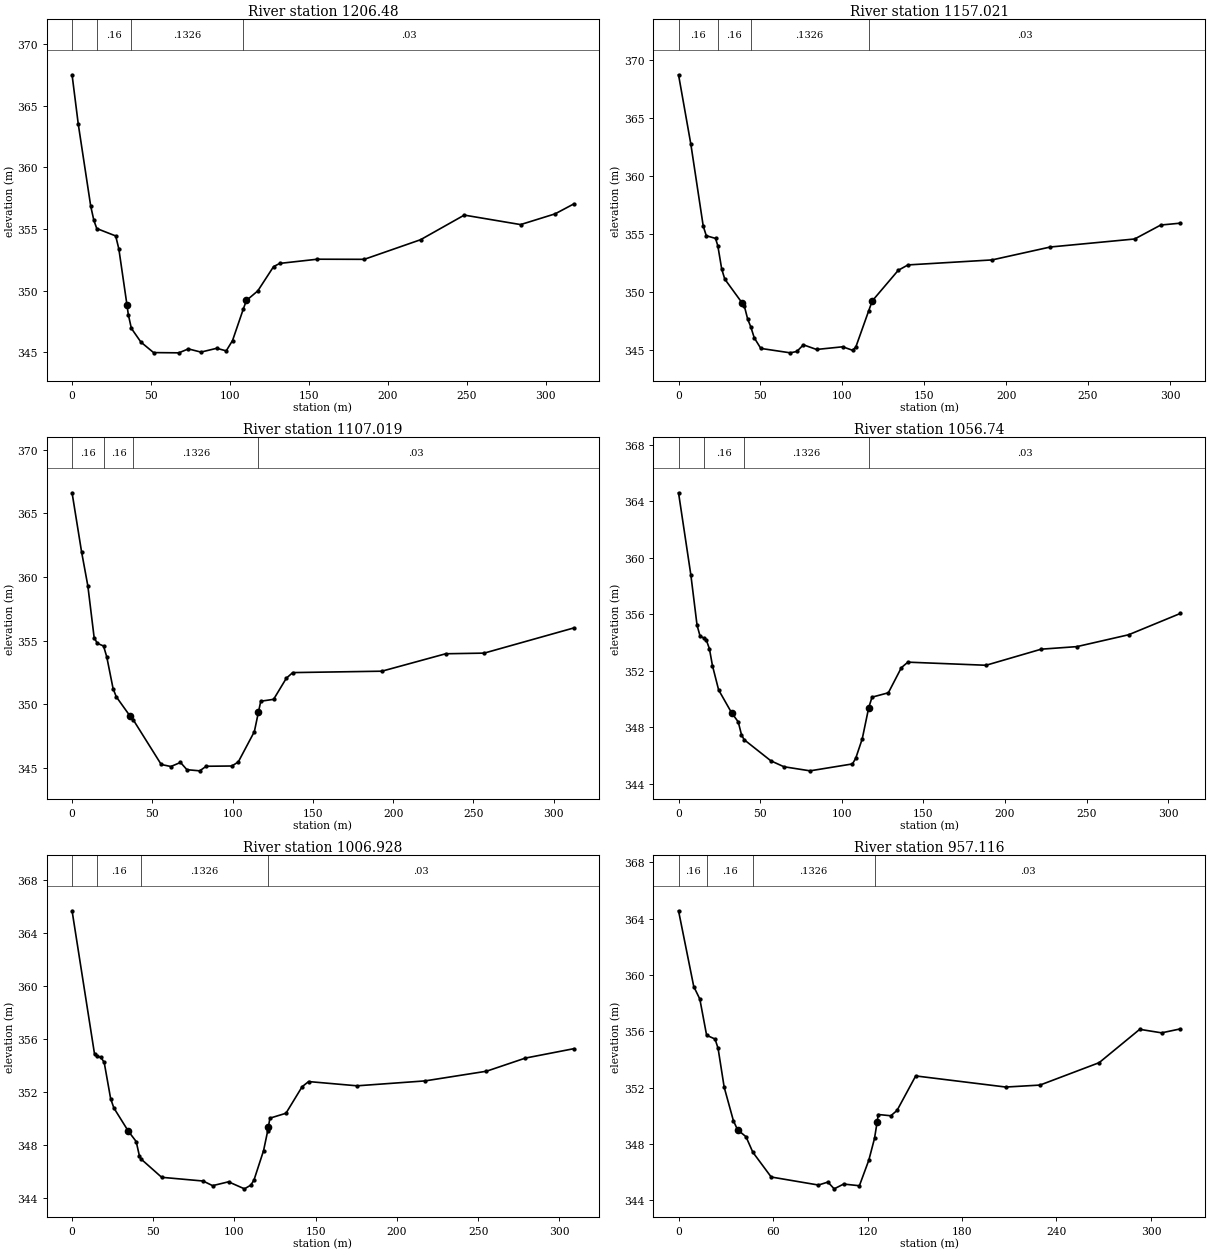
Type RM Length L Ch R = 1 ,1206.48 ,49.47,49.46,49.46
XS GIS Cut Line= 5
     318201.1528     4049223.494     318197.9849    4049248.9113
     318185.6169    4049348.1435     318168.7242    4049483.6797
     318137.1618    4049529.3642
#Sta/Elev= 30
       0  367.51    3.94  363.49   11.82  356.84   13.79   355.7   15.63  355.03
   27.61  354.43   29.61  353.38   34.74  348.85   35.61  348.05   37.54  346.93
   43.61  345.81   51.61  344.96   67.61  344.94   73.61  345.26   81.61     345
   91.61  345.31   97.61   345.1  101.61  345.94  108.52  348.53  110.39  349.19
  117.61  349.97  127.59  351.94  131.55   352.2  155.31  352.54     185  352.53
  220.63  354.12  248.34  356.12  284.01  355.35  305.83  356.22  317.73  357.03
#Mann= 4 ,-1 , 0
       0     .16       0   15.63     .16       0   37.54   .1326       0
  108.52     .03       0
Bank Sta=34.74,110.39
XS Rating Curve= 0 ,0
Exp/Cntr=0.3,0.1

Type RM Length L Ch R = 1 ,1157.021,50.02,50,50
XS GIS Cut Line= 5
     318152.3972    4049214.7814     318148.9058    4049242.7942
     318136.5378    4049342.0264     318120.9116     4049467.401
     318086.4117    4049505.9817
#Sta/Elev= 30
       0  368.69    7.53  362.71   15.06  355.69   16.94  354.85   22.58  354.62
   23.99  353.98   26.35  351.99   28.23  351.12   38.82  349.07   40.23  348.77
   42.23  347.67   44.07  347.03   46.23  346.07   50.23  345.16   68.23  344.78
   72.23   344.9   76.23  345.47   84.23  345.07  100.23   345.3  106.23     345
  108.23  345.28     116  348.36  118.28  349.25  134.15  351.88  140.07  352.34
   191.4  352.77  226.94  353.88  278.46  354.57  294.39  355.77  306.33  355.93
#Mann= 4 ,-1 , 0
       0     .16       0   23.99     .16       0   44.07   .1326       0
     116     .03       0
Bank Sta=38.82,118.28
XS Rating Curve= 0 ,0
Exp/Cntr=0.3,0.1

Type RM Length L Ch R = 1 ,1107.019,51.07,50.28,49.51
XS GIS Cut Line= 5
     318102.4446     4049211.278     318099.2874      4049236.61
     318086.9194    4049335.8422     318075.6384    4049426.3538
     318042.0055     4049516.048
#Sta/Elev= 30
       0  366.61    5.89  361.99    9.82   359.3   13.75  355.23   15.71  354.78
    19.6  354.57    21.6  353.72   25.53  351.23   27.53  350.58   36.26  349.04
   38.25  348.74   55.53  345.26   61.53   345.1   67.53  345.42   71.53  344.85
   79.53  344.76   83.53  345.12   99.53  345.14  103.53  345.46  113.53  347.84
     116  349.33   116.1  349.39  117.53  350.23  125.53  350.38  133.46  352.04
  137.43  352.48  192.95  352.59  232.71  353.96  256.65  354.01  312.53  355.99
#Mann= 4 ,-1 , 0
       0     .16       0    19.6     .16       0   38.25   .1326       0
     116     .03       0
Bank Sta=36.26,116.1
XS Rating Curve= 0 ,0
Exp/Cntr=0.3,0.1

Type RM Length L Ch R = 1 ,1056.74 ,49.82,49.81,49.82
XS GIS Cut Line= 5
     318051.2251    4049206.3175     318048.5678    4049230.7397
      318037.751    4049330.1529     318028.2557    4049417.4204
     318000.2192    4049508.3068
#Sta/Elev= 30
       0  364.61    7.56  358.78   11.34  355.23   13.23  354.44   15.36  354.33
   17.01  354.18    18.9  353.57   20.79  352.36   24.57  350.64   32.48  349.03
   36.57  348.38   38.57  347.47   40.16  347.12   56.57  345.62   64.57   345.2
   80.57  344.91  106.57   345.4  108.57   345.8  112.57  347.18  116.47  349.35
  116.51  349.38  118.57  350.13  128.56  350.44  136.54  352.22  140.53  352.61
  188.41  352.39  222.26  353.53  244.05  353.71  275.76  354.55  307.46  356.06
#Mann= 4 ,-1 , 0
       0     .16       0   15.36     .16       0   40.16   .1326       0
  116.47     .03       0
Bank Sta=32.48,116.51
XS Rating Curve= 0 ,0
Exp/Cntr=0.3,0.1

Type RM Length L Ch R = 1 ,1006.928,49.82,49.81,49.82
XS GIS Cut Line= 5
     318002.0452    4049197.8074     317999.0482    4049225.3516
     317988.2314    4049324.7649     317979.8324    4049401.9561
     317949.7777    4049501.1004
#Sta/Elev= 30
       0  365.67   13.85  354.85    15.6  354.69   17.81  354.61   19.79  354.23
   23.75   351.5   25.73   350.8   34.68  349.04   39.47  348.27   41.43   347.2
   42.46  346.95   55.16  345.57   80.65  345.29   86.53  344.94   96.33  345.23
  106.14   344.7  110.06  344.98  112.02  345.37   117.9  347.58  120.38  349.03
  120.92   349.4  121.82  350.03  131.69   350.4  141.64   352.4  145.63  352.79
  175.49  352.47  217.31  352.84  255.16  353.57  279.07  354.56  308.95  355.27
#Mann= 4 ,-1 , 0
       0     .16       0    15.6     .16       0   42.46   .1326       0
  120.38     .03       0
Bank Sta=34.68,120.92
XS Rating Curve= 0 ,0
Exp/Cntr=0.3,0.1

Type RM Length L Ch R = 1 ,957.116 ,50.06,50.05,50.06
XS GIS Cut Line= 5
     317953.0808     4049187.315     317949.5284    4049219.9635
     317938.7116    4049319.3767      317925.265    4049442.9587
     317897.9487     4049498.048
#Sta/Elev= 30
       0  364.56    9.66  359.18   13.52  358.29   17.83  355.72   23.18  355.45
   25.11  354.79   28.98  352.03   34.84  349.65   37.46  349.01   42.84  348.51
   47.18  347.41   58.84  345.65   88.84  345.08   94.84  345.29   98.84  344.81
  104.84  345.15  114.84  345.03  120.84  346.85  124.44  348.39  126.11  349.55
  126.84  350.09  134.81     350  138.76  350.38   150.6  352.83  207.82  352.04
  229.53  352.18  267.07  353.77  292.86  356.14  306.74  355.89  318.64  356.17
#Mann= 4 ,-1 , 0
       0     .16       0   17.83     .16       0   47.18   .1326       0
  124.44     .03       0
Bank Sta=37.46,126.11
XS Rating Curve= 0 ,0
Exp/Cntr=0.3,0.1

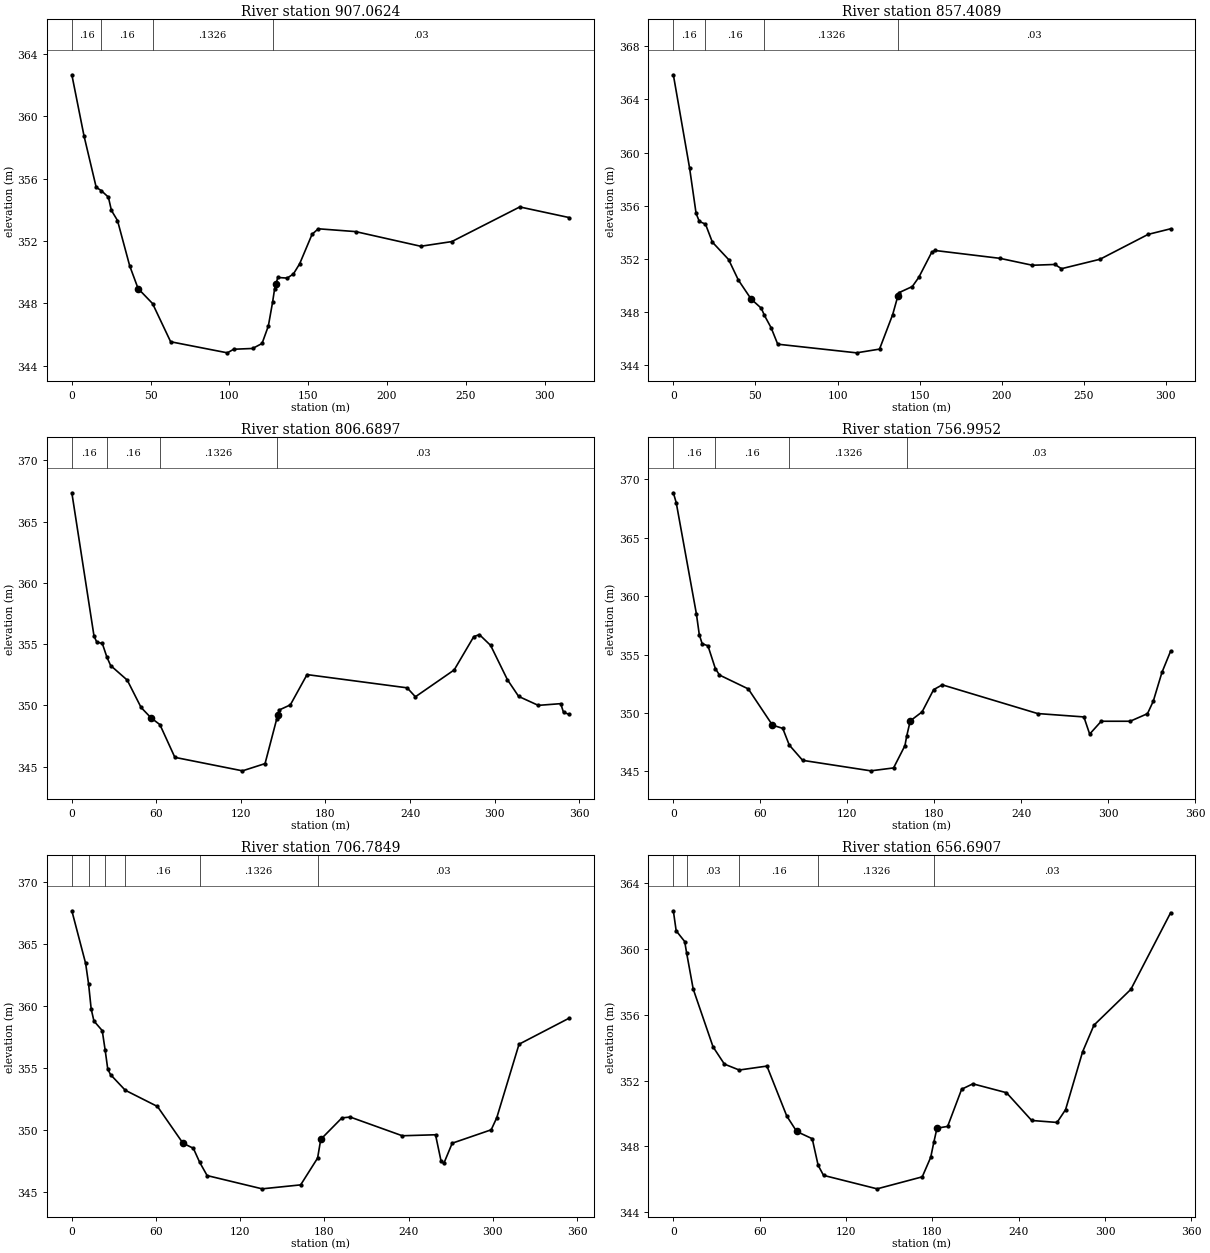
Type RM Length L Ch R = 1 ,907.0624,49.85,49.65,49.47
XS GIS Cut Line= 5
     317903.7384    4049178.0632     317899.7684    4049214.5493
     317888.9516    4049313.9625      317876.378    4049429.5207
     317842.2756     4049482.048
#Sta/Elev= 30
       0  362.65    7.73  358.73   15.45  355.44   18.62  355.23   23.18  354.81
   25.11  353.96   28.97  353.31    36.7  350.41   42.04  348.95   51.21  347.99
    62.7  345.54    98.7  344.83   102.7  345.06   114.7  345.11   120.7  345.43
   124.7  346.55   127.4  348.08   128.7  348.95  129.53  349.24   130.7  349.66
   136.7  349.62  140.64  349.89  144.58  350.54  152.46  352.43   156.4  352.78
  180.05   352.6  221.42  351.66  241.12  351.96  284.25  354.18  315.57   353.5
#Mann= 4 ,-1 , 0
       0     .16       0   18.62     .16       0   51.21   .1326       0
   127.4     .03       0
Bank Sta=42.04,129.53
XS Rating Curve= 0 ,0
Exp/Cntr=0.3,0.1

Type RM Length L Ch R = 1 ,857.4089,50.16,50.72,50.73
XS GIS Cut Line= 5
      317854.557    4049167.9495     317850.2111    4049209.2911
     317839.7565    4049308.7431     317830.8695    4049393.2829
     317807.9564     4049466.048
#Sta/Elev= 30
       0  365.84     9.9  358.83   13.86  355.42   15.84  354.82   19.58  354.62
   23.75  353.27   33.65  351.96   39.59  350.42   47.37  348.99   53.57   348.3
   55.48  347.76   59.57  346.83   63.57   345.6  111.57  344.95  125.57  345.23
  133.57  347.82   136.7   349.2  136.72   349.2  137.57  349.48  145.52  349.93
  149.48  350.62  157.38  352.51  159.36  352.64   198.9  352.05  218.67  351.53
  232.44  351.59  236.36  351.27  259.83  351.98  289.17  353.85  302.86  354.27
#Mann= 4 ,-1 , 0
       0     .16       0   19.58     .16       0   55.48   .1326       0
  136.72     .03       0
Bank Sta=47.37,136.7
XS Rating Curve= 0 ,0
Exp/Cntr=0.3,0.1

Type RM Length L Ch R = 1 ,806.6897,49.09,49.69,49.7
XS GIS Cut Line= 6
     317812.1216    4049154.4044     317799.7698    4049203.9886
     317789.3152    4049303.4406     317780.8488    4049383.9792
     317777.7866    4049413.1092     317706.1531     4049470.048
#Sta/Elev= 30
       0  367.35   15.72  355.67   17.69  355.17   21.62  355.06   24.86  353.95
   27.52  353.26   39.31  352.07   49.13  349.84   56.28  348.98   62.49  348.44
    73.1  345.77   121.1  344.67   137.1  345.26  145.43  348.92  146.13  349.21
   147.1  349.63  155.05  350.05   166.9  352.52  237.94  351.44   243.8  350.71
  271.32   352.9  285.24  355.62  289.22  355.78  297.18   354.9  309.11   352.1
  317.07  350.74     331  350.01  346.91  350.15   348.9  349.44  352.88  349.28
#Mann= 4 ,-1 , 0
       0     .16       0   24.86     .16       0   62.49   .1326       0
  145.43     .03       0
Bank Sta=56.28,146.13
XS Rating Curve= 0 ,0
Exp/Cntr=0.3,0.1

Type RM Length L Ch R = 1 ,756.9952,42.23,50.21,57.24
XS GIS Cut Line= 5
      317772.478    4049134.8811     317750.3476    4049198.7932
      317739.893    4049298.2453     317732.6019    4049367.6036
       317659.55     4049444.048
#Sta/Elev= 30
       0  368.86    1.99  368.01   15.91  358.48    17.9   356.7   19.89  355.92
   23.87  355.75   28.96   353.8   31.83  353.24   51.72  352.05   68.36  348.95
   75.48  348.67   79.98  347.24    89.2  345.93  136.26  345.03  151.95  345.28
  159.79  347.19  161.02  348.01  163.44  349.31  171.62  350.08  179.59  351.99
  185.57   352.4  251.34  349.94  283.26  349.65  287.25  348.18  295.23  349.28
  315.18  349.28  327.15  349.93  331.14     351  337.13  353.47  343.11  355.29
#Mann= 4 ,-1 , 0
       0     .16       0   28.96     .16       0   79.98   .1326       0
  161.02     .03       0
Bank Sta=68.36,163.44
XS Rating Curve= 0 ,0
Exp/Cntr=0.3,0.1

Type RM Length L Ch R = 1 ,706.7849,49.54,50.09,50.1
XS GIS Cut Line= 5
     317738.9719    4049117.5541     317707.4606    4049193.9858
     317683.1854    4049290.9947     317668.4697     4049349.802
      317604.478    4049440.5994
#Sta/Elev= 30
       0  367.68    9.84  363.43   11.95  361.76   13.78  359.76   15.75  358.79
   21.65  358.02   23.75  356.44   25.59  354.92   27.56  354.47   38.07  353.21
   61.02   351.9   79.18  348.94   86.59  348.53   91.06  347.41    96.4  346.33
  135.61  345.26  163.06  345.58  175.13  347.74  177.38  349.25  192.45  350.98
  198.32  351.05  235.47  349.54  259.16  349.62  263.13  347.49  265.11  347.32
  271.06  348.94  298.83  350.02   302.8  350.99  318.67  356.92  354.37  359.02
#Mann= 6 ,-1 , 0
       0     .16       0   11.95      .1       0   23.75     .03       0
   38.07     .16       0   91.06   .1326       0  175.13     .03       0
Bank Sta=79.18,177.38
XS Rating Curve= 0 ,0
Exp/Cntr=0.3,0.1

Type RM Length L Ch R = 1 ,656.6907,44.6,50.86,57.75
XS GIS Cut Line= 5
     317698.2016    4049102.3244     317658.8648    4049181.8254
     317634.5896    4049278.8343       317617.57    4049346.8484
     317548.9397     4049400.048
#Sta/Elev= 30
       0  362.34    1.97  361.12    7.88  360.47    9.28  359.75    13.8  357.58
    27.6  354.06   35.48  353.01   45.79  352.65   65.05  352.89   78.84  349.85
   85.74  348.91   96.54  348.47  100.65  346.85  104.39  346.24  141.64  345.42
  173.01  346.15   178.9  347.34  181.04  348.25  183.25  349.11  190.65  349.22
  200.39  351.48  208.18  351.81  231.55  351.27  249.07  349.58  266.71  349.46
  272.63  350.24  284.47  353.76  292.36  355.38  318.02  357.56  345.65  362.22
#Mann= 5 ,-1 , 0
       0      .1       0    9.28     .03       0   45.79     .16       0
  100.65   .1326       0  181.04     .03       0
Bank Sta=85.74,183.25
XS Rating Curve= 0 ,0
Exp/Cntr=0.3,0.1

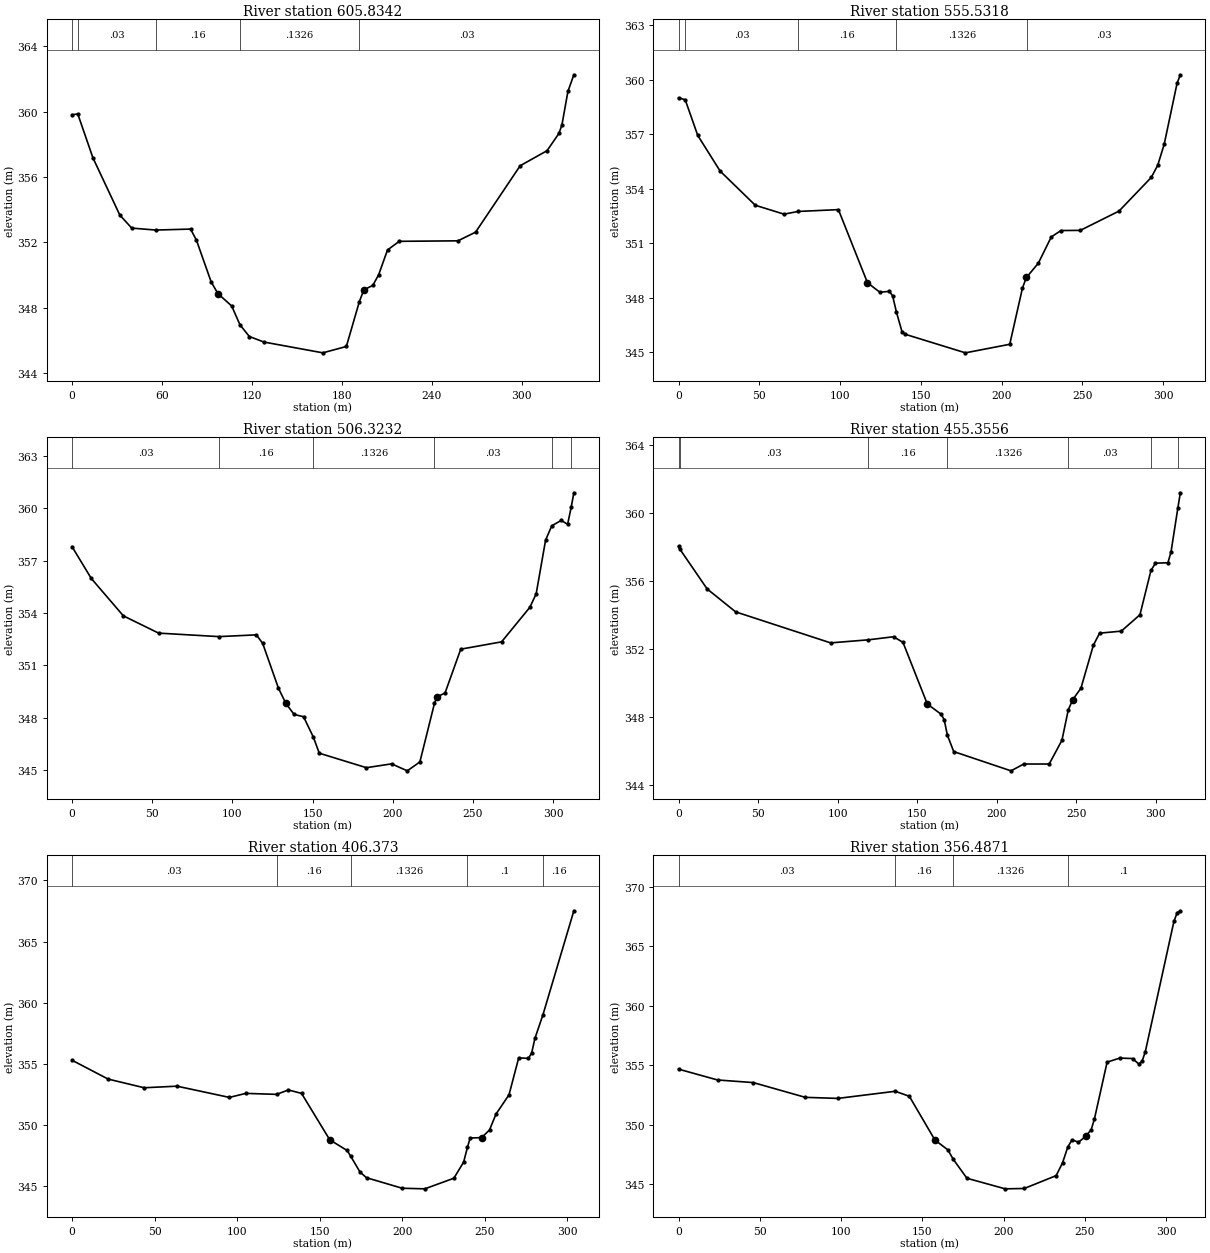
Type RM Length L Ch R = 1 ,605.8342,48.84,50.3,50.66
XS GIS Cut Line= 6
     317667.7723    4049085.3423     317637.7067    4049117.1515
     317616.5599    4049169.8702     317579.3309    4049262.6819
     317552.3663    4049329.9044     317491.9297     4049342.048
#Sta/Elev= 30
       0  359.81     3.8  359.86   13.93  357.17   31.83  353.67   39.79  352.87
   55.81  352.75   79.03  352.81   82.94  352.13   92.74  349.58   97.23  348.86
  106.45   348.1  111.96  346.95  118.22  346.23  128.02  345.89  167.24  345.23
  182.92  345.62  191.57  348.36  194.58  349.09  200.57  349.36  204.49  350.02
  210.36  351.53  218.19  352.06  257.34  352.09  269.09  352.62  298.85  356.69
  316.75  357.61   324.7  358.67  326.69  359.19  330.67  361.24  334.64  362.26
#Mann= 5 ,-1 , 0
       0      .1       0     3.8     .03       0   55.81     .16       0
  111.96   .1326       0  191.57     .03       0
Bank Sta=97.23,194.58
XS Rating Curve= 0 ,0
Exp/Cntr=0.3,0.1

Type RM Length L Ch R = 1 ,555.5318,41.59,49.21,57.69
XS GIS Cut Line= 4
     317634.8213    4049051.7047     317569.8734    4049151.1431
     317532.6444    4049243.9548     317460.1466    4049300.3794
#Sta/Elev= 30
       0  358.99    4.13  358.89   11.88  356.93   25.73  354.97   47.51  353.09
   65.32   352.6   74.06  352.75   98.97  352.85  116.98  348.83  124.65  348.31
  130.53  348.36   132.5  348.12  134.89  347.22  138.38  346.13  140.34     346
  177.59  344.98  205.04  345.45  212.89  348.53  215.34  349.13  215.84  349.17
  222.76  349.91  230.75  351.35  236.74   351.7  248.73  351.71  272.69  352.77
  292.66  354.62  296.66  355.29  300.65  356.44  308.64   359.8  310.64  360.26
#Mann= 5 ,-1 , 0
       0      .1       0    4.13     .03       0   74.06     .16       0
  134.89   .1326       0  215.84     .03       0
Bank Sta=116.98,215.34
XS Rating Curve= 0 ,0
Exp/Cntr=0.3,0.1

Type RM Length L Ch R = 1 ,506.3232,50.4,50.97,48.95
XS GIS Cut Line= 5
     317609.3383    4049027.1877     317563.0994    4049074.2391
     317534.0661     4049132.045     317481.7199      4049217.25
     317438.6291    4049287.3899
#Sta/Elev= 30
       0  357.79   11.99  355.97   31.98  353.83   53.97  352.84   91.56  352.64
  114.97  352.74  118.89  352.25   128.7  349.69  133.29  348.82   138.5  348.18
  144.38  348.05  150.55  346.87  154.19  345.96   183.6  345.13  199.28  345.35
  209.09  344.95  216.93  345.46  226.02  348.81  227.49  349.18  232.62  349.41
  242.42  351.92   267.9  352.34  285.54  354.32  289.46  355.09  295.34  358.17
  299.22  358.99  305.14   359.3  309.06  359.07   311.3  360.05  312.97  360.88
#Mann= 6 ,-1 , 0
       0     .03       0   91.56     .16       0  150.55   .1326       0
  226.02     .03       0  299.22      .1       0   311.3     .16       0
Bank Sta=133.29,227.49
XS Rating Curve= 0 ,0
Exp/Cntr=0.3,0.1

Type RM Length L Ch R = 1 ,455.3556,38.64,48.98,62.83
XS GIS Cut Line= 5
      317588.478    4048992.5728     317525.8222    4049048.0972
     317490.6391    4049105.3655      317438.293    4049190.5704
     317418.1895    4049251.7595
#Sta/Elev= 30
       0  358.03     .63   357.9   17.94  355.54   35.88  354.19   95.58  352.37
  119.33  352.55  135.12  352.73  141.05   352.4  156.35  348.78  164.93  348.19
  166.93  347.87  168.93  346.96  172.93  345.99  208.93  344.86  216.93  345.26
  232.93  345.26  240.93  346.65  244.93  348.44  247.75  349.04  252.88  349.71
  260.69  352.23  264.59  352.94  278.25  353.06  289.96  354.02  296.89  356.62
  299.72  357.05  307.53  357.07  309.48   357.7  313.76  360.27  315.34  361.18
#Mann= 7 ,-1 , 0
       0      .1       0     .63     .03       0  119.33     .16       0
  168.93   .1326       0  244.93     .03       0  296.89      .1       0
  313.76     .16       0
Bank Sta=156.35,247.75
XS Rating Curve= 0 ,0
Exp/Cntr=0.3,0.1

Type RM Length L Ch R = 1 ,406.373 ,49.95,49.89,51.55
XS GIS Cut Line= 4
     317558.8118    4048971.2016     317457.7115    4049083.2281
     317390.7139    4049157.4664     317347.8281    4049188.6979
#Sta/Elev= 30
       0  355.29   21.84  353.75   43.68  353.04   63.54  353.17   95.31  352.25
  105.23  352.58  123.87   352.5  131.05  352.86  138.99  352.58   156.1  348.78
  166.59  347.91  168.82  347.43  174.43  346.14  178.35  345.68  199.92  344.82
  213.65  344.77  231.29  345.64  237.18  346.96   239.5  348.17   241.1  348.93
   248.1  348.96  252.87  349.59   256.8  350.89  264.66  352.46  270.55  355.49
  276.45  355.44  278.41   355.9  280.37  357.08  285.27  359.03  303.95  367.52
#Mann= 5 ,-1 , 0
       0     .03       0  123.87     .16       0  168.82   .1326       0
   239.5      .1       0  285.27     .16       0
Bank Sta=156.1,248.1
XS Rating Curve= 0 ,0
Exp/Cntr=0.3,0.1

Type RM Length L Ch R = 1 ,356.4871,34.58,34.57,36.99
XS GIS Cut Line= 4
     317521.1733    4048938.4483      317420.677    4049049.8057
     317353.6794     4049124.044     317300.1798    4049148.3462
#Sta/Elev= 30
       0  354.68      24  353.77      46  353.55      78  352.31      98  352.22
  133.35  352.82     142   352.4  157.77  348.72  165.69   347.9  169.11  347.09
  177.45  345.51  200.98  344.62  212.74  344.65  232.35  345.73  236.27   346.8
  239.56  348.15  242.16  348.74  246.08  348.54  250.45  349.02  253.92   349.6
  255.88  350.48  263.71  355.27  271.55  355.61  279.38  355.57   283.3   355.1
  285.26  355.36  287.21  356.14  304.84  367.11   306.8  367.82  308.76  367.99
#Mann= 4 ,-1 , 0
       0     .03       0  133.35     .16       0  169.11   .1326       0
  239.56      .1       0
Bank Sta=157.77,250.45
XS Rating Curve= 0 ,0
Exp/Cntr=0.3,0.1

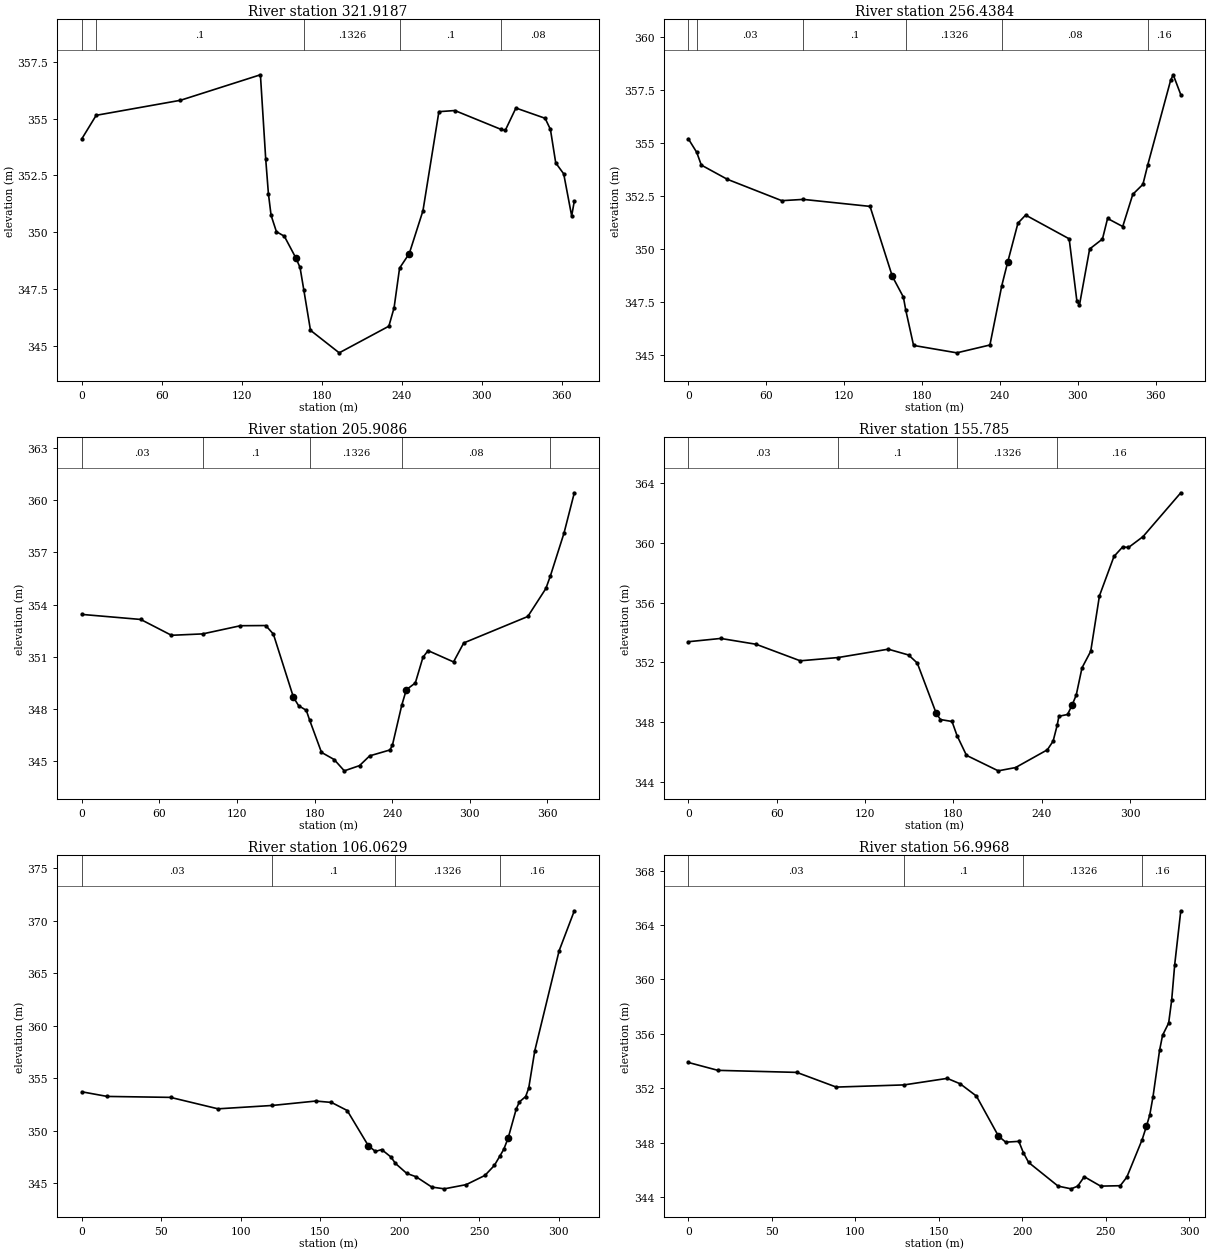
Type RM Length L Ch R = 1 ,321.9187,54.12,65.48,74.13
XS GIS Cut Line= 4
     317495.5103    4048915.2883      317395.014    4049026.6457
     317328.0164     4049100.884     317211.1221     4049126.048
#Sta/Elev= 30
       0  354.11   10.75  355.14      74   355.8     134  356.92     138   353.2
     140   351.7     142  350.75     146  350.03  151.96  349.83  160.57  348.88
  163.73  348.46  166.63  347.45  171.57   345.7  193.14  344.71  230.39  345.88
  234.31  346.69  238.43  348.43  245.71  349.07  255.98  350.95  267.94   355.3
  279.89  355.35  314.65  354.52  317.76  354.48  325.73  355.46  347.65  355.01
  351.64  354.52  355.62  353.05   361.6  352.57  367.58  350.72  369.57  351.38
#Mann= 5 ,-1 , 0
       0     .03       0   10.75      .1       0  166.63   .1326       0
  238.43      .1       0  314.65     .08       0
Bank Sta=160.57,245.71
XS Rating Curve= 0 ,0
Exp/Cntr=0.3,0.1

Type RM Length L Ch R = 1 ,256.4384,50.69,50.53,48.8
XS GIS Cut Line= 5
     317480.8344    4048895.3885      317359.947    4048984.1927
     317279.3553    4049043.3956      317208.478     4049060.836
     317184.1717    4049111.7417
#Sta/Elev= 30
       0  355.22    6.48  354.58      10  353.98      30  353.31      72   352.3
    88.6  352.36     140  352.03  157.17  348.73  165.69  347.75   167.5  347.14
  173.53  345.47  206.86  345.12  232.35  345.49   241.5  348.29     246  349.39
  253.95  351.24  259.86  351.62   293.4   350.5  299.32  347.58  301.29  347.36
  309.18  350.02  319.05  350.49  322.99  351.46  334.66  351.08  342.44   352.6
  350.22  353.07  353.96  353.99  371.62  357.99  373.57  358.24   379.4   357.3
#Mann= 6 ,-1 , 0
       0      .1       0    6.48     .03       0    88.6      .1       0
   167.5   .1326       0   241.5     .08       0  353.96     .16       0
Bank Sta=157.17,246
XS Rating Curve= 0 ,0
Exp/Cntr=0.3,0.1

Type RM Length L Ch R = 1 ,205.9086,33.57,50.12,63.77
XS GIS Cut Line= 6
     317475.8265    4048876.3234     317366.2822    4048916.8402
     317330.0318    4048943.4699     317249.4401    4049002.6728
     317196.9949    4049041.1992     317167.8832    4049086.6428
#Sta/Elev= 30
       0  353.44   45.53  353.15   69.29  352.24   93.44  352.32  122.66  352.79
  142.22   352.8  148.09  352.31  163.66  348.67  167.66  348.19  173.54  347.93
  176.12  347.37  185.31  345.51  195.11   345.1  202.95  344.45  214.72  344.75
  222.56  345.31  238.25  345.65  240.21  345.94   247.4  348.23  250.91  349.11
  257.86   349.5  263.75  350.97  267.69  351.36  287.41  350.71   295.3   351.8
  344.84  353.32  358.83  354.93  362.34  355.66  372.83  358.11  380.82  360.43
#Mann= 5 ,-1 , 0
       0     .03       0   93.44      .1       0  176.12   .1326       0
   247.4     .08       0  362.34     .16       0
Bank Sta=163.66,250.91
XS Rating Curve= 0 ,0
Exp/Cntr=0.3,0.1

Type RM Length L Ch R = 1 ,155.785 ,40.48,49.72,56.84
XS GIS Cut Line= 5
     317476.4879      4048865.74     317361.8644    4048893.6606
     317317.4283    4048909.9165     317223.5152    4048944.2725
     317168.8521    4048986.4221
#Sta/Elev= 30
       0  353.38      22   353.6   45.99  353.21   75.98   352.1  101.71  352.32
  135.72  352.88  149.52  352.49  155.43  351.95  168.29  348.58  171.17  348.16
  179.02  348.03  182.39  347.09  188.82  345.76  210.39  344.72  222.15  344.94
  243.72  346.13  247.64  346.71  250.41  347.78  251.57  348.38  257.45   348.5
  260.44  349.11  263.33   349.8  267.26  351.63  273.18  352.74   279.1  356.46
  288.96   359.1  294.87  359.74  298.82   359.7  308.68  360.43  334.32  363.37
#Mann= 4 ,-1 , 0
       0     .03       0  101.71      .1       0  182.39   .1326       0
  250.41     .16       0
Bank Sta=168.29,260.44
XS Rating Curve= 0 ,0
Exp/Cntr=0.3,0.1

Type RM Length L Ch R = 1 ,106.0629,30.91,49.07,64.91
XS GIS Cut Line= 5
     317482.7969    4048846.1564     317372.6639    4048864.0158
     317303.6526    4048869.1923     317207.4705    4048890.2333
     317177.5658    4048896.7753
#Sta/Elev= 30
       0  353.71   15.94  353.27   55.79  353.18   85.67  352.09  119.78  352.41
  147.16  352.83  157.05   352.7  166.94  351.93  180.23  348.58  184.72  348.03
  188.65  348.21  194.56  347.49  197.23   346.9  204.41  345.94  210.31  345.62
  220.16  344.64  228.04  344.47  241.82  344.87  253.63  345.75  259.54   346.7
  263.11  347.62  265.45  348.23  268.24  349.32  273.33  352.09   275.3  352.75
  279.23  353.26  281.15  354.06  284.97  357.62  300.28  367.14  309.85  370.95
#Mann= 4 ,-1 , 0
       0     .03       0  119.78      .1       0  197.23   .1326       0
  263.11     .16       0
Bank Sta=180.23,268.24
XS Rating Curve= 0 ,0
Exp/Cntr=0.3,0.1

Type RM Length L Ch R = 1 ,56.9968 ,32.8,44.03,55.2
XS GIS Cut Line= 5
     317485.4176    4048824.7295     317368.9895    4048844.9961
     317305.3277    4048837.2169      317206.066    4048825.0877
      317193.435    4048823.5442
#Sta/Elev= 30
       0  353.89   17.73  353.31      65  353.16   88.63  352.08  129.27  352.24
  155.11  352.72  162.88  352.32   172.6  351.42  185.79  348.48  190.16  348.03
     198  348.09  200.72  347.26  203.88  346.54  221.53   344.8  229.37   344.6
  233.29   344.8  237.22  345.49  247.02   344.8  258.78  344.83  262.71  345.46
   271.9  348.22  274.43  349.19  276.43  350.02  278.39  351.37  282.31  354.77
  284.13  355.89  287.77  356.79  289.59  358.48   291.4  361.09  295.04  365.04
#Mann= 4 ,-1 , 0
       0     .03       0  129.27      .1       0  200.72   .1326       0
   271.9     .16       0
Bank Sta=185.79,274.43
XS Rating Curve= 0 ,0
Exp/Cntr=0.3,0.1