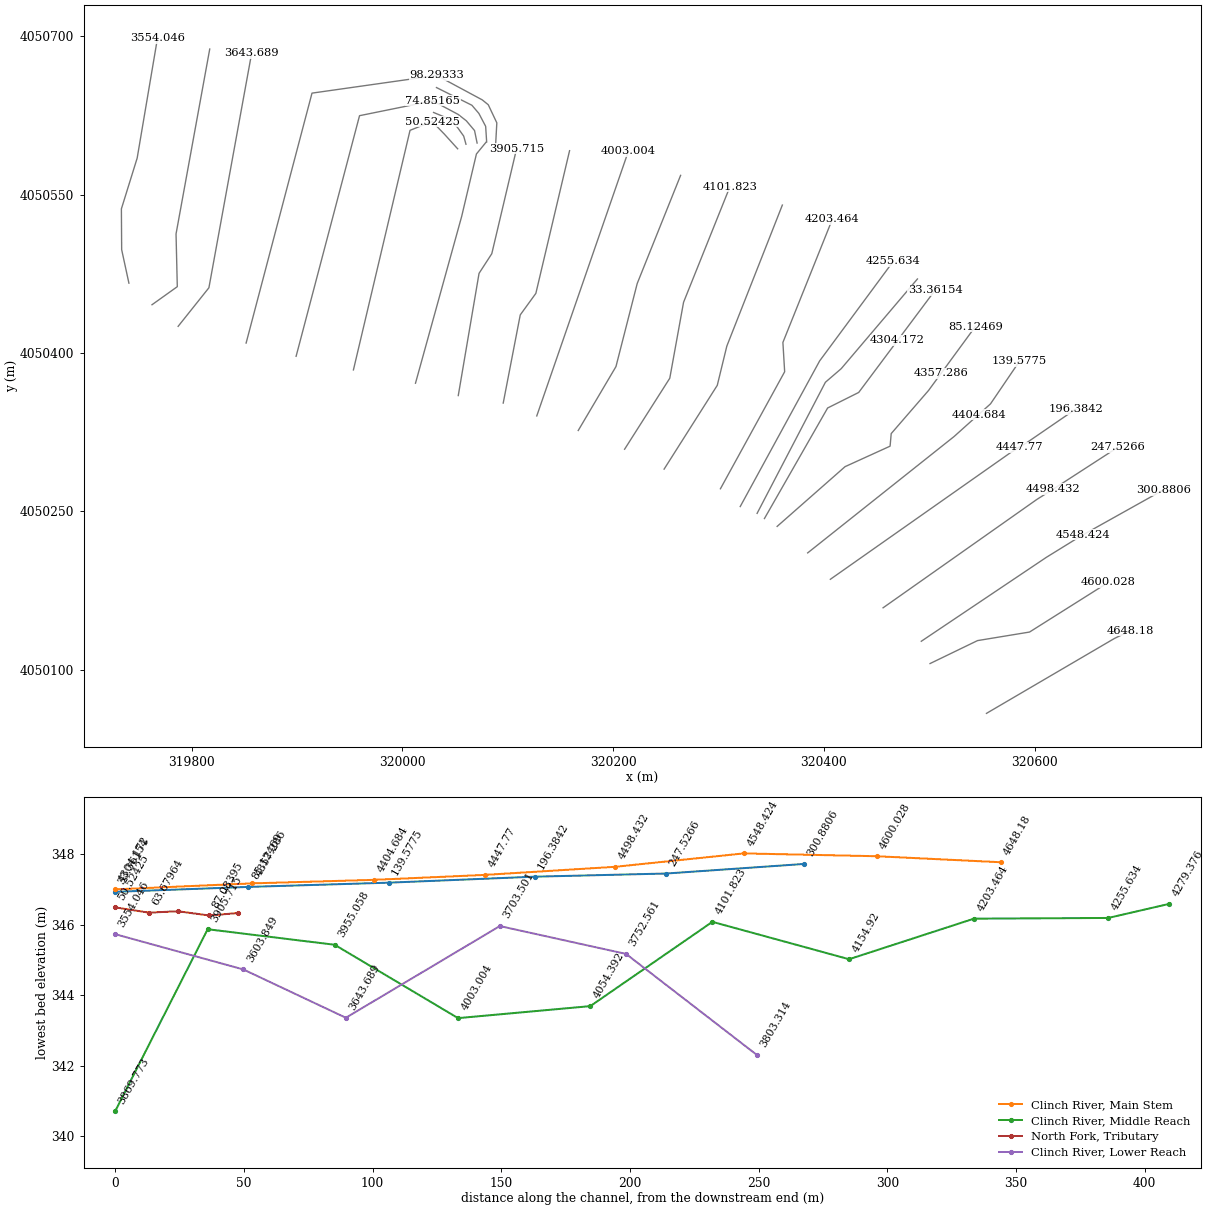
HEC-RAS study WBmod1D.prj: WBmod1D

--- WBmod1D.g06 (geometry) --- (continued)

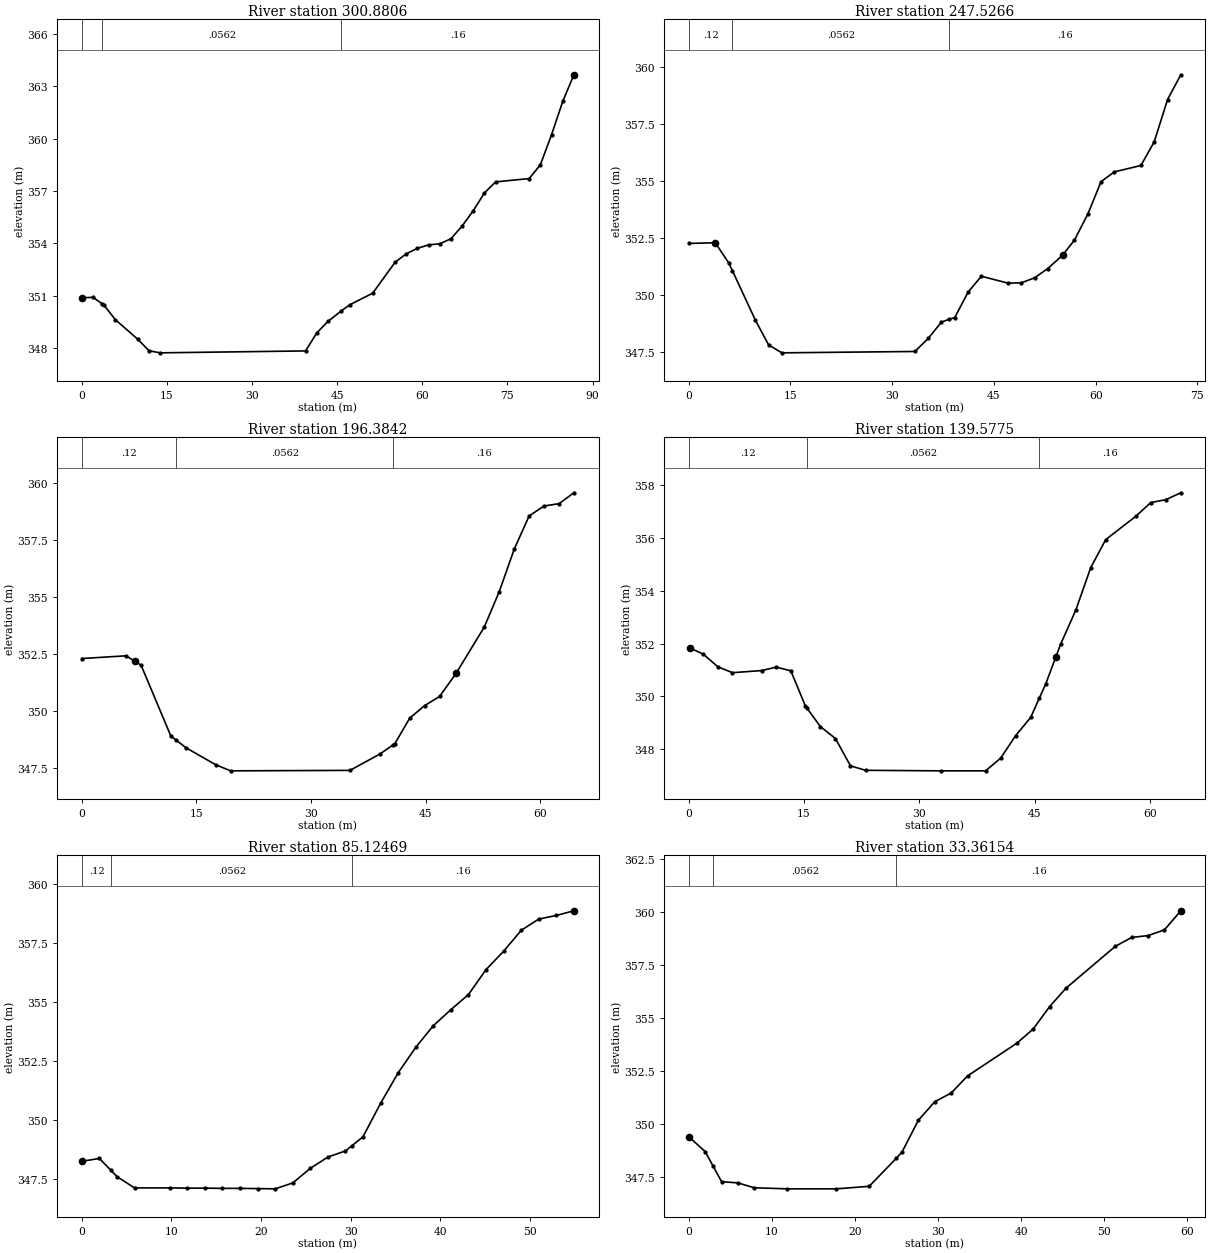
Type RM Length L Ch R = 1 ,300.8806,51.73,53.35,56.02
XS GIS Cut Line= 3
     320646.1206     4050227.881     320690.8836    4050252.8527
     320721.8501    4050270.1278
#Sta/Elev= 29
       0  350.88    1.97   350.9    3.58  350.53    3.94  350.44    5.91  349.62
    9.86   348.5   11.83  347.84    13.8  347.72   39.43  347.83    41.4  348.86
   43.37  349.52    45.7  350.12   47.31  350.49   51.26  351.14    55.2  352.91
   57.17   353.4   59.14  353.71   61.11  353.91   63.08  353.97   65.05  354.26
   67.02  354.99   68.99  355.87   70.96  356.89   72.93  357.52   78.84  357.71
   80.81   358.5   82.78  360.22   84.75  362.13   86.72  363.66
#Mann= 3 ,-1 , 0
       0     .12       0    3.58   .0562       0    45.7     .16       0
Bank Sta=0,86.72
XS Rating Curve= 0 ,0
Exp/Cntr=0.3,0.1

Type RM Length L Ch R = 1 ,247.5266,50.9,51.14,53.63
XS GIS Cut Line= 2
      320617.721    4050271.0724      320678.652    4050310.4615
#Sta/Elev= 27
       0  352.25    3.91  352.28    5.88   351.4    6.43  351.06     9.8   348.9
   11.77   347.8   13.73  347.45   33.34  347.51    35.3  348.08   37.26   348.8
    38.4  348.92   39.22     349   41.18  350.11   43.14  350.81   47.06  350.51
   49.02  350.52   50.98  350.74   52.94  351.15   55.11  351.73   56.87   352.4
   58.83  353.53   60.79  354.96   62.75  355.39   66.67  355.67   68.63  356.71
   70.59  358.56   72.55  359.65
#Mann= 3 ,-1 , 0
       0     .12       0    6.43   .0562       0    38.4     .16       0
Bank Sta=3.91,55.11
XS Rating Curve= 0 ,0
Exp/Cntr=0.3,0.1

Type RM Length L Ch R = 1 ,196.3842,49.6,56.81,67.88
XS GIS Cut Line= 3
     320585.5492    4050310.7311     320592.1555    4050314.7802
     320638.8935    4050346.7788
#Sta/Elev= 24
       0   352.3    5.81  352.42    6.96  352.17    7.75  352.01   11.65  348.89
   12.35  348.71   13.61  348.38   17.51  347.63   19.47  347.36   35.09  347.38
      39   348.1   40.73   348.5   40.95  348.55   42.91  349.68   44.86  350.23
   46.81  350.63   48.98  351.65   52.67  353.69   54.62  355.24   56.58  357.11
   58.53  358.57   60.48  359.01   62.44  359.11   64.39  359.59
#Mann= 3 ,-1 , 0
       0     .12       0   12.35   .0562       0   40.73     .16       0
Bank Sta=6.96,48.98
XS Rating Curve= 0 ,0
Exp/Cntr=0.3,0.1

Type RM Length L Ch R = 1 ,139.5775,52.8,54.45,53.47
XS GIS Cut Line= 3
     320546.7671    4050341.6357     320558.0778    4050351.7635
     320585.5657    4050392.1313
#Sta/Elev= 30
       0  351.85      .1  351.84     1.9   351.6     3.8  351.12    5.69   350.9
    9.49  350.98   11.39  351.11   13.28  350.97   15.18  349.64    15.4  349.55
   17.14  348.86   19.09  348.41   21.04  347.38      23  347.21   32.76  347.19
   38.62  347.19   40.58  347.67   42.53  348.52   44.49  349.21    45.6  349.93
   46.44  350.47   47.74  351.48   48.39  351.98   50.35  353.26    52.3  354.87
   54.25  355.93   58.16  356.81   60.11  357.33   62.07  357.44   64.02   357.7
#Mann= 3 ,-1 , 0
       0     .12       0    15.4   .0562       0    45.6     .16       0
Bank Sta=0.1,47.74
XS Rating Curve= 0 ,0
Exp/Cntr=0.3,0.1

Type RM Length L Ch R = 1 ,85.12469,51.7,51.76,51.42
XS GIS Cut Line= 2
      320511.251    4050380.7478     320543.7404    4050425.0261
#Sta/Elev= 30
       0  348.24    1.96  348.36    3.27  347.85    3.92  347.59    5.88  347.11
    9.81  347.11   11.77   347.1   13.73   347.1   15.69  347.09   17.65  347.09
   19.61  347.08   21.58  347.07   23.54  347.32    25.5  347.94   27.46  348.42
   29.42  348.68   30.18  348.91   31.38  349.28   33.34   350.7   35.31     352
   37.27  353.08   39.23     354   41.19  354.68   43.15  355.32   45.11  356.38
   47.07  357.16   49.04  358.05      51  358.53   52.96  358.68   54.92  358.88
#Mann= 3 ,-1 , 0
       0     .12       0    3.27   .0562       0   30.18     .16       0
Bank Sta=0,54.92
XS Rating Curve= 0 ,0
Exp/Cntr=0.3,0.1

Type RM Length L Ch R = 1 ,33.36154,26.26,33.36,18.47
XS GIS Cut Line= 2
     320469.9539    4050411.9048     320505.4319    4050459.3002
#Sta/Elev= 24
       0  349.39    1.97  348.69    2.95  347.99    3.95  347.27    5.92  347.21
    7.89  346.98   11.84  346.93   17.76  346.93   21.71  347.05   24.99  348.38
   25.65  348.66   27.63  350.17    29.6  351.04   31.57  351.45   33.55  352.26
   39.47   353.8   41.44  354.47   43.42  355.53   45.39   356.4   51.31  358.37
   53.28  358.79   55.26  358.88   57.23  359.15    59.2  360.05
#Mann= 3 ,-1 , 0
       0     .12       0    2.95   .0562       0   24.99     .16       0
Bank Sta=0,59.2
XS Rating Curve= 0 ,0
Exp/Cntr=0.3,0.1

River Reach=Clinch River    ,Main Stem

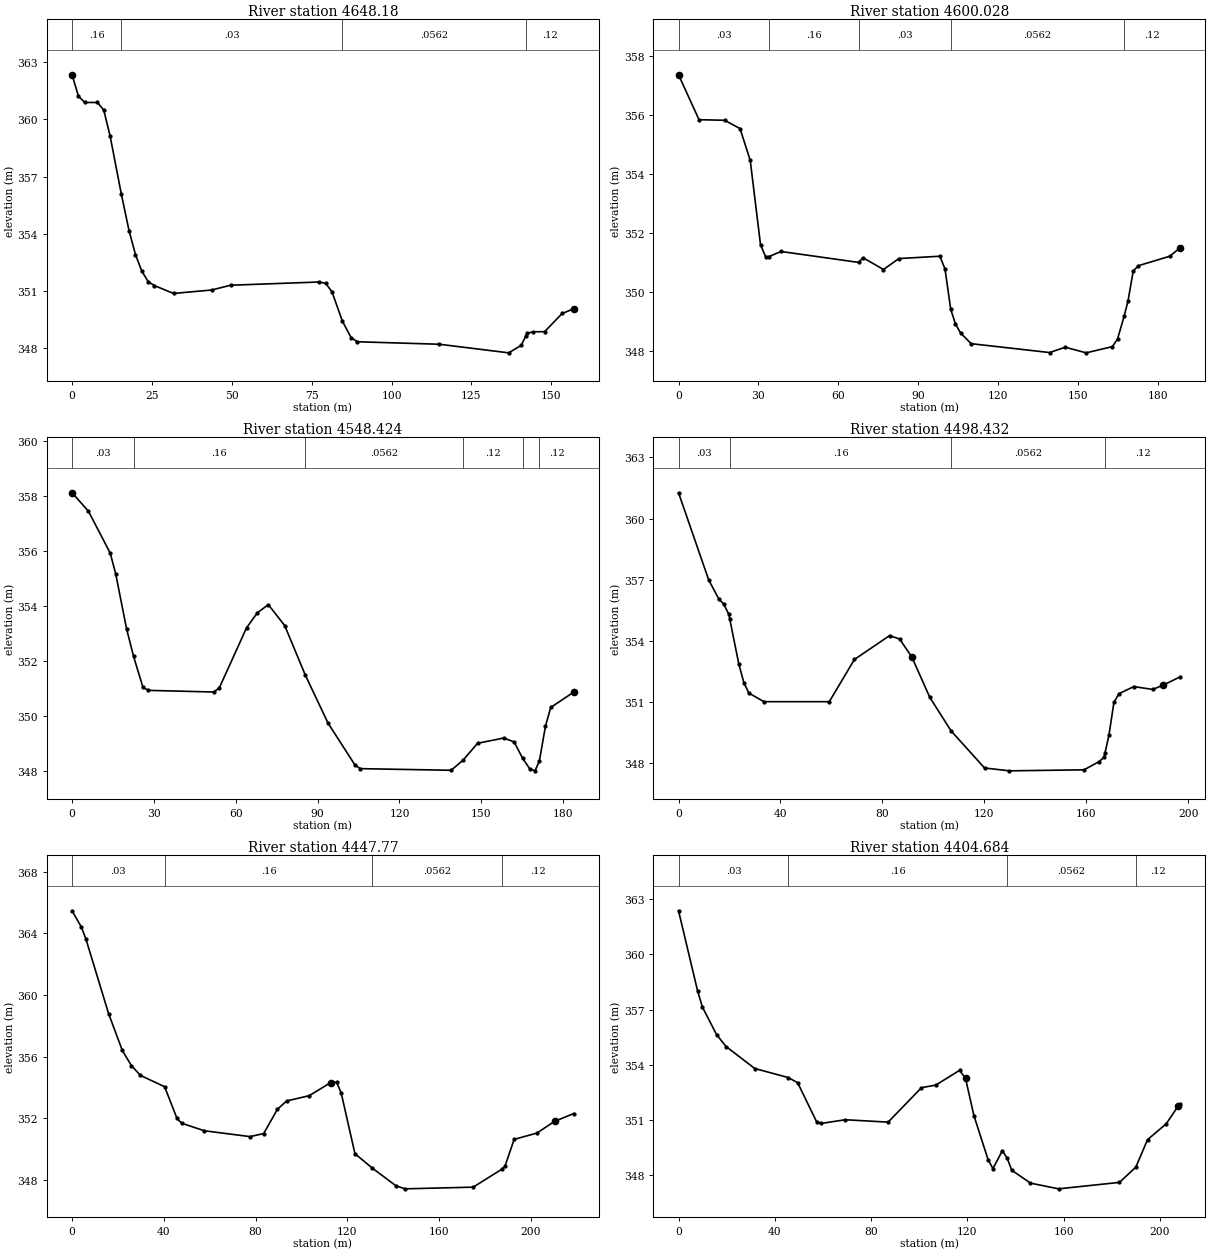
Type RM Length L Ch R = 1 ,4648.18 ,60,48.15,50.34
XS GIS Cut Line= 4
     320554.2473    4050058.6163      320629.645     4050102.679
      320675.632    4050129.5539     320690.4575    4050136.7511
#Sta/Elev= 30
       0  362.33    1.98  361.21    3.97  360.88    7.94  360.88    9.92  360.48
   11.91  359.12   15.42  356.08   17.86  354.15   19.85  352.91   21.83  352.05
   23.82   351.5    25.8  351.29   31.76  350.88   43.66  351.06   49.62  351.31
   77.41  351.48   79.39  351.41   81.37  350.96   84.59  349.44   87.33  348.57
    89.3  348.35  114.95  348.22  136.65  347.77  140.59  348.16  141.97  348.63
  142.42  348.79  144.26  348.87  147.92  348.88  153.41  349.83  157.07  350.08
#Mann= 4 ,-1 , 0
       0     .16       0   15.42     .03       0   84.59   .0562       0
  141.97     .12       0
Bank Sta=0,157.07
XS Rating Curve= 0 ,0
Exp/Cntr=0.3,0.1

Type RM Length L Ch R = 1 ,4600.028,35.94,51.6,51
XS GIS Cut Line= 4
     320500.7236    4050105.8024     320545.7491    4050127.5448
     320595.1043     4050135.642     320669.8785    4050182.6929
#Sta/Elev= 30
       0  357.35    7.69  355.83   17.31  355.81   23.08  355.53   26.92  354.45
   30.77   351.6   32.69  351.19   34.01   351.2   38.46  351.37    67.6     351
   69.24  351.16   76.93  350.76    82.7  351.13   98.09  351.21  100.02  350.78
  102.18  349.41  103.94  348.92   105.9  348.61  109.83  348.25  139.28  347.95
  145.17  348.13  153.02  347.94  162.84  348.15   164.8  348.41  167.27  349.18
  168.73   349.7  170.69  350.71  172.65  350.89  184.43  351.21  188.36   351.5
#Mann= 5 ,-1 , 0
       0     .03       0   34.01     .16       0    67.6     .03       0
  102.18   .0562       0  167.27     .12       0
Bank Sta=0,188.36
XS Rating Curve= 0 ,0
Exp/Cntr=0.3,0.1

Type RM Length L Ch R = 1 ,4548.424,48.23,49.99,51.73
XS GIS Cut Line= 5
     320492.4164    4050126.9221     320565.4709    4050175.8588
     320611.1192     4050206.437     320643.7081    4050226.5351
     320646.1108    4050227.8755
#Sta/Elev= 30
       0  358.11       6  357.44   13.99  355.92   15.99  355.17   19.98  353.17
   22.55  352.17   25.98  351.05   27.98  350.94   51.96  350.88   53.96  351.03
   63.95  353.21   67.95  353.76   71.94  354.05   77.94  353.29   85.46   351.5
   93.82  349.75  103.63  348.24  105.59   348.1  138.95  348.04  143.33  348.41
  148.62  349.02  158.19  349.21  162.02  349.07  165.11  348.48  167.76  348.09
  169.68  348.02   171.3  348.39   173.5  349.64  175.42  350.32  183.91  350.88
#Mann= 6 ,-1 , 0
       0     .03       0   22.55     .16       0   85.46   .0562       0
  143.33     .12       0  165.11   .0562       0   171.3     .12       0
Bank Sta=0,183.91
XS Rating Curve= 0 ,0
Exp/Cntr=0.3,0.1

Type RM Length L Ch R = 1 ,4498.432,50.94,50.66,50.9
XS GIS Cut Line= 5
     320456.1551    4050158.6168       320536.79    4050215.3347
     320602.2454    4050261.3754     320616.4107    4050270.2253
     320617.7136    4050271.0676
#Sta/Elev= 30
       0  361.27   11.83     357   15.77  356.07   17.75  355.81   19.72  355.31
   20.13  355.06   23.66  352.87   25.63  351.96    27.6  351.45   33.52  351.03
   59.15  351.03   69.01   353.1   82.81  354.27   86.75   354.1   91.52  353.22
   98.58  351.24  106.91   349.6  120.05  347.78  129.81  347.64  159.09  347.69
  164.95  348.09   166.9   348.3  167.32  348.53  168.85  349.38   170.8  350.99
  172.75  351.42  178.61  351.77  186.03  351.63  190.24  351.85  196.86  352.25
#Mann= 4 ,-1 , 0
       0     .03       0   20.13     .16       0  106.91   .0562       0
  167.32     .12       0
Bank Sta=91.52,190.24
XS Rating Curve= 0 ,0
Exp/Cntr=0.3,0.1

Type RM Length L Ch R = 1 ,4447.77 ,39.28,43.09,49.6
XS GIS Cut Line= 4
     320406.1333    4050185.6172     320510.3316    4050258.7264
     320576.8649    4050305.4085     320585.5429    4050310.7273
#Sta/Elev= 30
       0  365.46    3.98  364.42    5.97  363.66   15.91  358.79   21.88   356.4
   25.86  355.41   29.83  354.77   40.34  354.04   45.74  351.98   47.73  351.67
   57.68  351.18   77.57   350.8   83.53     351    89.5  352.57   93.48  353.11
  103.42  353.46  112.75  354.31  115.35  354.33  117.34  353.62  123.31  349.69
  130.94  348.75  141.16  347.61  145.13  347.41  174.86  347.52  187.63  348.71
  188.74  348.89  192.71  350.62  202.62  351.03  210.31  351.79  218.74   352.3
#Mann= 4 ,-1 , 0
       0     .03       0   40.34     .16       0  130.94   .0562       0
  187.63     .12       0
Bank Sta=112.75,210.31
XS Rating Curve= 0 ,0
Exp/Cntr=0.3,0.1

Type RM Length L Ch R = 1 ,4404.684,35.13,47.4,52.8
XS GIS Cut Line= 4
     320384.6058    4050210.6092     320488.5035     4050293.043
      320523.576      4050320.87     320546.7602    4050341.6296
#Sta/Elev= 30
       0  362.36    7.92  358.01     9.9  357.14   15.84  355.63    19.8  354.99
   31.67   353.8   45.58  353.31   49.49  353.03   57.41   350.9   59.39  350.82
   69.28  351.02    87.1  350.89  100.96  352.76  106.89   352.9  116.79   353.7
  119.27  353.26  122.73  351.25  128.67  348.84  130.65  348.37  134.57  349.34
  136.57  348.93  138.47  348.28  146.25  347.58  157.93  347.27  183.23  347.62
  190.04  348.45   194.9  349.94  202.68   350.8  207.65  351.77  208.52  351.85
#Mann= 4 ,-1 , 0
       0     .03       0   45.58     .16       0  136.57   .0562       0
  190.04     .12       0
Bank Sta=119.27,207.65
XS Rating Curve= 0 ,0
Exp/Cntr=0.3,0.1

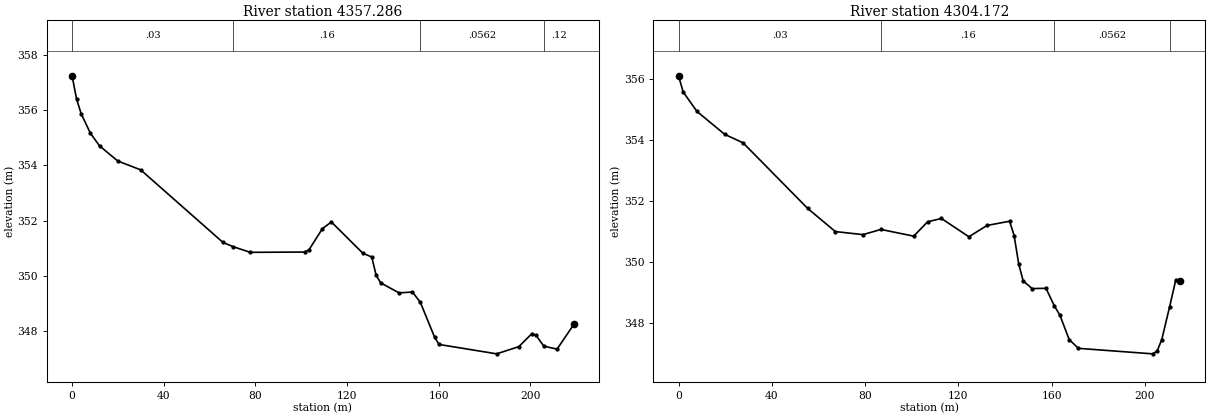
Type RM Length L Ch R = 1 ,4357.286,59.28,53.11,51.7
XS GIS Cut Line= 6
     320355.6307    4050235.7011     320420.0751    4050292.2872
     320462.8057    4050311.7008      320463.864     4050323.607
     320499.3183    4050364.4852      320511.251    4050380.7478
#Sta/Elev= 30
       0  357.25    1.99   356.4    3.99  355.87    7.98  355.17   11.97  354.71
   19.94  354.16   29.92  353.84   65.82  351.21   70.41  351.05   77.78  350.85
  101.41  350.86  103.36  350.94  109.23  351.71  113.14  351.95  126.83  350.82
  130.74  350.68   132.7  350.01  134.69  349.74  142.66  349.38  148.51  349.41
  151.94  349.04  158.18  347.77  160.11  347.51  185.23  347.17   194.9  347.43
  200.59   347.9  202.43  347.84  205.81  347.45   211.6  347.34  218.93  348.24
#Mann= 4 ,-1 , 0
       0     .03       0   70.41     .16       0  151.94   .0562       0
  205.81     .12       0
Bank Sta=0,218.93
XS Rating Curve= 0 ,0
Exp/Cntr=0.3,0.1

Type RM Length L Ch R = 1 ,4304.172,19.2,24.8,26.26
XS GIS Cut Line= 4
     320343.5792    4050243.1492     320403.5441    4050347.8591
     320433.0418    4050362.5935     320469.9492    4050411.8985
#Sta/Elev= 30
       0  356.12    1.98  355.59    7.91  354.95   19.78   354.2   27.69  353.92
   55.39  351.77   67.26  351.01   79.12  350.91   86.81  351.08  100.88  350.86
  106.82  351.33  112.75  351.44  124.54  350.84   132.3  351.21     142  351.35
  143.94  350.88  145.88  349.96  147.82  349.39   151.7  349.14  157.61  349.15
  161.21  348.57  163.57  348.27  167.54  347.47  171.52  347.18  203.31     347
  205.29  347.09  207.28  347.47  210.59  348.53  213.24  349.41  215.23  349.39
#Mann= 4 ,-1 , 0
       0     .03       0   86.81     .16       0  161.21   .0562       0
  210.59     .12       0
Bank Sta=0,215.23
XS Rating Curve= 0 ,0
Exp/Cntr=0.3,0.1

River Reach=Clinch River    ,Middle Reach

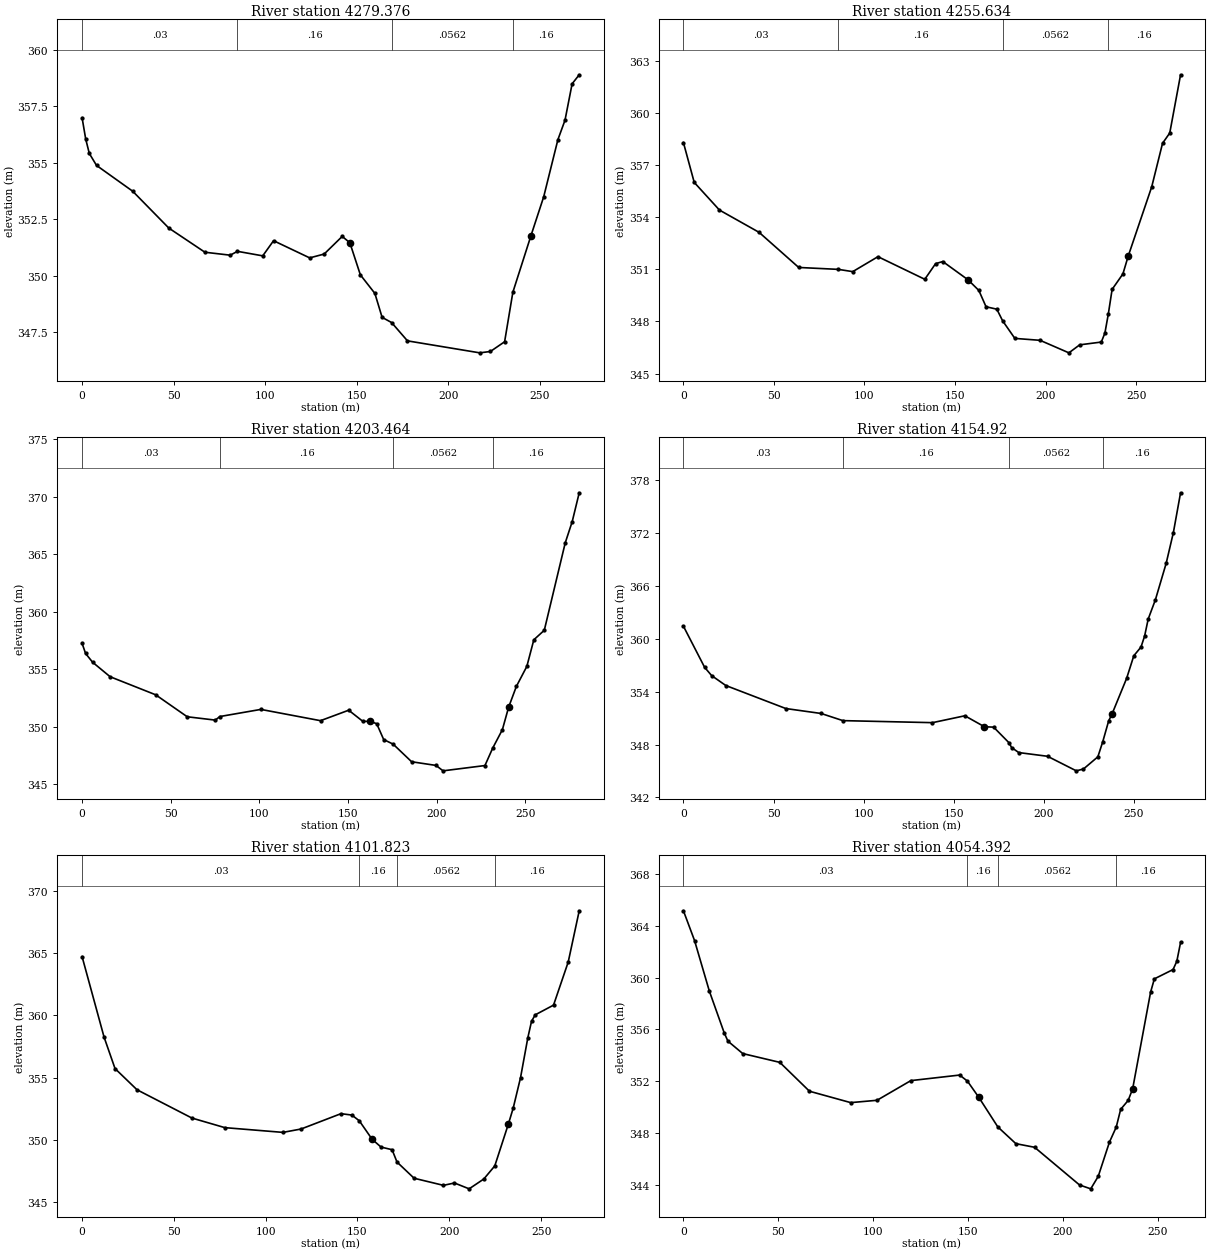
Type RM Length L Ch R = 1 ,4279.376,15.66,23.74,27.2
XS GIS Cut Line= 5
     320336.6232    4050248.0636     320401.4124    4050372.2086
     320416.4359    4050385.1111     320449.7769    4050424.2814
     320488.7458    4050470.0636
#Sta/Elev= 30
       0  356.99    1.97  356.05    3.94  355.41    7.89  354.88   27.61  353.74
   47.34  352.11   67.06  351.04   80.86  350.91   84.83  351.08   98.62  350.88
  104.53  351.55  124.26  350.79  132.15  350.96  142.01  351.74  146.19  351.46
  151.92  350.04  159.84  349.22  163.79  348.16  168.97  347.93  177.64  347.12
  217.09  346.59  222.91  346.65  230.67  347.08  235.17  349.27     245  351.76
     252  353.49  259.76  356.02  263.64  356.88  267.52  358.49   271.4  358.89
#Mann= 4 ,-1 , 0
       0     .03       0   84.83     .16       0  168.97   .0562       0
  235.17     .16       0
Bank Sta=146.19,245
XS Rating Curve= 0 ,0
Exp/Cntr=0.3,0.1

Type RM Length L Ch R = 1 ,4255.634,32.76,52.17,63.74
XS GIS Cut Line= 3
     320320.6015    4050254.5014     320395.9612    4050392.4355
     320465.8256    4050486.7638
#Sta/Elev= 30
       0  358.28    5.97  355.99    19.9   354.4   41.78  353.12   63.67   351.1
   85.52  350.99   93.51  350.86  107.44  351.72   133.3  350.42  139.27  351.32
  143.25  351.44  157.18  350.39  163.15  349.78  167.13  348.84  173.09   348.7
   176.3  348.03  183.04  347.02  196.97  346.91  212.89  346.19  218.85  346.65
  230.79  346.81  232.78  347.33  234.66  348.42  236.76  349.84  242.73  350.73
  245.61  351.74  258.64  355.74  264.61  358.24  268.59  358.83  274.56  362.18
#Mann= 4 ,-1 , 0
       0     .03       0   85.52     .16       0   176.3   .0562       0
  234.66     .16       0
Bank Sta=157.18,245.61
XS Rating Curve= 0 ,0
Exp/Cntr=0.3,0.1

Type RM Length L Ch R = 1 ,4203.464,53.89,48.54,48.84
XS GIS Cut Line= 4
     320301.8165    4050271.3392     320362.7586    4050382.1803
     320361.0967    4050409.9472     320408.0969    4050526.8685
#Sta/Elev= 30
       0  357.25    1.98  356.37    5.93  355.61   15.81  354.35    41.5  352.78
   59.29  350.87    75.1  350.58   77.68  350.89   100.8  351.51  134.44  350.53
  150.33  351.44  158.24  350.48  162.53  350.46  166.12  350.27  170.06  348.89
   175.4  348.49  185.81  346.96  199.59  346.64  203.53  346.17  227.16  346.63
  231.52  348.14     237  349.75  240.49  351.69  244.88  353.51  250.79  355.25
  254.72  357.56  260.63  358.39  272.44  365.99  276.38  367.84  280.32  370.34
#Mann= 4 ,-1 , 0
       0     .03       0   77.68     .16       0   175.4   .0562       0
  231.52     .16       0
Bank Sta=162.53,240.49
XS Rating Curve= 0 ,0
Exp/Cntr=0.3,0.1

Type RM Length L Ch R = 1 ,4154.92 ,50.74,53.1,52.8
XS GIS Cut Line= 4
     320248.3828    4050289.9528     320298.8335    4050369.3239
     320307.8783    4050406.4264     320360.5787     4050540.048
#Sta/Elev= 30
       0  361.41   11.76  356.75   15.67  355.81   23.51  354.69   56.82  352.08
   76.41  351.52   88.49  350.71  138.22  350.48  156.18  351.26  167.01  350.02
  172.14  349.97  180.68   348.2  182.11  347.66   186.1  347.09  202.06  346.67
  218.02  345.02  222.01  345.23  229.99  346.61  232.72  348.33  235.98  350.68
  237.93   351.5  245.95   355.5  249.94  358.06  253.93  359.05  255.93  360.29
  257.92  362.22  261.91   364.4   267.9  368.54  271.89  372.02  275.88  376.53
#Mann= 4 ,-1 , 0
       0     .03       0   88.49     .16       0  180.68   .0562       0
  232.72     .16       0
Bank Sta=167.01,237.93
XS Rating Curve= 0 ,0
Exp/Cntr=0.3,0.1

Type RM Length L Ch R = 1 ,4101.823,48.48,47.43,47.43
XS GIS Cut Line= 4
     320210.8897    4050308.7956     320253.7623     4050376.048
      320266.836    4050447.9719      320310.819    4050557.3871
#Sta/Elev= 30
       0  364.71   11.96  358.26   17.94  355.73   29.91  354.03   59.82  351.76
   77.76  350.99  109.39  350.61  119.27  350.88     141  352.11  146.93     352
  150.99  351.54  158.01  350.05  162.85  349.43  168.85  349.22  171.53  348.23
  180.84  346.93  196.83  346.36  202.83  346.55  210.82  346.08  218.82  346.87
  224.79  347.92  232.26  351.31  234.81  352.55   238.8  354.99   242.8  358.21
   244.8  359.52   246.8  360.04  256.79  360.82  264.79  364.28  270.78  368.39
#Mann= 4 ,-1 , 0
       0     .03       0  150.99     .16       0  171.53   .0562       0
  224.79     .16       0
Bank Sta=158.01,232.26
XS Rating Curve= 0 ,0
Exp/Cntr=0.3,0.1

Type RM Length L Ch R = 1 ,4054.392,50.43,51.39,53.8
XS GIS Cut Line= 4
     320166.8993    4050326.5308     320202.6957    4050387.0594
     320222.8456    4050465.7071     320264.0367    4050568.1773
#Sta/Elev= 30
       0  365.17    5.86  362.87   13.67  358.96   21.49  355.74   23.44   355.1
   31.25  354.14   50.79  353.46   66.41  351.23   88.14  350.35     102  350.53
  119.83  352.05  145.57  352.48  149.65  352.01  155.59  350.77  165.68  348.47
  175.17  347.18  185.04   346.9   208.7  343.99  214.62  343.69  218.56  344.65
  224.48   347.3  228.06  348.46  230.39  349.83  234.34  350.52   236.7  351.41
  246.17  358.89  248.14  359.91     258  360.63  259.98  361.27  261.95  362.72
#Mann= 4 ,-1 , 0
       0     .03       0  149.65     .16       0  165.68   .0562       0
  228.06     .16       0
Bank Sta=155.59,236.7
XS Rating Curve= 0 ,0
Exp/Cntr=0.3,0.1

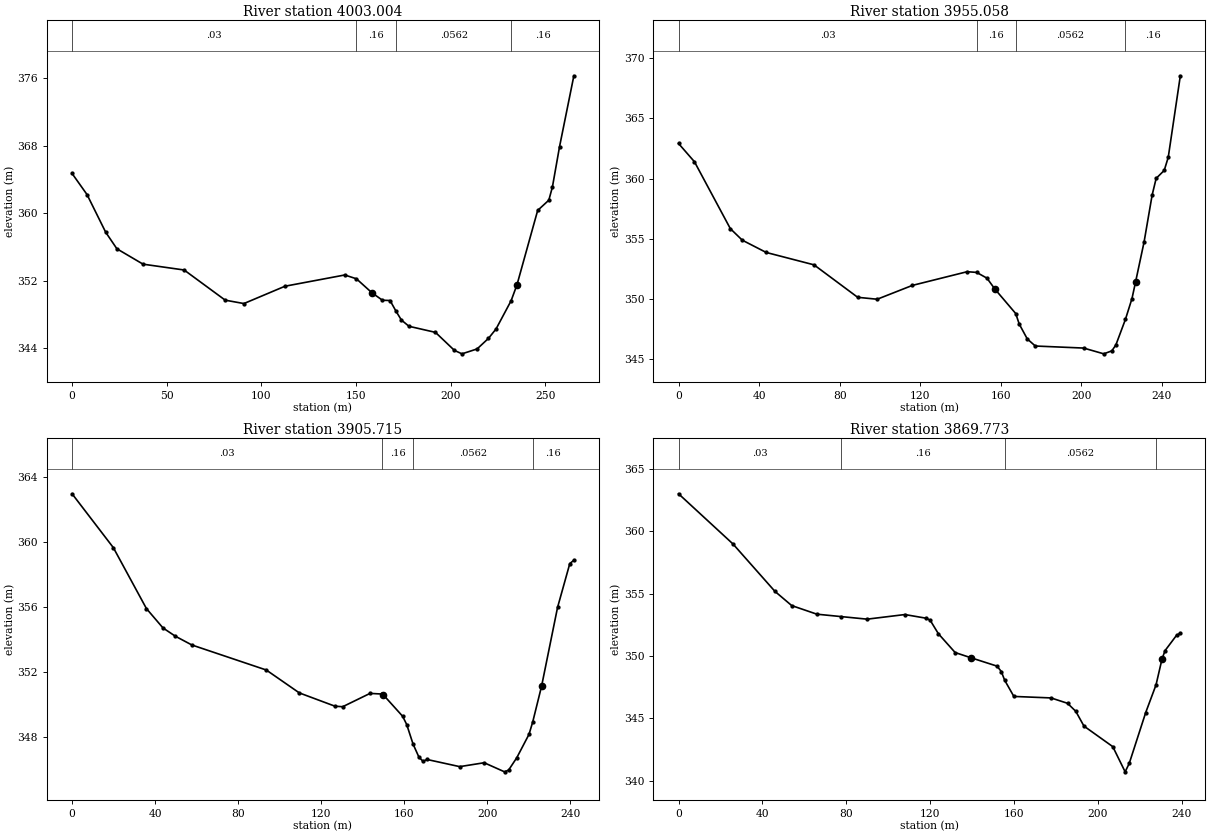
Type RM Length L Ch R = 1 ,4003.004,42.97,47.95,52
XS GIS Cut Line= 4
     320127.5561     4050340.332     320176.6961    4050482.0545
     320209.4561    4050576.5361     320214.4091    4050590.8209
#Sta/Elev= 30
       0  364.69    7.89   362.2   17.76  357.74   23.68  355.78    37.5  353.96
   59.21  353.27   80.92   349.7   90.79   349.3   112.5  351.35  144.08  352.68
  150.24  352.23  158.41  350.58     164  349.69     168  349.66  171.24  348.36
     174  347.35     178  346.61     192  345.89     202  343.76     206  343.35
     214  343.93     220  345.18     224  346.29  231.98  349.64  235.08  351.53
     246  360.32  251.89  361.53  253.78  363.08  257.56  367.87  265.12  376.25
#Mann= 4 ,-1 , 0
       0     .03       0  150.24     .16       0  171.24   .0562       0
  231.98     .16       0
Bank Sta=158.41,235.08
XS Rating Curve= 0 ,0
Exp/Cntr=0.3,0.1

Type RM Length L Ch R = 1 ,3955.058,50.75,49.34,49.49
XS GIS Cut Line= 5
     320095.7166    4050352.4919     320111.8844    4050436.0227
      320126.686    4050456.3993     320135.6451    4050494.2464
     320158.6805     4050591.557
#Sta/Elev= 30
       0  362.92    7.91   361.4   25.72  355.84   31.66  354.88   43.53  353.86
   67.27  352.83   88.96  350.13   98.64  349.97   116.1  351.12  143.33  352.26
  148.04   352.2  153.16  351.72  157.06  350.82  167.43  348.78  169.16  347.91
  173.16  346.67  177.16  346.08  201.16  345.91  211.16  345.43  215.16  345.68
  217.16  346.17  221.89  348.29  225.16  350.03  226.94  351.41  231.16  354.73
  235.16  358.63  237.16  360.02  241.16  360.68  243.16  361.77  249.16  368.55
#Mann= 4 ,-1 , 0
       0     .03       0  148.04     .16       0  167.43   .0562       0
  221.89     .16       0
Bank Sta=157.06,226.94
XS Rating Curve= 0 ,0
Exp/Cntr=0.3,0.1

Type RM Length L Ch R = 1 ,3905.715,37.46,35.94,32.79
XS GIS Cut Line= 4
     320053.0693    4050359.6191     320072.7926    4050475.3878
     320084.8748    4050493.9783     320108.3964     4050593.343
#Sta/Elev= 30
       0  362.99    19.9  359.67   35.83  355.92   43.79  354.73   49.76  354.22
   57.72  353.68   93.55  352.14  109.47  350.73  126.67  349.91  130.37  349.88
  143.54   350.7   149.3  350.66   149.8  350.63  159.25  349.29  161.21  348.78
  164.26  347.58   167.1  346.77  169.06  346.52  171.03  346.63  186.74  346.19
  198.52  346.43  208.34  345.87   210.3  345.98  214.23  346.74  220.12  348.18
   221.9  348.94  226.18  351.15  233.86  355.99  239.76  358.69  241.72   358.9
#Mann= 4 ,-1 , 0
       0     .03       0   149.3     .16       0  164.26   .0562       0
   221.9     .16       0
Bank Sta=149.8,226.18
XS Rating Curve= 0 ,0
Exp/Cntr=0.3,0.1

Type RM Length L Ch R = 1 ,3869.773,65,66.46,14.16
XS GIS Cut Line= 4
      320012.478    4050371.3182     320056.2836    4050529.2275
     320070.2988    4050588.4335     320079.5228    4050599.6658
#Sta/Elev= 30
       0  363.02   25.98  358.99   45.96  355.19   53.96  354.05   65.95  353.36
   77.29  353.17   89.93  352.96  107.92  353.33  117.91  353.04  119.91  352.89
   123.9  351.79   131.9  350.28  139.48  349.86  151.88  349.19  153.88  348.76
   155.5  348.06  159.88  346.76  177.61  346.64  185.46  346.21  189.39  345.57
  193.31  344.38  207.05  342.73  212.94  340.71   214.9  341.39  222.75  345.47
  227.67  347.69   230.5  349.75  231.98  350.44  237.43  351.66  239.25  351.83
#Mann= 4 ,-1 , 0
       0     .03       0   77.29     .16       0   155.5   .0562       0
  227.67     .16       0
Bank Sta=139.48,230.5
XS Rating Curve= 0 ,0
Exp/Cntr=0.3,0.1

River Reach=North Fork      ,Tributary

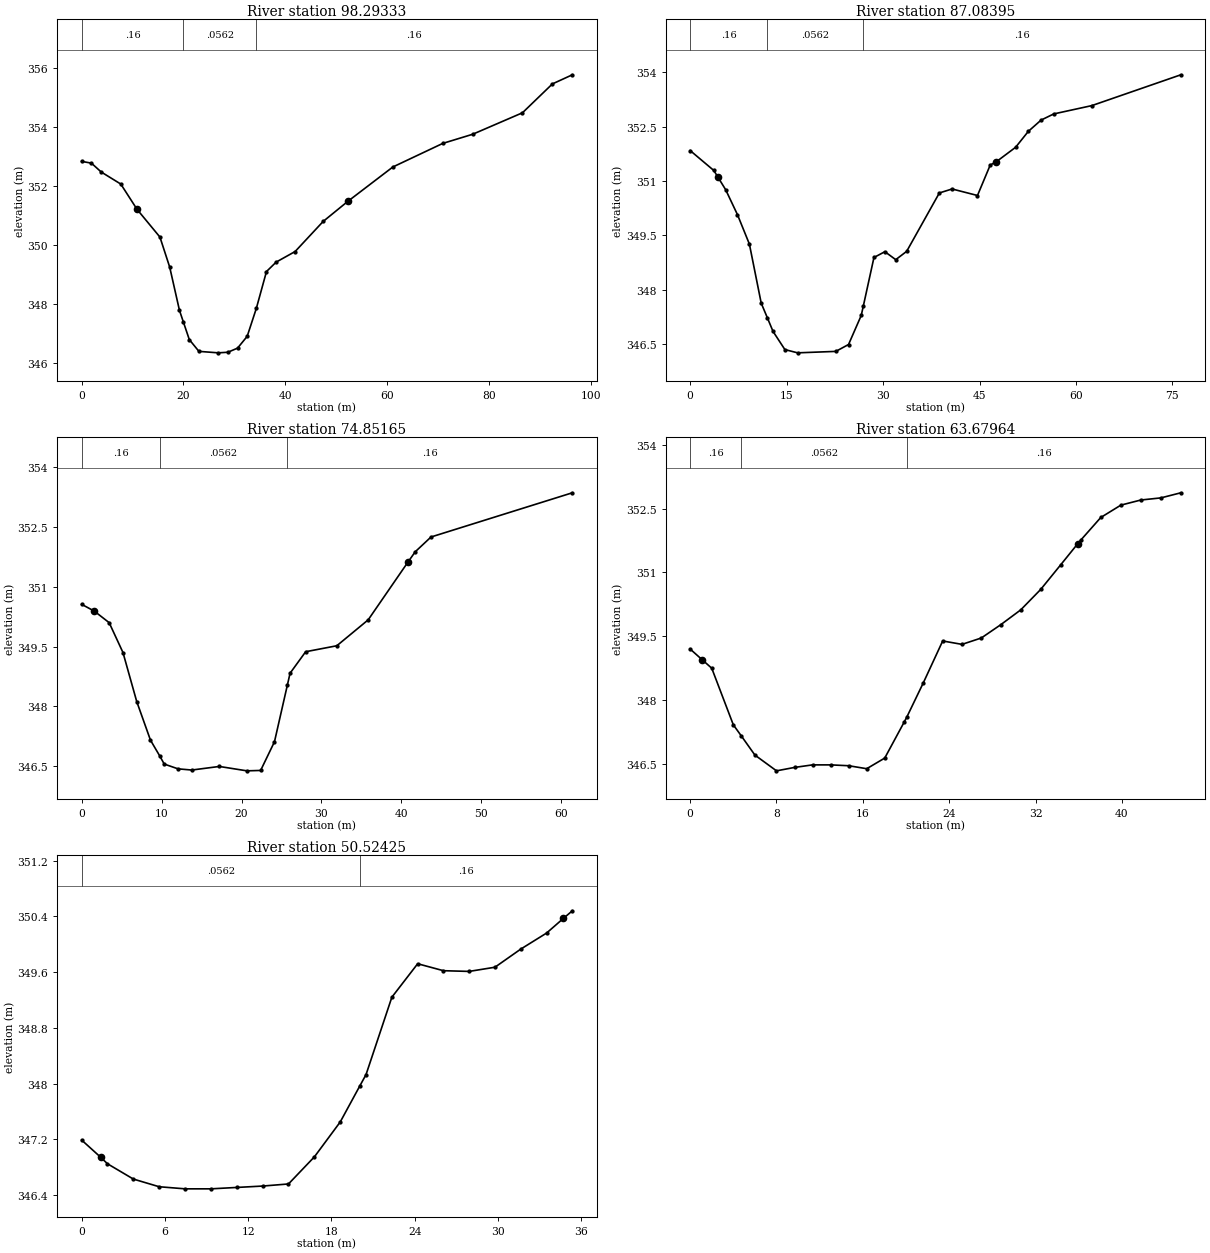
Type RM Length L Ch R = 1 ,98.29333,10.02,11.21,14.23
XS GIS Cut Line= 5
     320088.4987    4050596.8002     320089.6548    4050617.9138
     320081.5393    4050635.0498     320075.8435    4050639.6626
     320032.7105    4050662.8283
#Sta/Elev= 27
       0  352.83    1.92  352.77    3.84  352.47    7.69  352.06   10.89   351.2
   15.38  350.26    17.3  349.24   19.22  347.77   19.96  347.39   21.15  346.78
   23.04  346.38   26.83  346.33   28.73  346.35   30.63  346.49   32.52  346.89
   34.32  347.84   36.31  349.09   38.21  349.41   41.94  349.77   47.44  350.79
   52.27  351.47   61.14  352.64   70.94  353.44   76.81  353.75    86.6  354.48
   92.48  355.46    96.4  355.77
#Mann= 3 ,-1 , 0
       0     .16       0   19.96   .0562       0   34.32     .16       0
Bank Sta=10.89,52.27
XS Rating Curve= 0 ,0
Exp/Cntr=0.3,0.1

Type RM Length L Ch R = 1 ,87.08395,9.71,12.23,14.68
XS GIS Cut Line= 5
     320080.0055    4050599.8958     320079.0598    4050614.5937
     320072.6152    4050626.8593      320066.001    4050634.5826
     320032.3946     4050651.348
#Sta/Elev= 30
       0  351.84    3.68  351.29    4.27  351.12    5.52  350.76    7.36  350.07
    9.21  349.26   11.05  347.63   12.02  347.22   12.89  346.85   14.73  346.35
   16.71  346.26   22.65   346.3   24.63  346.49    26.6  347.29   26.94  347.56
   28.58  348.89   30.28  349.05   31.97  348.83   33.67  349.06   38.75  350.67
   40.73  350.78   44.68   350.6   46.66  351.44    47.6  351.53   50.61  351.93
   52.59  352.37   54.57  352.68   56.54  352.85   62.47  353.08   76.31  353.93
#Mann= 3 ,-1 , 0
       0     .16       0   12.02   .0562       0   26.94     .16       0
Bank Sta=4.27,47.6
XS Rating Curve= 0 ,0
Exp/Cntr=0.3,0.1

Type RM Length L Ch R = 1 ,74.85165,10.7,11.17,9.52
XS GIS Cut Line= 5
     320070.9412    4050598.7874     320068.5241    4050610.5976
     320060.7536    4050619.8212     320053.0692    4050625.8412
     320028.7965    4050638.7647
#Sta/Elev= 23
       0  350.56    1.58  350.39    3.44   350.1    5.17  349.35    6.89  348.12
    8.61  347.15    9.78  346.75   10.33  346.55   12.06  346.43   13.78   346.4
   17.22  346.49   20.67  346.38   22.39  346.39   24.12  347.11   25.73  348.53
   26.07  348.83   28.02  349.37   31.92  349.52   35.84  350.17   40.85  351.63
   41.73  351.88    43.7  352.25   61.38  353.36
#Mann= 3 ,-1 , 0
       0     .16       0    9.78   .0562       0   25.73     .16       0
Bank Sta=1.58,40.85
XS Rating Curve= 0 ,0
Exp/Cntr=0.3,0.1

Type RM Length L Ch R = 1 ,63.67964,9.19,13.16,9.67
XS GIS Cut Line= 5
     320060.3787    4050597.6496     320058.2182    4050605.3508
       320052.38      4050613.51      320045.073    4050621.3843
     320029.6308    4050627.7458
#Sta/Elev= 30
       0   349.2    1.11  348.95       2  348.75       4  347.42    4.74  347.16
       6  346.71       8  346.34    9.67  346.42   11.34  346.48   13.01  346.48
   14.69  346.46   16.36  346.39   18.03  346.64   19.82  347.48   20.07   347.6
   21.61  348.41    23.4  349.39   25.19  349.31   26.98  349.46   28.77  349.77
   30.63  350.12   32.48   350.6   34.34  351.18    35.9  351.67    36.2  351.76
   38.05  352.29   39.91  352.58   41.76   352.7   43.62  352.75   45.47  352.87
#Mann= 3 ,-1 , 0
       0     .16       0    4.74   .0562       0   20.07     .16       0
Bank Sta=1.11,35.9
XS Rating Curve= 0 ,0
Exp/Cntr=0.3,0.1

Type RM Length L Ch R = 1 ,50.52425,0.47,50.52,0.27
XS GIS Cut Line= 3
     320052.4888    4050593.3402      320039.956    4050607.1391
     320028.3079    4050619.1469
#Sta/Elev= 23
       0  347.19    1.39  346.94    1.86  346.85    3.73  346.63    5.59  346.52
    7.46  346.49    9.32  346.49   11.18  346.51   13.05  346.53   14.91  346.56
   16.78  346.95   18.64  347.45   20.06  347.97    20.5  348.13   22.36  349.24
   24.22  349.72   26.08  349.62   27.93  349.61   29.79  349.67   31.65  349.93
   33.51  350.16   34.72  350.37   35.37  350.48
#Mann= 2 ,-1 , 0
       0   .0562       0   20.06     .16       0
Bank Sta=1.39,34.72
XS Rating Curve= 0 ,0
Exp/Cntr=0.3,0.1

River Reach=Clinch River    ,Lower Reach

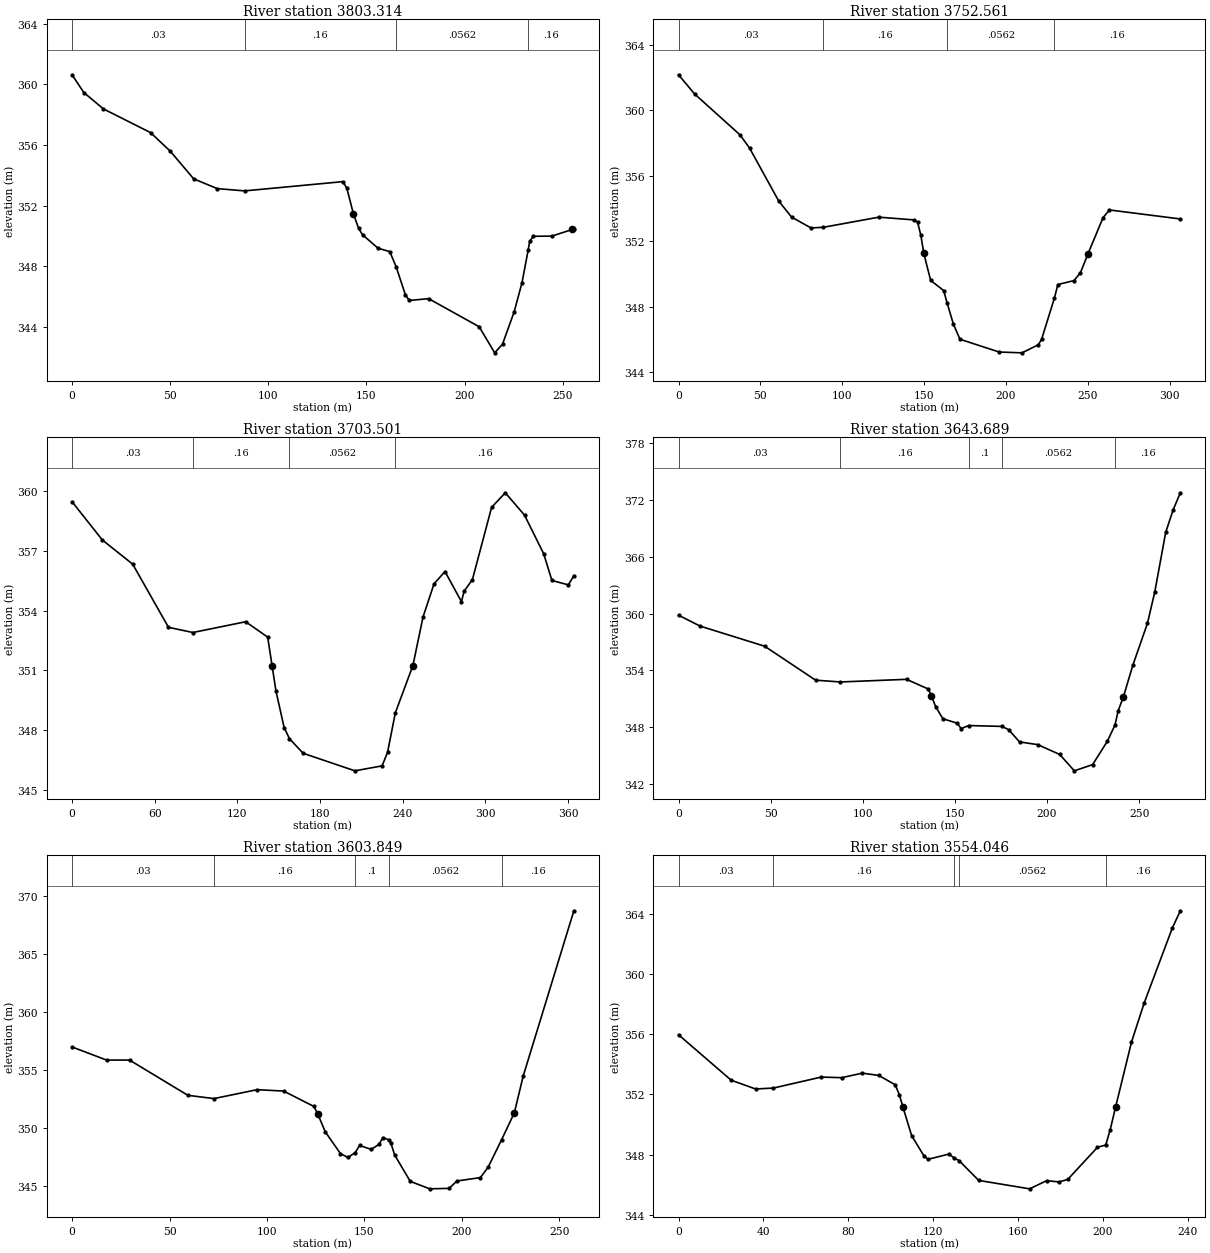
Type RM Length L Ch R = 1 ,3803.314,53.02,50.75,38.45
XS GIS Cut Line= 4
      319953.586     4050383.901     319988.1391     4050529.867
     320007.3026    4050610.8214     320028.1876    4050619.1885
#Sta/Elev= 30
       0  360.63       6  359.46      16  358.38      40  356.82      50   355.6
      62  353.77      74  353.13   87.91  352.98     138  353.59     140  353.16
  143.36  351.47     146  350.51     148  350.09  155.94   349.2  161.88  348.98
  165.11  347.99  169.81  346.15  171.79  345.76  181.69  345.88  207.44  344.03
  215.36  342.31  219.33  342.88  225.27  345.01  229.23  346.91  232.45  349.11
  233.19  349.67  235.07  349.99  244.44     350  254.94  350.44  255.69   350.5
#Mann= 4 ,-1 , 0
       0     .03       0   87.91     .16       0  165.11   .0562       0
  232.45     .16       0
Bank Sta=143.36,254.94
XS Rating Curve= 0 ,0
Exp/Cntr=0.3,0.1

Type RM Length L Ch R = 1 ,3752.561,49.63,49.06,67.83
XS GIS Cut Line= 4
     319899.2076     4050396.827      319937.508    4050541.8549
      319959.387    4050624.7017     320028.7848    4050638.7674
#Sta/Elev= 30
       0  362.18    9.87     361    37.5  358.51   43.42  357.69   61.18  354.46
   69.08  353.47   80.92  352.81   88.45  352.85  122.37  353.47  144.08   353.3
  146.05  353.15  148.03  352.35  149.83  351.25  153.99   349.6  161.96  348.98
  164.03  348.23  167.93  346.91  171.92     346  195.83  345.22  209.78  345.17
  219.75  345.66  221.74  345.99  229.62  348.53   231.7  349.35  241.59  349.59
  245.52  350.08  250.15  351.24  259.29  353.44  263.22  353.91   306.5  353.36
#Mann= 4 ,-1 , 0
       0     .03       0   88.45     .16       0  164.03   .0562       0
  229.62     .16       0
Bank Sta=149.83,250.15
XS Rating Curve= 0 ,0
Exp/Cntr=0.3,0.1

Type RM Length L Ch R = 1 ,3703.501,54.69,59.81,74.06
XS GIS Cut Line= 4
     319851.7715    4050409.3446     319890.0719    4050554.3724
     319914.2879    4050646.0686     320032.5468    4050662.8149
#Sta/Elev= 30
       0  359.46      22  357.54      44  356.33      70  353.16   87.71   352.9
     126  353.44     142  352.67  145.23  351.22     148  349.97  153.95  348.13
  157.84  347.57  167.78  346.84  205.32  345.96  225.08  346.21  229.03  346.89
  234.68  348.87  247.42  351.24  254.79  353.68  262.76  355.34  270.72  355.96
  282.66  354.45  284.65  354.98  290.62  355.55  304.56  359.18  314.51  359.91
  328.45  358.79  342.38  356.85  348.35  355.51   360.3  355.29  364.28  355.75
#Mann= 4 ,-1 , 0
       0     .03       0   87.71     .16       0  157.84   .0562       0
  234.68     .16       0
Bank Sta=145.23,247.42
XS Rating Curve= 0 ,0
Exp/Cntr=0.3,0.1

Type RM Length L Ch R = 1 ,3643.689,39.95,39.84,39.84
XS GIS Cut Line= 4
     319787.2797    4050425.2006      319816.474    4050461.7289
     319835.9722    4050568.5346     319856.9908    4050683.6686
#Sta/Elev= 30
       0  359.82   11.69  358.67   46.76  356.54    74.4  352.95    87.9  352.76
  123.75  353.04  135.59  352.01  137.19  351.32  139.54  350.16  143.49  348.87
  151.38  348.39  153.36  347.83  157.54  348.15  175.49  348.06  179.14  347.72
  185.09  346.42  195.01  346.13  206.91  345.09  214.84  343.36  224.76  344.02
   232.7  346.47  236.92  348.21  238.65  349.72  241.52  351.22  246.58  354.52
  254.52  358.96  258.48  362.26  264.43  368.58   268.4  370.93  272.37  372.77
#Mann= 5 ,-1 , 0
       0     .03       0    87.9     .16       0  157.54      .1       0
  175.49   .0562       0  236.92     .16       0
Bank Sta=137.19,241.52
XS Rating Curve= 0 ,0
Exp/Cntr=0.3,0.1

Type RM Length L Ch R = 1 ,3603.849,52.59,49.8,50.38
XS GIS Cut Line= 5
      319762.478     4050445.651      319786.478    4050462.7566
     319785.2773    4050512.6773     319796.7898    4050575.7398
     319817.2549    4050687.8417
#Sta/Elev= 30
       0  356.99   17.68  355.86   29.47  355.86   59.43  352.81   72.84  352.53
   94.95   353.3  108.55  353.18  124.09  351.85  126.03  351.21  129.91  349.66
  137.68  347.78  141.57  347.44  145.33  347.87  147.51  348.48  153.51  348.14
  157.51  348.58  159.51  349.16  162.38  348.97   163.5  348.73   165.5  347.66
   173.5  345.38   183.5  344.73  193.49  344.77  197.49  345.41  209.49   345.7
  213.48   346.6  220.44  348.99  226.93   351.3  231.48  354.48  257.47  368.76
#Mann= 5 ,-1 , 0
       0     .03       0   72.84     .16       0  145.33      .1       0
  162.38   .0562       0  220.44     .16       0
Bank Sta=126.03,226.93
XS Rating Curve= 0 ,0
Exp/Cntr=0.3,0.1

Type RM Length L Ch R = 1 ,3554.046,27.87,48.27,66.62
XS GIS Cut Line= 6
     319740.5663    4050466.0877     319733.6833    4050497.8211
      319733.427    4050536.4477     319748.4031    4050584.5456
     319765.1369    4050683.1355     319767.6532    4050697.9607
#Sta/Elev= 30
       0  355.96   24.83  352.94   36.33  352.36   44.68  352.42   67.24  353.15
   76.91  353.11    86.6  353.41   94.35  353.26   102.1  352.64  104.04  351.99
  105.78  351.15  109.85  349.27  115.66  347.92   117.6  347.69  127.47  348.04
  129.91  347.78  132.24   347.6  141.47  346.29  165.47  345.73  173.47  346.27
  179.47  346.19  183.47  346.36  197.47  348.49  201.36  348.64  203.47  349.66
     206  351.16  213.47  355.46  219.47  358.07  232.75  363.05  236.51  364.19
#Mann= 5 ,-1 , 0
       0     .03       0   44.68     .16       0  129.91      .1       0
  132.24   .0562       0  201.36     .16       0
Bank Sta=105.78,206
XS Rating Curve= 0 ,0
Exp/Cntr=0.3,0.1