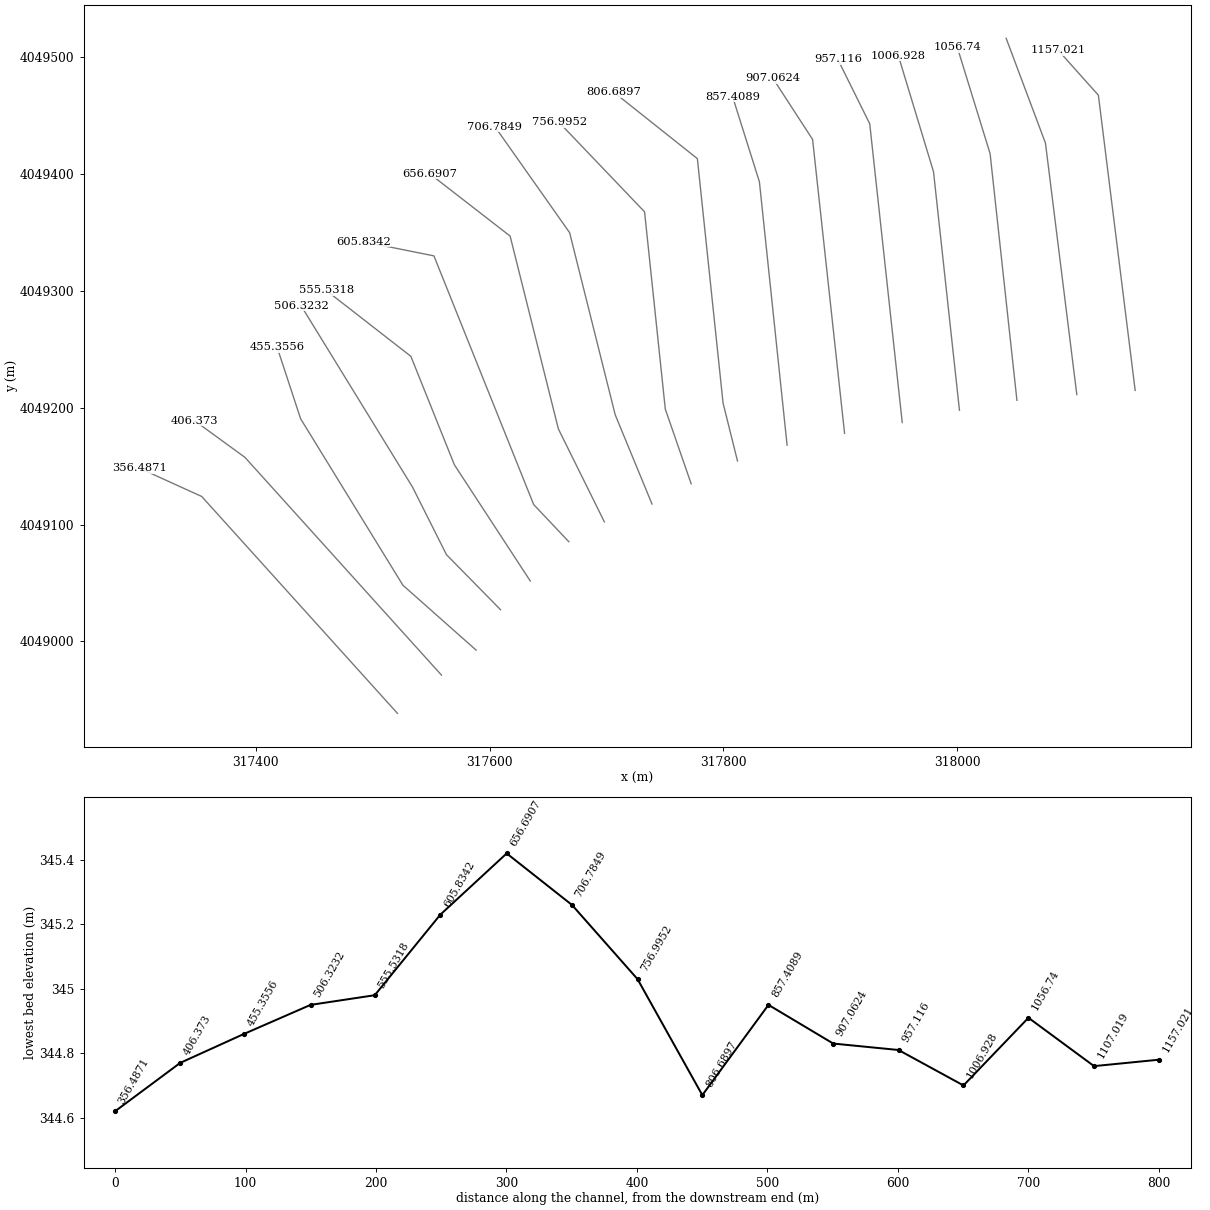
HEC-RAS study WBmod1D.prj: WBmod1D

--- WBmod1D.g08 (geometry) --- (continued)

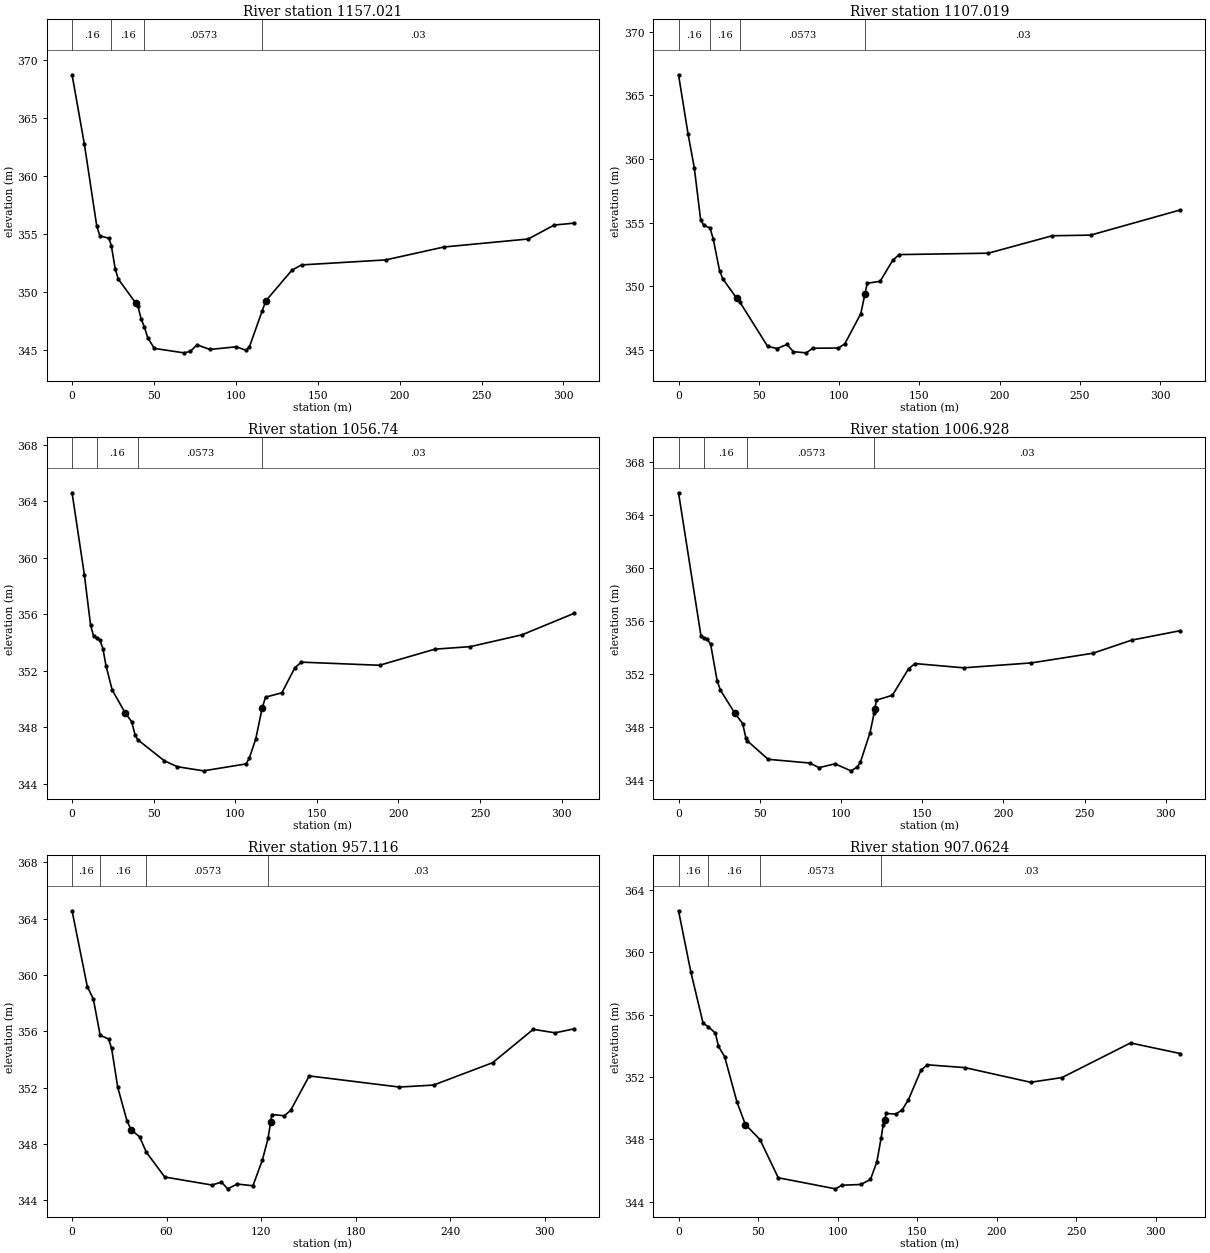
Type RM Length L Ch R = 1 ,1157.021,50.02,50,50
XS GIS Cut Line= 5
     318152.3972    4049214.7814     318148.9058    4049242.7942
     318136.5378    4049342.0264     318120.9116     4049467.401
     318086.4117    4049505.9817
#Sta/Elev= 30
       0  368.69    7.53  362.71   15.06  355.69   16.94  354.85   22.58  354.62
   23.99  353.98   26.35  351.99   28.23  351.12   38.82  349.07   40.23  348.77
   42.23  347.67   44.07  347.03   46.23  346.07   50.23  345.16   68.23  344.78
   72.23   344.9   76.23  345.47   84.23  345.07  100.23   345.3  106.23     345
  108.23  345.28     116  348.36  118.28  349.25  134.15  351.88  140.07  352.34
   191.4  352.77  226.94  353.88  278.46  354.57  294.39  355.77  306.33  355.93
#Mann= 4 ,-1 , 0
       0     .16       0   23.99     .16       0   44.07   .0573       0
     116     .03       0
Bank Sta=38.82,118.28
XS Rating Curve= 0 ,0
Exp/Cntr=0.3,0.1

Type RM Length L Ch R = 1 ,1107.019,51.07,50.28,49.51
XS GIS Cut Line= 5
     318102.4446     4049211.278     318099.2874      4049236.61
     318086.9194    4049335.8422     318075.6384    4049426.3538
     318042.0055     4049516.048
#Sta/Elev= 30
       0  366.61    5.89  361.99    9.82   359.3   13.75  355.23   15.71  354.78
    19.6  354.57    21.6  353.72   25.53  351.23   27.53  350.58   36.26  349.04
   38.25  348.74   55.53  345.26   61.53   345.1   67.53  345.42   71.53  344.85
   79.53  344.76   83.53  345.12   99.53  345.14  103.53  345.46  113.53  347.84
     116  349.33   116.1  349.39  117.53  350.23  125.53  350.38  133.46  352.04
  137.43  352.48  192.95  352.59  232.71  353.96  256.65  354.01  312.53  355.99
#Mann= 4 ,-1 , 0
       0     .16       0    19.6     .16       0   38.25   .0573       0
     116     .03       0
Bank Sta=36.26,116.1
XS Rating Curve= 0 ,0
Exp/Cntr=0.3,0.1

Type RM Length L Ch R = 1 ,1056.74 ,49.82,49.81,49.82
XS GIS Cut Line= 5
     318051.2251    4049206.3175     318048.5678    4049230.7397
      318037.751    4049330.1529     318028.2557    4049417.4204
     318000.2192    4049508.3068
#Sta/Elev= 30
       0  364.61    7.56  358.78   11.34  355.23   13.23  354.44   15.36  354.33
   17.01  354.18    18.9  353.57   20.79  352.36   24.57  350.64   32.48  349.03
   36.57  348.38   38.57  347.47   40.16  347.12   56.57  345.62   64.57   345.2
   80.57  344.91  106.57   345.4  108.57   345.8  112.57  347.18  116.47  349.35
  116.51  349.38  118.57  350.13  128.56  350.44  136.54  352.22  140.53  352.61
  188.41  352.39  222.26  353.53  244.05  353.71  275.76  354.55  307.46  356.06
#Mann= 4 ,-1 , 0
       0     .16       0   15.36     .16       0   40.16   .0573       0
  116.47     .03       0
Bank Sta=32.48,116.51
XS Rating Curve= 0 ,0
Exp/Cntr=0.3,0.1

Type RM Length L Ch R = 1 ,1006.928,49.82,49.81,49.82
XS GIS Cut Line= 5
     318002.0452    4049197.8074     317999.0482    4049225.3516
     317988.2314    4049324.7649     317979.8324    4049401.9561
     317949.7777    4049501.1004
#Sta/Elev= 30
       0  365.67   13.85  354.85    15.6  354.69   17.81  354.61   19.79  354.23
   23.75   351.5   25.73   350.8   34.68  349.04   39.47  348.27   41.43   347.2
   42.46  346.95   55.16  345.57   80.65  345.29   86.53  344.94   96.33  345.23
  106.14   344.7  110.06  344.98  112.02  345.37   117.9  347.58  120.38  349.03
  120.92   349.4  121.82  350.03  131.69   350.4  141.64   352.4  145.63  352.79
  175.49  352.47  217.31  352.84  255.16  353.57  279.07  354.56  308.95  355.27
#Mann= 4 ,-1 , 0
       0     .16       0    15.6     .16       0   42.46   .0573       0
  120.38     .03       0
Bank Sta=34.68,120.92
XS Rating Curve= 0 ,0
Exp/Cntr=0.3,0.1

Type RM Length L Ch R = 1 ,957.116 ,50.06,50.05,50.06
XS GIS Cut Line= 5
     317953.0808     4049187.315     317949.5284    4049219.9635
     317938.7116    4049319.3767      317925.265    4049442.9587
     317897.9487     4049498.048
#Sta/Elev= 30
       0  364.56    9.66  359.18   13.52  358.29   17.83  355.72   23.18  355.45
   25.11  354.79   28.98  352.03   34.84  349.65   37.46  349.01   42.84  348.51
   47.18  347.41   58.84  345.65   88.84  345.08   94.84  345.29   98.84  344.81
  104.84  345.15  114.84  345.03  120.84  346.85  124.44  348.39  126.11  349.55
  126.84  350.09  134.81     350  138.76  350.38   150.6  352.83  207.82  352.04
  229.53  352.18  267.07  353.77  292.86  356.14  306.74  355.89  318.64  356.17
#Mann= 4 ,-1 , 0
       0     .16       0   17.83     .16       0   47.18   .0573       0
  124.44     .03       0
Bank Sta=37.46,126.11
XS Rating Curve= 0 ,0
Exp/Cntr=0.3,0.1

Type RM Length L Ch R = 1 ,907.0624,49.85,49.65,49.47
XS GIS Cut Line= 5
     317903.7384    4049178.0632     317899.7684    4049214.5493
     317888.9516    4049313.9625      317876.378    4049429.5207
     317842.2756     4049482.048
#Sta/Elev= 30
       0  362.65    7.73  358.73   15.45  355.44   18.62  355.23   23.18  354.81
   25.11  353.96   28.97  353.31    36.7  350.41   42.04  348.95   51.21  347.99
    62.7  345.54    98.7  344.83   102.7  345.06   114.7  345.11   120.7  345.43
   124.7  346.55   127.4  348.08   128.7  348.95  129.53  349.24   130.7  349.66
   136.7  349.62  140.64  349.89  144.58  350.54  152.46  352.43   156.4  352.78
  180.05   352.6  221.42  351.66  241.12  351.96  284.25  354.18  315.57   353.5
#Mann= 4 ,-1 , 0
       0     .16       0   18.62     .16       0   51.21   .0573       0
   127.4     .03       0
Bank Sta=42.04,129.53
XS Rating Curve= 0 ,0
Exp/Cntr=0.3,0.1

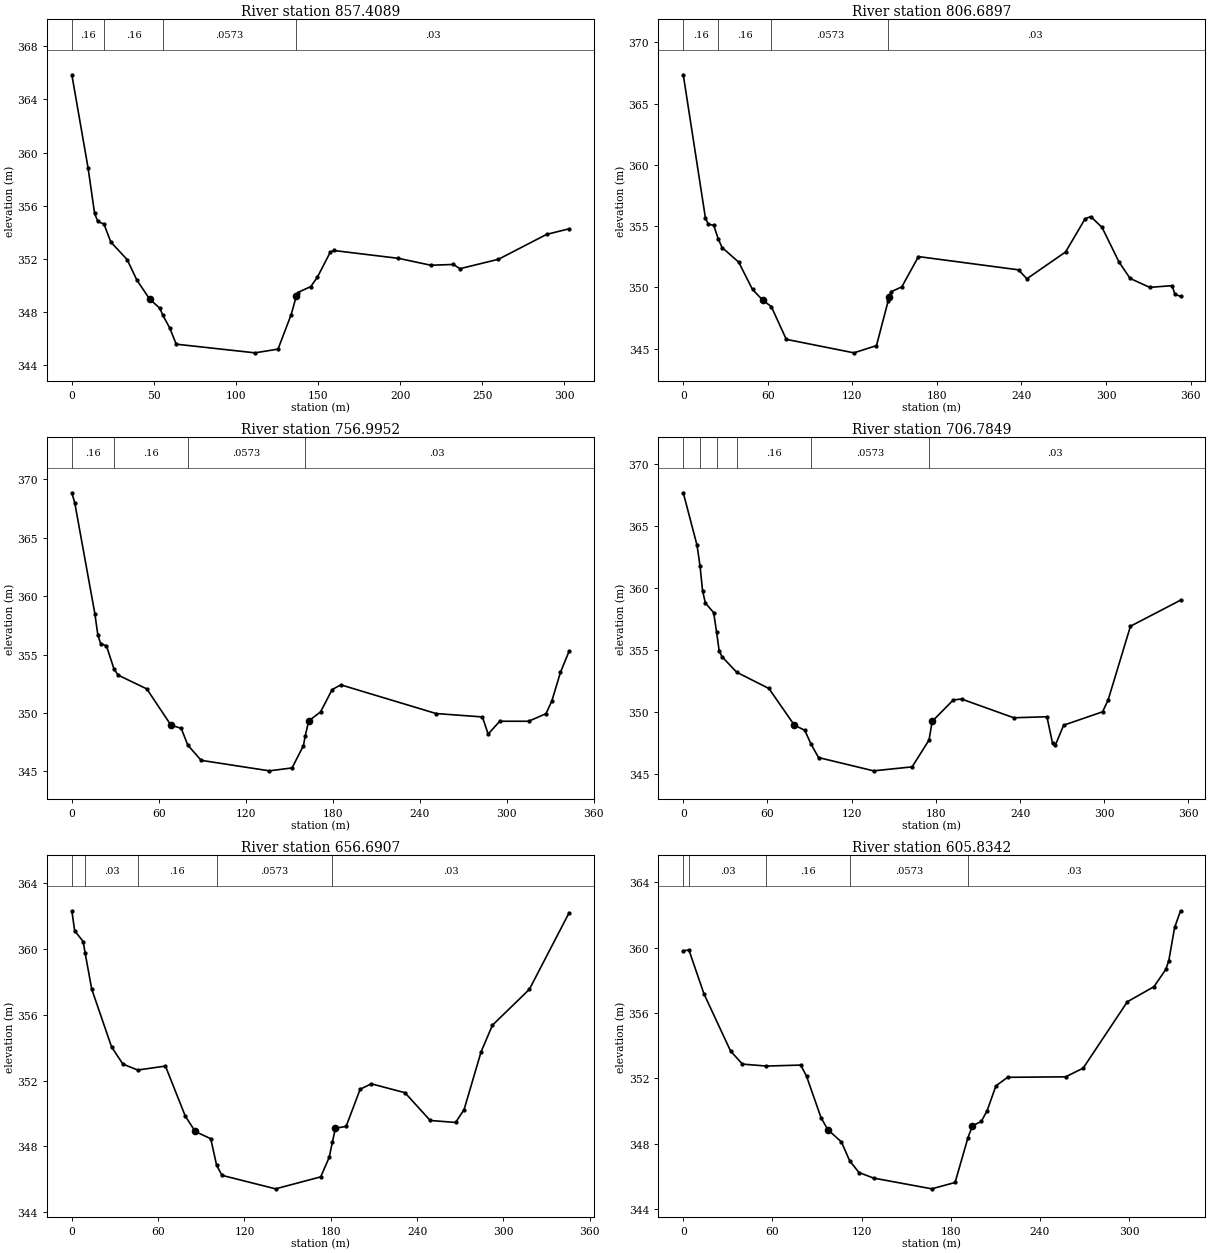
Type RM Length L Ch R = 1 ,857.4089,50.16,50.72,50.73
XS GIS Cut Line= 5
      317854.557    4049167.9495     317850.2111    4049209.2911
     317839.7565    4049308.7431     317830.8695    4049393.2829
     317807.9564     4049466.048
#Sta/Elev= 30
       0  365.84     9.9  358.83   13.86  355.42   15.84  354.82   19.58  354.62
   23.75  353.27   33.65  351.96   39.59  350.42   47.37  348.99   53.57   348.3
   55.48  347.76   59.57  346.83   63.57   345.6  111.57  344.95  125.57  345.23
  133.57  347.82   136.7   349.2  136.72   349.2  137.57  349.48  145.52  349.93
  149.48  350.62  157.38  352.51  159.36  352.64   198.9  352.05  218.67  351.53
  232.44  351.59  236.36  351.27  259.83  351.98  289.17  353.85  302.86  354.27
#Mann= 4 ,-1 , 0
       0     .16       0   19.58     .16       0   55.48   .0573       0
  136.72     .03       0
Bank Sta=47.37,136.7
XS Rating Curve= 0 ,0
Exp/Cntr=0.3,0.1

Type RM Length L Ch R = 1 ,806.6897,49.09,49.69,49.7
XS GIS Cut Line= 6
     317812.1216    4049154.4044     317799.7698    4049203.9886
     317789.3152    4049303.4406     317780.8488    4049383.9792
     317777.7866    4049413.1092     317706.1531     4049470.048
#Sta/Elev= 30
       0  367.35   15.72  355.67   17.69  355.17   21.62  355.06   24.86  353.95
   27.52  353.26   39.31  352.07   49.13  349.84   56.28  348.98   62.49  348.44
    73.1  345.77   121.1  344.67   137.1  345.26  145.43  348.92  146.13  349.21
   147.1  349.63  155.05  350.05   166.9  352.52  237.94  351.44   243.8  350.71
  271.32   352.9  285.24  355.62  289.22  355.78  297.18   354.9  309.11   352.1
  317.07  350.74     331  350.01  346.91  350.15   348.9  349.44  352.88  349.28
#Mann= 4 ,-1 , 0
       0     .16       0   24.86     .16       0   62.49   .0573       0
  145.43     .03       0
Bank Sta=56.28,146.13
XS Rating Curve= 0 ,0
Exp/Cntr=0.3,0.1

Type RM Length L Ch R = 1 ,756.9952,42.23,50.21,57.24
XS GIS Cut Line= 5
      317772.478    4049134.8811     317750.3476    4049198.7932
      317739.893    4049298.2453     317732.6019    4049367.6036
       317659.55     4049444.048
#Sta/Elev= 30
       0  368.86    1.99  368.01   15.91  358.48    17.9   356.7   19.89  355.92
   23.87  355.75   28.96   353.8   31.83  353.24   51.72  352.05   68.36  348.95
   75.48  348.67   79.98  347.24    89.2  345.93  136.26  345.03  151.95  345.28
  159.79  347.19  161.02  348.01  163.44  349.31  171.62  350.08  179.59  351.99
  185.57   352.4  251.34  349.94  283.26  349.65  287.25  348.18  295.23  349.28
  315.18  349.28  327.15  349.93  331.14     351  337.13  353.47  343.11  355.29
#Mann= 4 ,-1 , 0
       0     .16       0   28.96     .16       0   79.98   .0573       0
  161.02     .03       0
Bank Sta=68.36,163.44
XS Rating Curve= 0 ,0
Exp/Cntr=0.3,0.1

Type RM Length L Ch R = 1 ,706.7849,49.54,50.09,50.1
XS GIS Cut Line= 5
     317738.9719    4049117.5541     317707.4606    4049193.9858
     317683.1854    4049290.9947     317668.4697     4049349.802
      317604.478    4049440.5994
#Sta/Elev= 30
       0  367.68    9.84  363.43   11.95  361.76   13.78  359.76   15.75  358.79
   21.65  358.02   23.75  356.44   25.59  354.92   27.56  354.47   38.07  353.21
   61.02   351.9   79.18  348.94   86.59  348.53   91.06  347.41    96.4  346.33
  135.61  345.26  163.06  345.58  175.13  347.74  177.38  349.25  192.45  350.98
  198.32  351.05  235.47  349.54  259.16  349.62  263.13  347.49  265.11  347.32
  271.06  348.94  298.83  350.02   302.8  350.99  318.67  356.92  354.37  359.02
#Mann= 6 ,-1 , 0
       0     .16       0   11.95      .1       0   23.75     .03       0
   38.07     .16       0   91.06   .0573       0  175.13     .03       0
Bank Sta=79.18,177.38
XS Rating Curve= 0 ,0
Exp/Cntr=0.3,0.1

Type RM Length L Ch R = 1 ,656.6907,44.6,50.86,57.75
XS GIS Cut Line= 5
     317698.2016    4049102.3244     317658.8648    4049181.8254
     317634.5896    4049278.8343       317617.57    4049346.8484
     317548.9397     4049400.048
#Sta/Elev= 30
       0  362.34    1.97  361.12    7.88  360.47    9.28  359.75    13.8  357.58
    27.6  354.06   35.48  353.01   45.79  352.65   65.05  352.89   78.84  349.85
   85.74  348.91   96.54  348.47  100.65  346.85  104.39  346.24  141.64  345.42
  173.01  346.15   178.9  347.34  181.04  348.25  183.25  349.11  190.65  349.22
  200.39  351.48  208.18  351.81  231.55  351.27  249.07  349.58  266.71  349.46
  272.63  350.24  284.47  353.76  292.36  355.38  318.02  357.56  345.65  362.22
#Mann= 5 ,-1 , 0
       0      .1       0    9.28     .03       0   45.79     .16       0
  100.65   .0573       0  181.04     .03       0
Bank Sta=85.74,183.25
XS Rating Curve= 0 ,0
Exp/Cntr=0.3,0.1

Type RM Length L Ch R = 1 ,605.8342,48.84,50.3,50.66
XS GIS Cut Line= 6
     317667.7723    4049085.3423     317637.7067    4049117.1515
     317616.5599    4049169.8702     317579.3309    4049262.6819
     317552.3663    4049329.9044     317491.9297     4049342.048
#Sta/Elev= 30
       0  359.81     3.8  359.86   13.93  357.17   31.83  353.67   39.79  352.87
   55.81  352.75   79.03  352.81   82.94  352.13   92.74  349.58   97.23  348.86
  106.45   348.1  111.96  346.95  118.22  346.23  128.02  345.89  167.24  345.23
  182.92  345.62  191.57  348.36  194.58  349.09  200.57  349.36  204.49  350.02
  210.36  351.53  218.19  352.06  257.34  352.09  269.09  352.62  298.85  356.69
  316.75  357.61   324.7  358.67  326.69  359.19  330.67  361.24  334.64  362.26
#Mann= 5 ,-1 , 0
       0      .1       0     3.8     .03       0   55.81     .16       0
  111.96   .0573       0  191.57     .03       0
Bank Sta=97.23,194.58
XS Rating Curve= 0 ,0
Exp/Cntr=0.3,0.1

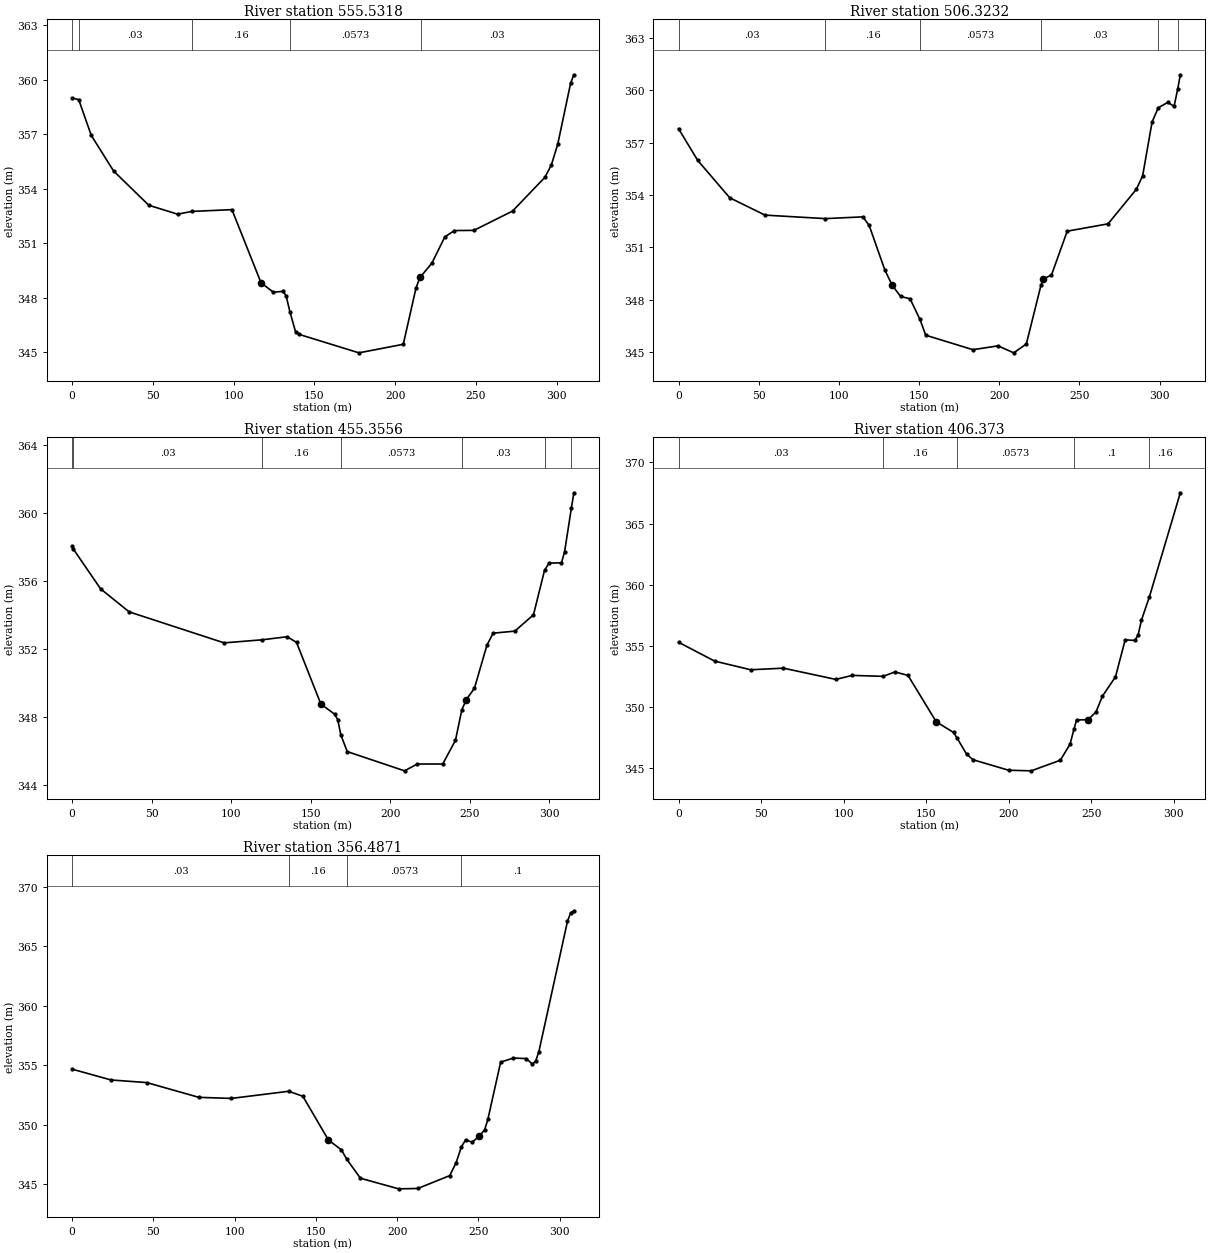
Type RM Length L Ch R = 1 ,555.5318,41.59,49.21,57.69
XS GIS Cut Line= 4
     317634.8213    4049051.7047     317569.8734    4049151.1431
     317532.6444    4049243.9548     317460.1466    4049300.3794
#Sta/Elev= 30
       0  358.99    4.13  358.89   11.88  356.93   25.73  354.97   47.51  353.09
   65.32   352.6   74.06  352.75   98.97  352.85  116.98  348.83  124.65  348.31
  130.53  348.36   132.5  348.12  134.89  347.22  138.38  346.13  140.34     346
  177.59  344.98  205.04  345.45  212.89  348.53  215.34  349.13  215.84  349.17
  222.76  349.91  230.75  351.35  236.74   351.7  248.73  351.71  272.69  352.77
  292.66  354.62  296.66  355.29  300.65  356.44  308.64   359.8  310.64  360.26
#Mann= 5 ,-1 , 0
       0      .1       0    4.13     .03       0   74.06     .16       0
  134.89   .0573       0  215.84     .03       0
Bank Sta=116.98,215.34
XS Rating Curve= 0 ,0
Exp/Cntr=0.3,0.1

Type RM Length L Ch R = 1 ,506.3232,50.4,50.97,48.95
XS GIS Cut Line= 5
     317609.3383    4049027.1877     317563.0994    4049074.2391
     317534.0661     4049132.045     317481.7199      4049217.25
     317438.6291    4049287.3899
#Sta/Elev= 30
       0  357.79   11.99  355.97   31.98  353.83   53.97  352.84   91.56  352.64
  114.97  352.74  118.89  352.25   128.7  349.69  133.29  348.82   138.5  348.18
  144.38  348.05  150.55  346.87  154.19  345.96   183.6  345.13  199.28  345.35
  209.09  344.95  216.93  345.46  226.02  348.81  227.49  349.18  232.62  349.41
  242.42  351.92   267.9  352.34  285.54  354.32  289.46  355.09  295.34  358.17
  299.22  358.99  305.14   359.3  309.06  359.07   311.3  360.05  312.97  360.88
#Mann= 6 ,-1 , 0
       0     .03       0   91.56     .16       0  150.55   .0573       0
  226.02     .03       0  299.22      .1       0   311.3     .16       0
Bank Sta=133.29,227.49
XS Rating Curve= 0 ,0
Exp/Cntr=0.3,0.1

Type RM Length L Ch R = 1 ,455.3556,38.64,48.98,62.83
XS GIS Cut Line= 5
      317588.478    4048992.5728     317525.8222    4049048.0972
     317490.6391    4049105.3655      317438.293    4049190.5704
     317418.1895    4049251.7595
#Sta/Elev= 30
       0  358.03     .63   357.9   17.94  355.54   35.88  354.19   95.58  352.37
  119.33  352.55  135.12  352.73  141.05   352.4  156.35  348.78  164.93  348.19
  166.93  347.87  168.93  346.96  172.93  345.99  208.93  344.86  216.93  345.26
  232.93  345.26  240.93  346.65  244.93  348.44  247.75  349.04  252.88  349.71
  260.69  352.23  264.59  352.94  278.25  353.06  289.96  354.02  296.89  356.62
  299.72  357.05  307.53  357.07  309.48   357.7  313.76  360.27  315.34  361.18
#Mann= 7 ,-1 , 0
       0      .1       0     .63     .03       0  119.33     .16       0
  168.93   .0573       0  244.93     .03       0  296.89      .1       0
  313.76     .16       0
Bank Sta=156.35,247.75
XS Rating Curve= 0 ,0
Exp/Cntr=0.3,0.1

Type RM Length L Ch R = 1 ,406.373 ,49.95,49.89,51.55
XS GIS Cut Line= 4
     317558.8118    4048971.2016     317457.7115    4049083.2281
     317390.7139    4049157.4664     317347.8281    4049188.6979
#Sta/Elev= 30
       0  355.29   21.84  353.75   43.68  353.04   63.54  353.17   95.31  352.25
  105.23  352.58  123.87   352.5  131.05  352.86  138.99  352.58   156.1  348.78
  166.59  347.91  168.82  347.43  174.43  346.14  178.35  345.68  199.92  344.82
  213.65  344.77  231.29  345.64  237.18  346.96   239.5  348.17   241.1  348.93
   248.1  348.96  252.87  349.59   256.8  350.89  264.66  352.46  270.55  355.49
  276.45  355.44  278.41   355.9  280.37  357.08  285.27  359.03  303.95  367.52
#Mann= 5 ,-1 , 0
       0     .03       0  123.87     .16       0  168.82   .0573       0
   239.5      .1       0  285.27     .16       0
Bank Sta=156.1,248.1
XS Rating Curve= 0 ,0
Exp/Cntr=0.3,0.1

Type RM Length L Ch R = 1 ,356.4871,34.58,34.57,36.99
XS GIS Cut Line= 4
     317521.1733    4048938.4483      317420.677    4049049.8057
     317353.6794     4049124.044     317300.1798    4049148.3462
#Sta/Elev= 30
       0  354.68      24  353.77      46  353.55      78  352.31      98  352.22
  133.35  352.82     142   352.4  157.77  348.72  165.69   347.9  169.11  347.09
  177.45  345.51  200.98  344.62  212.74  344.65  232.35  345.73  236.27   346.8
  239.56  348.15  242.16  348.74  246.08  348.54  250.45  349.02  253.92   349.6
  255.88  350.48  263.71  355.27  271.55  355.61  279.38  355.57   283.3   355.1
  285.26  355.36  287.21  356.14  304.84  367.11   306.8  367.82  308.76  367.99
#Mann= 4 ,-1 , 0
       0     .03       0  133.35     .16       0  169.11   .0573       0
  239.56      .1       0
Bank Sta=157.77,250.45
XS Rating Curve= 0 ,0
Exp/Cntr=0.3,0.1