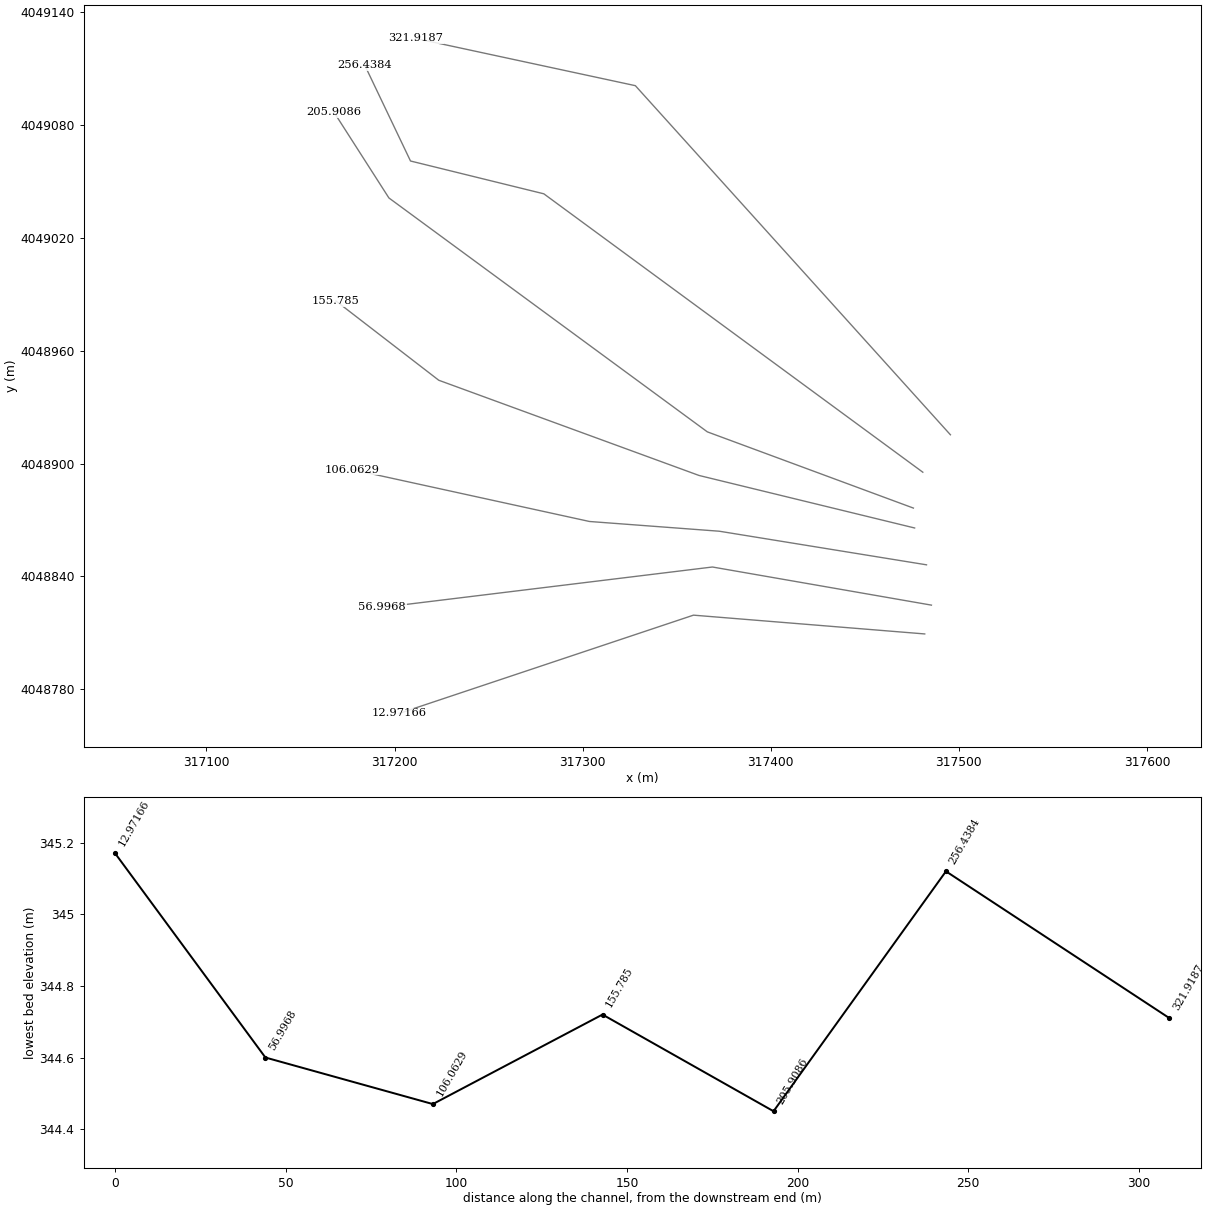
HEC-RAS study WBmod1D.prj: WBmod1D

--- WBmod1D.g08 (geometry) --- (continued)

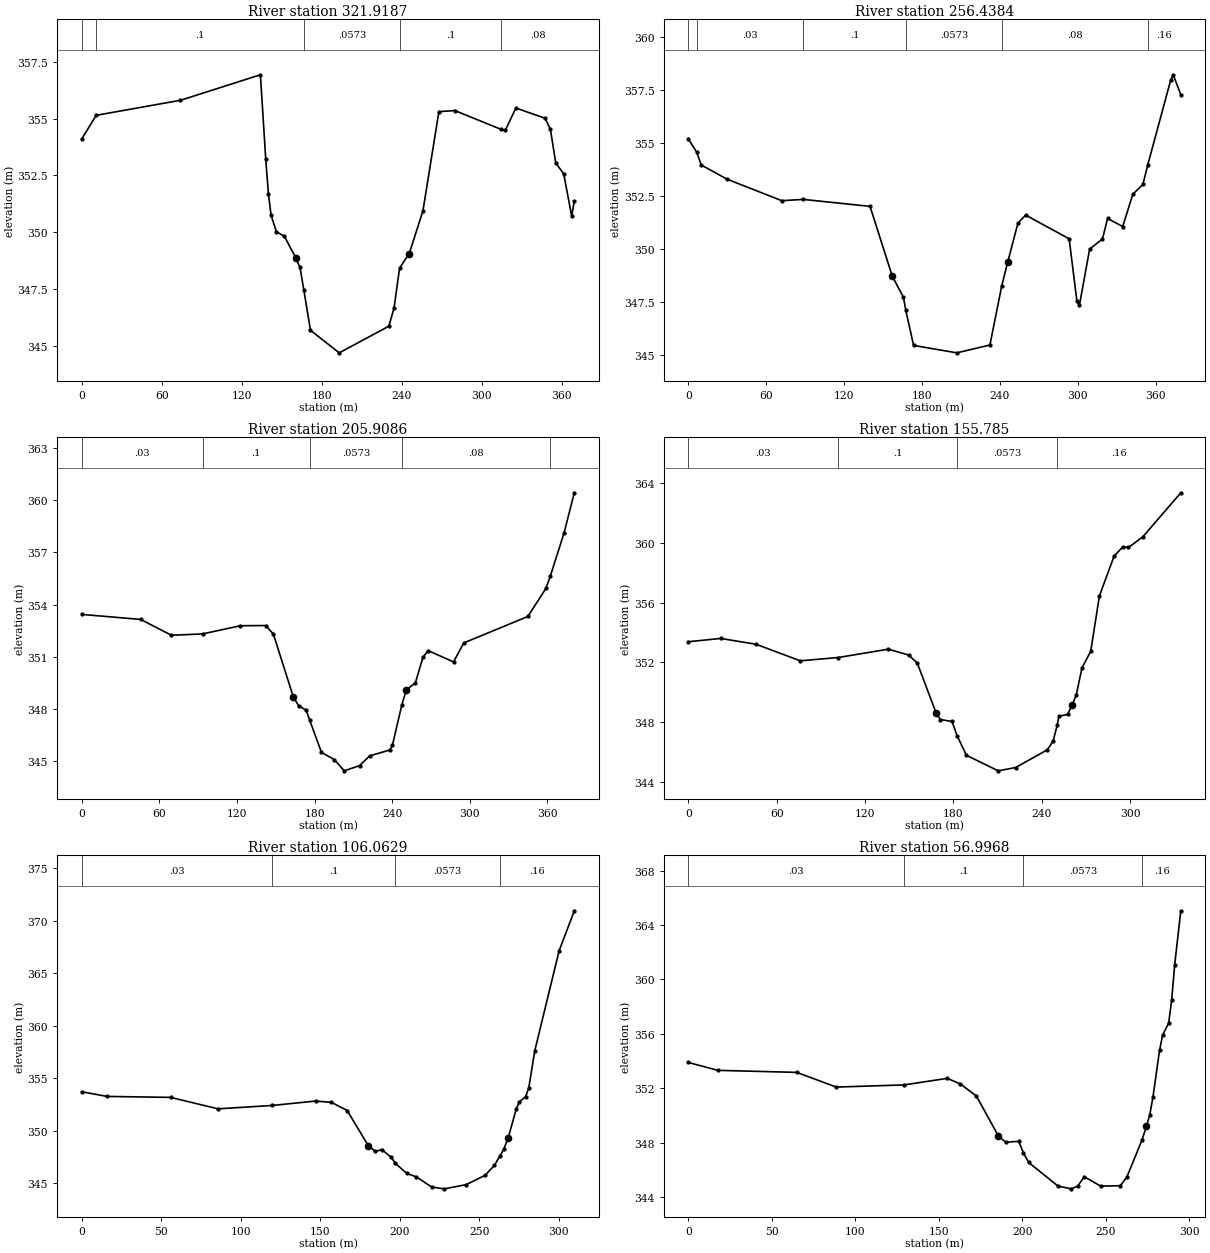
Type RM Length L Ch R = 1 ,321.9187,54.12,65.48,74.13
XS GIS Cut Line= 4
     317495.5103    4048915.2883      317395.014    4049026.6457
     317328.0164     4049100.884     317211.1221     4049126.048
#Sta/Elev= 30
       0  354.11   10.75  355.14      74   355.8     134  356.92     138   353.2
     140   351.7     142  350.75     146  350.03  151.96  349.83  160.57  348.88
  163.73  348.46  166.63  347.45  171.57   345.7  193.14  344.71  230.39  345.88
  234.31  346.69  238.43  348.43  245.71  349.07  255.98  350.95  267.94   355.3
  279.89  355.35  314.65  354.52  317.76  354.48  325.73  355.46  347.65  355.01
  351.64  354.52  355.62  353.05   361.6  352.57  367.58  350.72  369.57  351.38
#Mann= 5 ,-1 , 0
       0     .03       0   10.75      .1       0  166.63   .0573       0
  238.43      .1       0  314.65     .08       0
Bank Sta=160.57,245.71
XS Rating Curve= 0 ,0
Exp/Cntr=0.3,0.1

Type RM Length L Ch R = 1 ,256.4384,50.69,50.53,48.8
XS GIS Cut Line= 5
     317480.8344    4048895.3885      317359.947    4048984.1927
     317279.3553    4049043.3956      317208.478     4049060.836
     317184.1717    4049111.7417
#Sta/Elev= 30
       0  355.22    6.48  354.58      10  353.98      30  353.31      72   352.3
    88.6  352.36     140  352.03  157.17  348.73  165.69  347.75   167.5  347.14
  173.53  345.47  206.86  345.12  232.35  345.49   241.5  348.29     246  349.39
  253.95  351.24  259.86  351.62   293.4   350.5  299.32  347.58  301.29  347.36
  309.18  350.02  319.05  350.49  322.99  351.46  334.66  351.08  342.44   352.6
  350.22  353.07  353.96  353.99  371.62  357.99  373.57  358.24   379.4   357.3
#Mann= 6 ,-1 , 0
       0      .1       0    6.48     .03       0    88.6      .1       0
   167.5   .0573       0   241.5     .08       0  353.96     .16       0
Bank Sta=157.17,246
XS Rating Curve= 0 ,0
Exp/Cntr=0.3,0.1

Type RM Length L Ch R = 1 ,205.9086,33.57,50.12,63.77
XS GIS Cut Line= 6
     317475.8265    4048876.3234     317366.2822    4048916.8402
     317330.0318    4048943.4699     317249.4401    4049002.6728
     317196.9949    4049041.1992     317167.8832    4049086.6428
#Sta/Elev= 30
       0  353.44   45.53  353.15   69.29  352.24   93.44  352.32  122.66  352.79
  142.22   352.8  148.09  352.31  163.66  348.67  167.66  348.19  173.54  347.93
  176.12  347.37  185.31  345.51  195.11   345.1  202.95  344.45  214.72  344.75
  222.56  345.31  238.25  345.65  240.21  345.94   247.4  348.23  250.91  349.11
  257.86   349.5  263.75  350.97  267.69  351.36  287.41  350.71   295.3   351.8
  344.84  353.32  358.83  354.93  362.34  355.66  372.83  358.11  380.82  360.43
#Mann= 5 ,-1 , 0
       0     .03       0   93.44      .1       0  176.12   .0573       0
   247.4     .08       0  362.34     .16       0
Bank Sta=163.66,250.91
XS Rating Curve= 0 ,0
Exp/Cntr=0.3,0.1

Type RM Length L Ch R = 1 ,155.785 ,40.48,49.72,56.84
XS GIS Cut Line= 5
     317476.4879      4048865.74     317361.8644    4048893.6606
     317317.4283    4048909.9165     317223.5152    4048944.2725
     317168.8521    4048986.4221
#Sta/Elev= 30
       0  353.38      22   353.6   45.99  353.21   75.98   352.1  101.71  352.32
  135.72  352.88  149.52  352.49  155.43  351.95  168.29  348.58  171.17  348.16
  179.02  348.03  182.39  347.09  188.82  345.76  210.39  344.72  222.15  344.94
  243.72  346.13  247.64  346.71  250.41  347.78  251.57  348.38  257.45   348.5
  260.44  349.11  263.33   349.8  267.26  351.63  273.18  352.74   279.1  356.46
  288.96   359.1  294.87  359.74  298.82   359.7  308.68  360.43  334.32  363.37
#Mann= 4 ,-1 , 0
       0     .03       0  101.71      .1       0  182.39   .0573       0
  250.41     .16       0
Bank Sta=168.29,260.44
XS Rating Curve= 0 ,0
Exp/Cntr=0.3,0.1

Type RM Length L Ch R = 1 ,106.0629,30.91,49.07,64.91
XS GIS Cut Line= 5
     317482.7969    4048846.1564     317372.6639    4048864.0158
     317303.6526    4048869.1923     317207.4705    4048890.2333
     317177.5658    4048896.7753
#Sta/Elev= 30
       0  353.71   15.94  353.27   55.79  353.18   85.67  352.09  119.78  352.41
  147.16  352.83  157.05   352.7  166.94  351.93  180.23  348.58  184.72  348.03
  188.65  348.21  194.56  347.49  197.23   346.9  204.41  345.94  210.31  345.62
  220.16  344.64  228.04  344.47  241.82  344.87  253.63  345.75  259.54   346.7
  263.11  347.62  265.45  348.23  268.24  349.32  273.33  352.09   275.3  352.75
  279.23  353.26  281.15  354.06  284.97  357.62  300.28  367.14  309.85  370.95
#Mann= 4 ,-1 , 0
       0     .03       0  119.78      .1       0  197.23   .0573       0
  263.11     .16       0
Bank Sta=180.23,268.24
XS Rating Curve= 0 ,0
Exp/Cntr=0.3,0.1

Type RM Length L Ch R = 1 ,56.9968 ,32.8,44.03,55.2
XS GIS Cut Line= 5
     317485.4176    4048824.7295     317368.9895    4048844.9961
     317305.3277    4048837.2169      317206.066    4048825.0877
      317193.435    4048823.5442
#Sta/Elev= 30
       0  353.89   17.73  353.31      65  353.16   88.63  352.08  129.27  352.24
  155.11  352.72  162.88  352.32   172.6  351.42  185.79  348.48  190.16  348.03
     198  348.09  200.72  347.26  203.88  346.54  221.53   344.8  229.37   344.6
  233.29   344.8  237.22  345.49  247.02   344.8  258.78  344.83  262.71  345.46
   271.9  348.22  274.43  349.19  276.43  350.02  278.39  351.37  282.31  354.77
  284.13  355.89  287.77  356.79  289.59  358.48   291.4  361.09  295.04  365.04
#Mann= 4 ,-1 , 0
       0     .03       0  129.27      .1       0  200.72   .0573       0
   271.9     .16       0
Bank Sta=185.79,274.43
XS Rating Curve= 0 ,0
Exp/Cntr=0.3,0.1

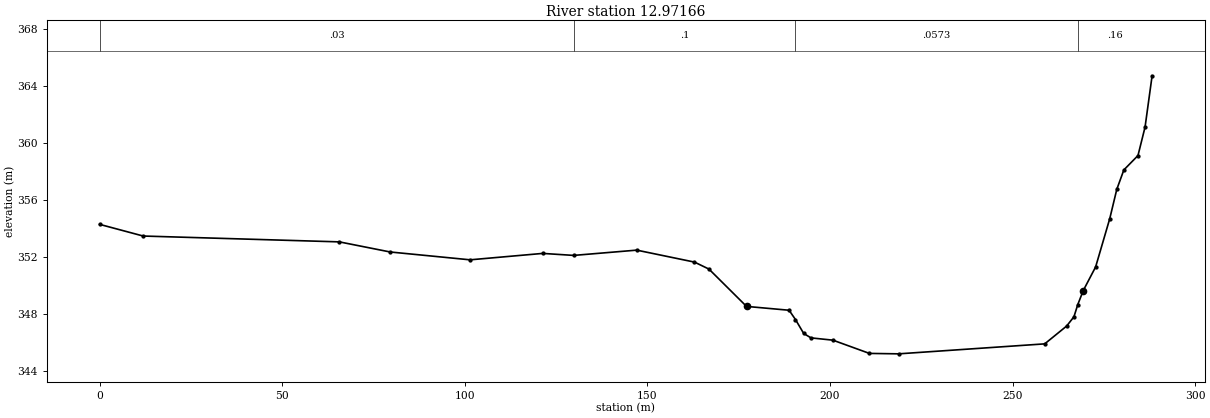
Type RM Length L Ch R = 1 ,12.97166,16.12,12.97,13.25
XS GIS Cut Line= 5
      317481.859    4048809.4101     317358.9155    4048819.3992
     317313.8852    4048804.3645     317219.0324    4048772.6953
     317202.5205    4048767.1823
#Sta/Elev= 30
       0  354.26   11.94  353.44   65.65  353.03   79.58  352.32  101.46  351.77
  121.36  352.22  129.83  352.08  147.09  352.45  162.91  351.61  166.87  351.12
  177.16   348.5  188.82  348.23  190.56  347.58  192.82   346.6  194.82  346.29
  200.82  346.13  210.82   345.2  218.82  345.17  258.82  345.87  264.82  347.12
  266.82  347.77  267.88  348.63  269.37  349.61  272.76  351.27  276.63  354.66
  278.56  356.72  280.49  358.08  284.36  359.09   286.3  361.09  288.23  364.69
#Mann= 4 ,-1 , 0
       0     .03       0  129.83      .1       0  190.56   .0573       0
  267.88     .16       0
Bank Sta=177.16,269.37
XS Rating Curve= 0 ,0
Exp/Cntr=0.3,0.1
LCMann Table=0

--- WBmod1D.g09 (geometry) ---

Geom Title=WBgeom1D
Program Version=5.07

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
River Reach=Clinch River    ,Upper Reach

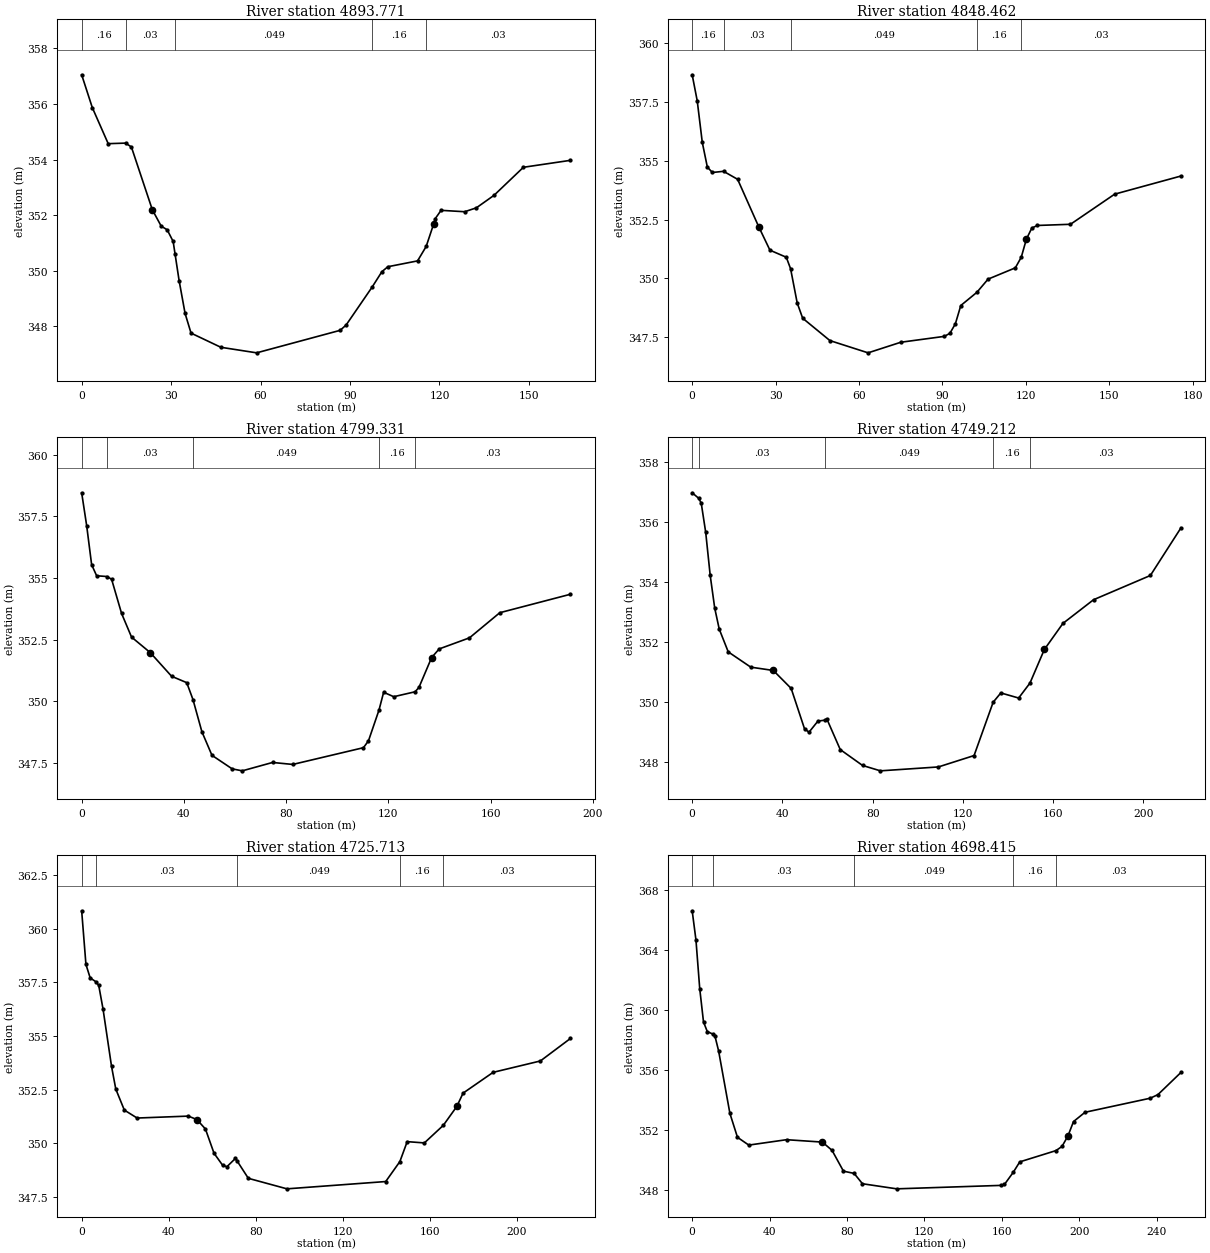
Type RM Length L Ch R = 1 ,4893.771,44.6,45.31,43.51
XS GIS Cut Line= 4
     320729.9764    4049882.4458     320739.5355    4049887.2116
     320829.0295    4049931.8302     320876.6807    4049955.5874
#Sta/Elev= 30
       0  357.05    3.56  355.87     8.9  354.57   14.74  354.59   16.68  354.45
    23.7  352.19   26.68   351.6   28.68  351.47   30.68  351.05   31.32   350.6
   32.68  349.64   34.68  348.46   36.68  347.75   46.68  347.24   58.68  347.04
   86.68  347.85   88.68  348.04   97.43  349.41  100.68  349.96  102.68  350.14
  112.65  350.35  115.54  350.87  118.05  351.68  118.57  351.87  120.54  352.17
  128.43  352.12  132.37  352.26  138.29  352.71  148.15  353.72  163.93  353.97
#Mann= 5 ,-1 , 0
       0     .16       0   14.74     .03       0   31.32    .049       0
   97.43     .16       0  115.54     .03       0
Bank Sta=23.7,118.05
XS Rating Curve= 0 ,0
Exp/Cntr=0.3,0.1

Type RM Length L Ch R = 1 ,4848.462,47.67,49.13,49.02
XS GIS Cut Line= 4
      320710.478    4049913.9269     320720.8694     4049928.816
     320810.5881    4049972.9812     320865.8832    4049989.1218
#Sta/Elev= 30
       0  358.65    1.82  357.54    3.63  355.78    5.45  354.73    7.26   354.5
   11.28  354.55   16.34  354.21   23.91   352.2   27.96   351.2   33.84   350.9
   35.39  350.41   37.76  348.96   39.73  348.31   49.53  347.36   63.25  346.84
   75.02  347.29   90.71  347.54   92.67  347.67   94.63  348.07   96.59  348.85
  102.37  349.41  106.39  349.97   116.2  350.45  118.33   350.9  120.18  351.67
  122.13  352.14  124.12  352.25  136.03   352.3  151.92  353.58  175.76  354.35
#Mann= 5 ,-1 , 0
       0     .16       0   11.28     .03       0   35.39    .049       0
  102.37     .16       0  118.33     .03       0
Bank Sta=23.91,120.18
XS Rating Curve= 0 ,0
Exp/Cntr=0.3,0.1

Type RM Length L Ch R = 1 ,4799.331,50.26,50.12,50.04
XS GIS Cut Line= 4
     320677.1605    4049950.7305     320699.1708    4049972.8953
     320794.8941    4050020.0163     320847.0184    4050031.4049
#Sta/Elev= 30
       0  358.46    1.95  357.13     3.9  355.54    5.86  355.09     9.9  355.06
   11.71  354.95   15.62  353.56   19.52   352.6   26.85  351.97   35.19  351.01
   41.12  350.75   43.57  350.06   47.04  348.76   50.99   347.8    58.9  347.25
   62.85  347.17    74.7  347.51   82.61  347.43  110.27  348.11  112.24  348.39
  116.36  349.64  118.17  350.36  122.12  350.18  130.48  350.38     132  350.56
  136.95  351.77  139.91  352.12  151.76  352.57  163.62  353.59  191.28  354.34
#Mann= 5 ,-1 , 0
       0     .16       0     9.9     .03       0   43.57    .049       0
  116.36     .16       0  130.48     .03       0
Bank Sta=26.85,136.95
XS Rating Curve= 0 ,0
Exp/Cntr=0.3,0.1

Type RM Length L Ch R = 1 ,4749.212,19.57,23.5,12.37
XS GIS Cut Line= 4
     320645.7347    4049986.7913     320669.2309    4050014.0194
      320777.424    4050067.2789      320836.478    4050078.3248
#Sta/Elev= 30
       0  356.98    2.82   356.8       4  356.64    5.99  355.66    7.99  354.22
    9.99  353.13   11.99  352.43   15.98  351.67   25.97  351.16   35.96  351.05
   43.87  350.45    49.8   349.1   51.78  348.99   55.73  349.36    58.7  349.39
   59.69  349.43   65.62  348.41    75.5  347.88   83.41   347.7  109.11  347.83
  124.93  348.21  133.39  349.99  136.79   350.3  144.69  350.13  149.71  350.63
  156.08  351.75  164.31  352.62  177.87  353.41  203.07  354.22  216.63  355.81
#Mann= 5 ,-1 , 0
       0     .16       0    2.82     .03       0    58.7    .049       0
  133.39     .16       0  149.71     .03       0
Bank Sta=35.96,156.08
XS Rating Curve= 0 ,0
Exp/Cntr=0.3,0.1

Type RM Length L Ch R = 1 ,4725.713,31.14,27.3,29.3
XS GIS Cut Line= 4
     320629.8557    4049994.6365     320662.6549    4050036.2249
      320722.478    4050066.5906     320824.4461     4050090.426
#Sta/Elev= 30
       0  360.84    1.96  358.34    3.92  357.71    6.58  357.53    7.85  357.36
    9.81  356.27   13.73  353.59   15.69  352.53   19.62  351.55    25.5  351.18
   49.04  351.27   52.97  351.11   56.91  350.67   60.86  349.54   64.81  348.98
   66.78  348.91   70.72   349.3   71.54  349.17   76.64  348.37    94.4  347.88
  139.81  348.22  146.32  349.15  149.69  350.08  157.59  350.02   166.3  350.84
  172.51  351.72  175.38  352.34  189.21  353.31  210.94  353.84  224.77  354.89
#Mann= 5 ,-1 , 0
       0     .16       0    6.58     .03       0   71.54    .049       0
  146.32     .16       0   166.3     .03       0
Bank Sta=52.97,172.51
XS Rating Curve= 0 ,0
Exp/Cntr=0.3,0.1

Type RM Length L Ch R = 1 ,4698.415,50.19,50.23,55.05
XS GIS Cut Line= 5
     320609.4483    4050007.0777     320640.1808    4050056.8439
      320712.838    4050091.7937     320732.8593    4050101.4244
      320822.844     4050116.414
#Sta/Elev= 30
       0  366.61    1.95  364.66     3.9  361.41    5.85  359.19     7.8  358.55
   10.98  358.36    11.7  358.28   13.65  357.26    19.5  353.08    23.4  351.49
   29.25  350.97   48.74  351.33   67.28  351.17   72.26  350.62   78.16  349.23
   83.67  349.08   87.99  348.39  105.69  348.05  159.48  348.28  161.33  348.34
  165.88  349.15  169.27  349.85  187.93   350.6  191.08  350.88  194.16  351.58
  197.03  352.54  202.98  353.16  236.69   354.1  240.66  354.34  252.56  355.82
#Mann= 5 ,-1 , 0
       0     .16       0   10.98     .03       0   83.67    .049       0
  165.88     .16       0  187.93     .03       0
Bank Sta=67.28,194.16
XS Rating Curve= 0 ,0
Exp/Cntr=0.3,0.1

River Reach=Side Channel    ,Side Reach

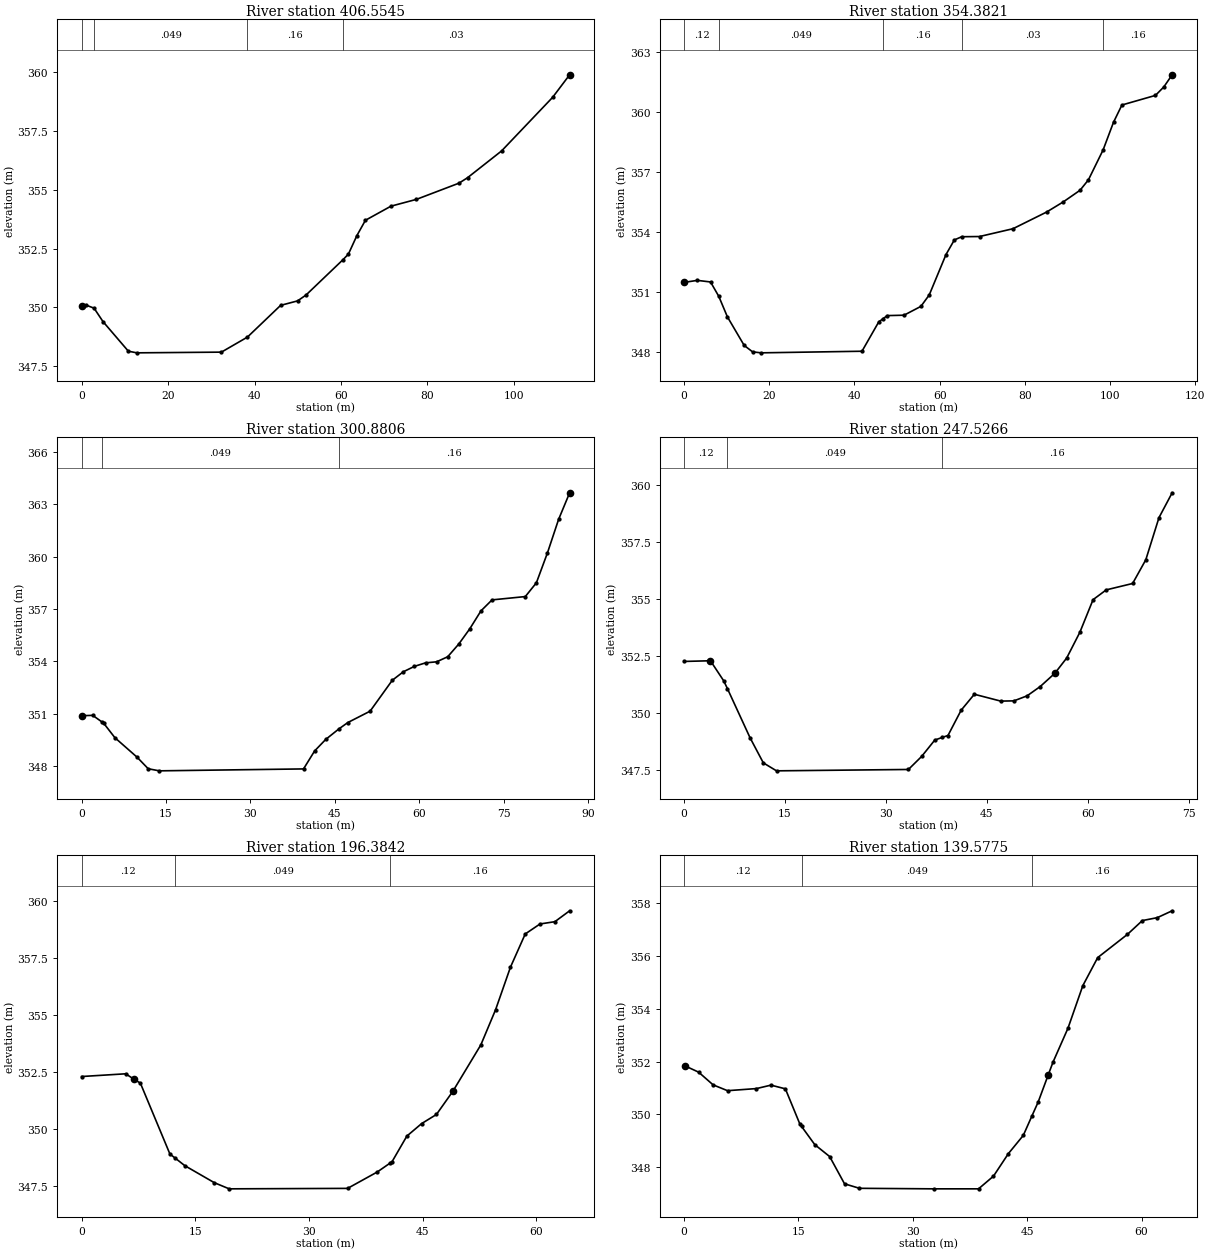
Type RM Length L Ch R = 1 ,406.5545,50.34,52.17,53.22
XS GIS Cut Line= 4
     320690.4575    4050136.7511     320691.4209    4050137.1041
     320744.7176    4050156.6323     320796.4729    4050175.5958
#Sta/Elev= 22
       0  350.08    1.03   350.1    2.88  349.97    4.94   349.4   10.81  348.14
   12.77  348.07   32.34   348.1   38.36  348.74   46.04  350.09   49.96  350.28
   51.92  350.53   60.45  352.03   61.72  352.27   63.69  353.06   65.66  353.71
   71.57  354.31   77.47   354.6   87.32  355.29   89.28  355.52   97.16  356.66
  108.97  358.94  112.91   359.9
#Mann= 4 ,-1 , 0
       0     .12       0    2.88    .049       0   38.36     .16       0
   60.45     .03       0
Bank Sta=0,112.91
XS Rating Curve= 0 ,0
Exp/Cntr=0.3,0.1

Type RM Length L Ch R = 1 ,354.3821,51,53.5,59.55
XS GIS Cut Line= 4
     320669.8785    4050182.6929     320675.1223    4050185.9925
     320721.0462    4050204.1692     320775.9194    4050225.8882
#Sta/Elev= 30
       0   351.5     3.1   351.6     6.2  351.52    8.14   350.8   10.15  349.78
    14.1  348.35   16.07  348.03   18.05  347.98   41.76  348.06   45.71  349.53
   46.75  349.69   47.68  349.84   51.63  349.86   55.59   350.3   57.55  350.87
   61.49  352.89   63.45  353.62   65.18  353.78   69.36  353.79   77.22  354.18
   85.09  355.01   89.03  355.52   92.96   356.1   94.93  356.62   98.39  358.12
  100.83   359.5   102.8  360.36  110.67  360.84  112.63  361.26   114.6  361.87
#Mann= 5 ,-1 , 0
       0     .12       0    8.14    .049       0   46.75     .16       0
   65.18     .03       0   98.39     .16       0
Bank Sta=0,114.6
XS Rating Curve= 0 ,0
Exp/Cntr=0.3,0.1

Type RM Length L Ch R = 1 ,300.8806,51.73,53.35,56.02
XS GIS Cut Line= 3
     320646.1206     4050227.881     320690.8836    4050252.8527
     320721.8501    4050270.1278
#Sta/Elev= 29
       0  350.88    1.97   350.9    3.58  350.53    3.94  350.44    5.91  349.62
    9.86   348.5   11.83  347.84    13.8  347.72   39.43  347.83    41.4  348.86
   43.37  349.52    45.7  350.12   47.31  350.49   51.26  351.14    55.2  352.91
   57.17   353.4   59.14  353.71   61.11  353.91   63.08  353.97   65.05  354.26
   67.02  354.99   68.99  355.87   70.96  356.89   72.93  357.52   78.84  357.71
   80.81   358.5   82.78  360.22   84.75  362.13   86.72  363.66
#Mann= 3 ,-1 , 0
       0     .12       0    3.58    .049       0    45.7     .16       0
Bank Sta=0,86.72
XS Rating Curve= 0 ,0
Exp/Cntr=0.3,0.1

Type RM Length L Ch R = 1 ,247.5266,50.9,51.14,53.63
XS GIS Cut Line= 2
      320617.721    4050271.0724      320678.652    4050310.4615
#Sta/Elev= 27
       0  352.25    3.91  352.28    5.88   351.4    6.43  351.06     9.8   348.9
   11.77   347.8   13.73  347.45   33.34  347.51    35.3  348.08   37.26   348.8
    38.4  348.92   39.22     349   41.18  350.11   43.14  350.81   47.06  350.51
   49.02  350.52   50.98  350.74   52.94  351.15   55.11  351.73   56.87   352.4
   58.83  353.53   60.79  354.96   62.75  355.39   66.67  355.67   68.63  356.71
   70.59  358.56   72.55  359.65
#Mann= 3 ,-1 , 0
       0     .12       0    6.43    .049       0    38.4     .16       0
Bank Sta=3.91,55.11
XS Rating Curve= 0 ,0
Exp/Cntr=0.3,0.1

Type RM Length L Ch R = 1 ,196.3842,49.6,56.81,67.88
XS GIS Cut Line= 3
     320585.5492    4050310.7311     320592.1555    4050314.7802
     320638.8935    4050346.7788
#Sta/Elev= 24
       0   352.3    5.81  352.42    6.96  352.17    7.75  352.01   11.65  348.89
   12.35  348.71   13.61  348.38   17.51  347.63   19.47  347.36   35.09  347.38
      39   348.1   40.73   348.5   40.95  348.55   42.91  349.68   44.86  350.23
   46.81  350.63   48.98  351.65   52.67  353.69   54.62  355.24   56.58  357.11
   58.53  358.57   60.48  359.01   62.44  359.11   64.39  359.59
#Mann= 3 ,-1 , 0
       0     .12       0   12.35    .049       0   40.73     .16       0
Bank Sta=6.96,48.98
XS Rating Curve= 0 ,0
Exp/Cntr=0.3,0.1

Type RM Length L Ch R = 1 ,139.5775,52.8,54.45,53.47
XS GIS Cut Line= 3
     320546.7671    4050341.6357     320558.0778    4050351.7635
     320585.5657    4050392.1313
#Sta/Elev= 30
       0  351.85      .1  351.84     1.9   351.6     3.8  351.12    5.69   350.9
    9.49  350.98   11.39  351.11   13.28  350.97   15.18  349.64    15.4  349.55
   17.14  348.86   19.09  348.41   21.04  347.38      23  347.21   32.76  347.19
   38.62  347.19   40.58  347.67   42.53  348.52   44.49  349.21    45.6  349.93
   46.44  350.47   47.74  351.48   48.39  351.98   50.35  353.26    52.3  354.87
   54.25  355.93   58.16  356.81   60.11  357.33   62.07  357.44   64.02   357.7
#Mann= 3 ,-1 , 0
       0     .12       0    15.4    .049       0    45.6     .16       0
Bank Sta=0.1,47.74
XS Rating Curve= 0 ,0
Exp/Cntr=0.3,0.1

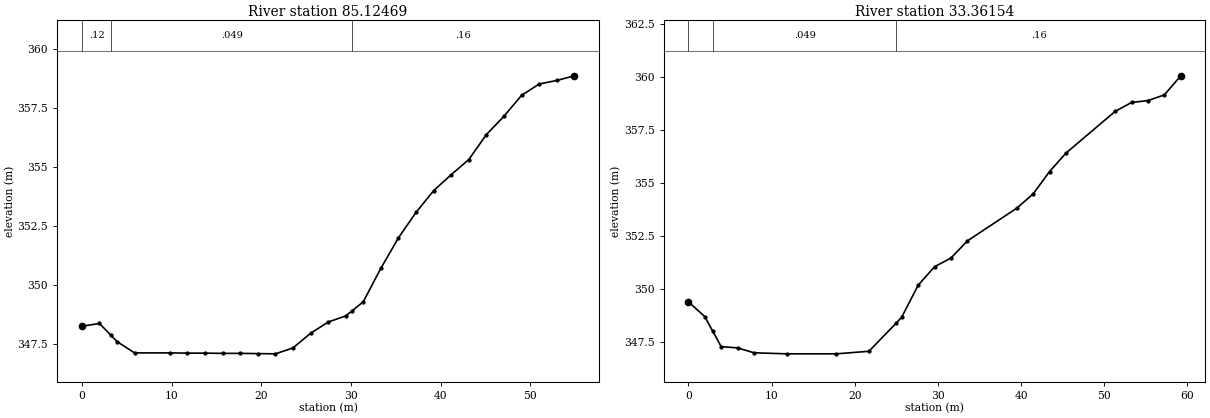
Type RM Length L Ch R = 1 ,85.12469,51.7,51.76,51.42
XS GIS Cut Line= 2
      320511.251    4050380.7478     320543.7404    4050425.0261
#Sta/Elev= 30
       0  348.24    1.96  348.36    3.27  347.85    3.92  347.59    5.88  347.11
    9.81  347.11   11.77   347.1   13.73   347.1   15.69  347.09   17.65  347.09
   19.61  347.08   21.58  347.07   23.54  347.32    25.5  347.94   27.46  348.42
   29.42  348.68   30.18  348.91   31.38  349.28   33.34   350.7   35.31     352
   37.27  353.08   39.23     354   41.19  354.68   43.15  355.32   45.11  356.38
   47.07  357.16   49.04  358.05      51  358.53   52.96  358.68   54.92  358.88
#Mann= 3 ,-1 , 0
       0     .12       0    3.27    .049       0   30.18     .16       0
Bank Sta=0,54.92
XS Rating Curve= 0 ,0
Exp/Cntr=0.3,0.1

Type RM Length L Ch R = 1 ,33.36154,26.26,33.36,18.47
XS GIS Cut Line= 2
     320469.9539    4050411.9048     320505.4319    4050459.3002
#Sta/Elev= 24
       0  349.39    1.97  348.69    2.95  347.99    3.95  347.27    5.92  347.21
    7.89  346.98   11.84  346.93   17.76  346.93   21.71  347.05   24.99  348.38
   25.65  348.66   27.63  350.17    29.6  351.04   31.57  351.45   33.55  352.26
   39.47   353.8   41.44  354.47   43.42  355.53   45.39   356.4   51.31  358.37
   53.28  358.79   55.26  358.88   57.23  359.15    59.2  360.05
#Mann= 3 ,-1 , 0
       0     .12       0    2.95    .049       0   24.99     .16       0
Bank Sta=0,59.2
XS Rating Curve= 0 ,0
Exp/Cntr=0.3,0.1

River Reach=Clinch River    ,Main Stem

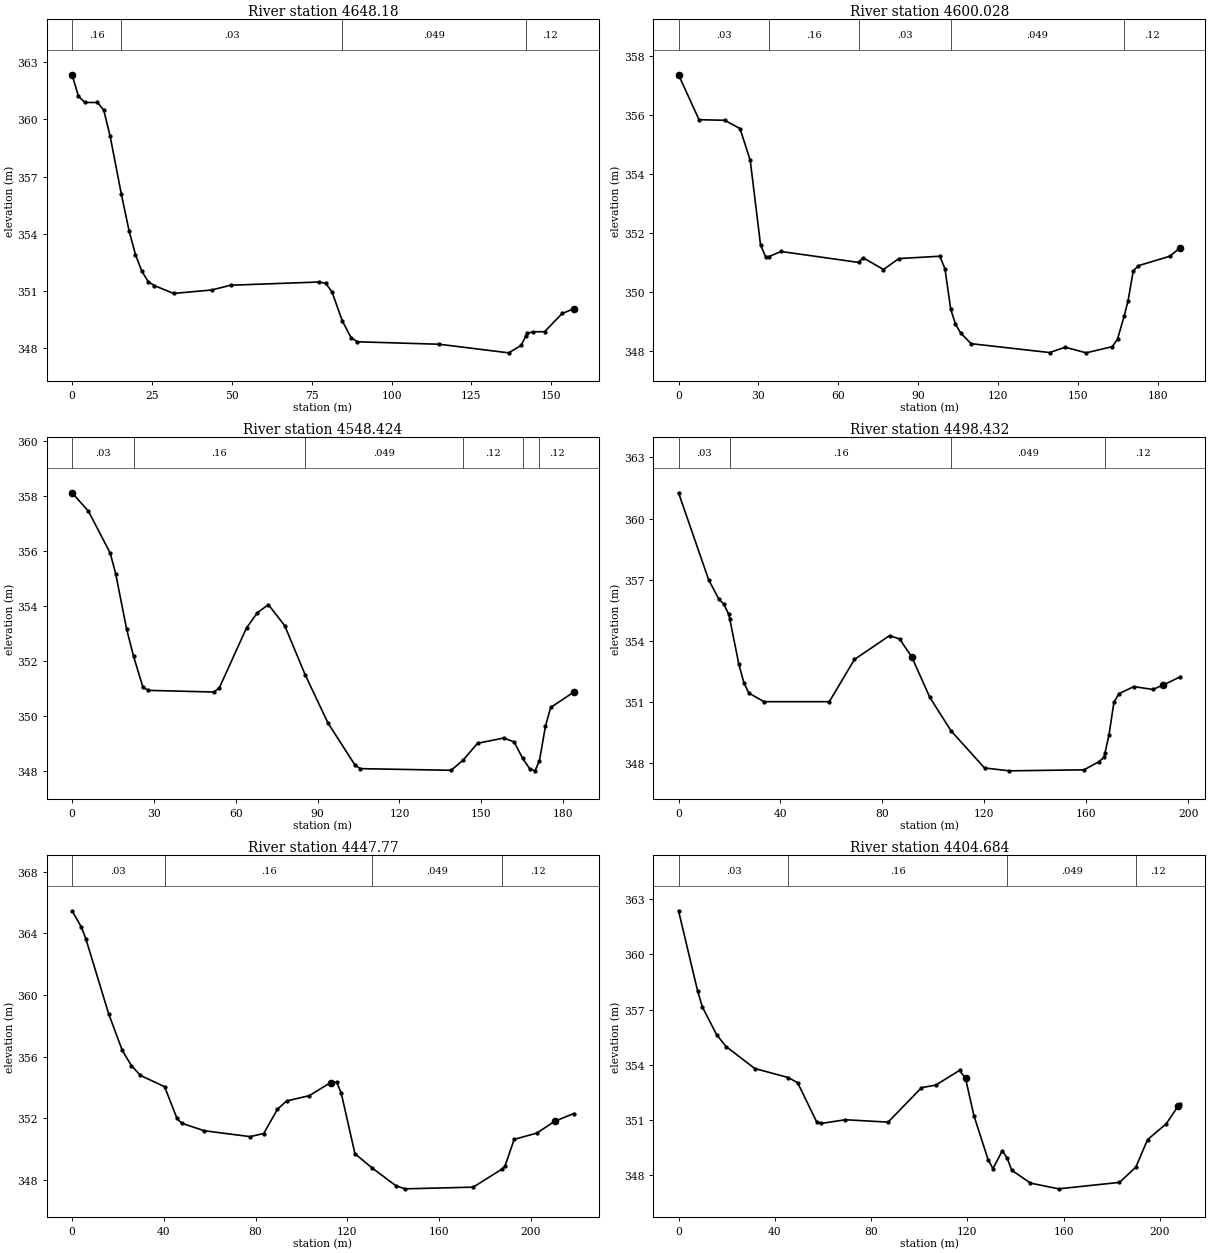
Type RM Length L Ch R = 1 ,4648.18 ,60,48.15,50.34
XS GIS Cut Line= 4
     320554.2473    4050058.6163      320629.645     4050102.679
      320675.632    4050129.5539     320690.4575    4050136.7511
#Sta/Elev= 30
       0  362.33    1.98  361.21    3.97  360.88    7.94  360.88    9.92  360.48
   11.91  359.12   15.42  356.08   17.86  354.15   19.85  352.91   21.83  352.05
   23.82   351.5    25.8  351.29   31.76  350.88   43.66  351.06   49.62  351.31
   77.41  351.48   79.39  351.41   81.37  350.96   84.59  349.44   87.33  348.57
    89.3  348.35  114.95  348.22  136.65  347.77  140.59  348.16  141.97  348.63
  142.42  348.79  144.26  348.87  147.92  348.88  153.41  349.83  157.07  350.08
#Mann= 4 ,-1 , 0
       0     .16       0   15.42     .03       0   84.59    .049       0
  141.97     .12       0
Bank Sta=0,157.07
XS Rating Curve= 0 ,0
Exp/Cntr=0.3,0.1

Type RM Length L Ch R = 1 ,4600.028,35.94,51.6,51
XS GIS Cut Line= 4
     320500.7236    4050105.8024     320545.7491    4050127.5448
     320595.1043     4050135.642     320669.8785    4050182.6929
#Sta/Elev= 30
       0  357.35    7.69  355.83   17.31  355.81   23.08  355.53   26.92  354.45
   30.77   351.6   32.69  351.19   34.01   351.2   38.46  351.37    67.6     351
   69.24  351.16   76.93  350.76    82.7  351.13   98.09  351.21  100.02  350.78
  102.18  349.41  103.94  348.92   105.9  348.61  109.83  348.25  139.28  347.95
  145.17  348.13  153.02  347.94  162.84  348.15   164.8  348.41  167.27  349.18
  168.73   349.7  170.69  350.71  172.65  350.89  184.43  351.21  188.36   351.5
#Mann= 5 ,-1 , 0
       0     .03       0   34.01     .16       0    67.6     .03       0
  102.18    .049       0  167.27     .12       0
Bank Sta=0,188.36
XS Rating Curve= 0 ,0
Exp/Cntr=0.3,0.1

Type RM Length L Ch R = 1 ,4548.424,48.23,49.99,51.73
XS GIS Cut Line= 5
     320492.4164    4050126.9221     320565.4709    4050175.8588
     320611.1192     4050206.437     320643.7081    4050226.5351
     320646.1108    4050227.8755
#Sta/Elev= 30
       0  358.11       6  357.44   13.99  355.92   15.99  355.17   19.98  353.17
   22.55  352.17   25.98  351.05   27.98  350.94   51.96  350.88   53.96  351.03
   63.95  353.21   67.95  353.76   71.94  354.05   77.94  353.29   85.46   351.5
   93.82  349.75  103.63  348.24  105.59   348.1  138.95  348.04  143.33  348.41
  148.62  349.02  158.19  349.21  162.02  349.07  165.11  348.48  167.76  348.09
  169.68  348.02   171.3  348.39   173.5  349.64  175.42  350.32  183.91  350.88
#Mann= 6 ,-1 , 0
       0     .03       0   22.55     .16       0   85.46    .049       0
  143.33     .12       0  165.11    .049       0   171.3     .12       0
Bank Sta=0,183.91
XS Rating Curve= 0 ,0
Exp/Cntr=0.3,0.1

Type RM Length L Ch R = 1 ,4498.432,50.94,50.66,50.9
XS GIS Cut Line= 5
     320456.1551    4050158.6168       320536.79    4050215.3347
     320602.2454    4050261.3754     320616.4107    4050270.2253
     320617.7136    4050271.0676
#Sta/Elev= 30
       0  361.27   11.83     357   15.77  356.07   17.75  355.81   19.72  355.31
   20.13  355.06   23.66  352.87   25.63  351.96    27.6  351.45   33.52  351.03
   59.15  351.03   69.01   353.1   82.81  354.27   86.75   354.1   91.52  353.22
   98.58  351.24  106.91   349.6  120.05  347.78  129.81  347.64  159.09  347.69
  164.95  348.09   166.9   348.3  167.32  348.53  168.85  349.38   170.8  350.99
  172.75  351.42  178.61  351.77  186.03  351.63  190.24  351.85  196.86  352.25
#Mann= 4 ,-1 , 0
       0     .03       0   20.13     .16       0  106.91    .049       0
  167.32     .12       0
Bank Sta=91.52,190.24
XS Rating Curve= 0 ,0
Exp/Cntr=0.3,0.1

Type RM Length L Ch R = 1 ,4447.77 ,39.28,43.09,49.6
XS GIS Cut Line= 4
     320406.1333    4050185.6172     320510.3316    4050258.7264
     320576.8649    4050305.4085     320585.5429    4050310.7273
#Sta/Elev= 30
       0  365.46    3.98  364.42    5.97  363.66   15.91  358.79   21.88   356.4
   25.86  355.41   29.83  354.77   40.34  354.04   45.74  351.98   47.73  351.67
   57.68  351.18   77.57   350.8   83.53     351    89.5  352.57   93.48  353.11
  103.42  353.46  112.75  354.31  115.35  354.33  117.34  353.62  123.31  349.69
  130.94  348.75  141.16  347.61  145.13  347.41  174.86  347.52  187.63  348.71
  188.74  348.89  192.71  350.62  202.62  351.03  210.31  351.79  218.74   352.3
#Mann= 4 ,-1 , 0
       0     .03       0   40.34     .16       0  130.94    .049       0
  187.63     .12       0
Bank Sta=112.75,210.31
XS Rating Curve= 0 ,0
Exp/Cntr=0.3,0.1

Type RM Length L Ch R = 1 ,4404.684,35.13,47.4,52.8
XS GIS Cut Line= 4
     320384.6058    4050210.6092     320488.5035     4050293.043
      320523.576      4050320.87     320546.7602    4050341.6296
#Sta/Elev= 30
       0  362.36    7.92  358.01     9.9  357.14   15.84  355.63    19.8  354.99
   31.67   353.8   45.58  353.31   49.49  353.03   57.41   350.9   59.39  350.82
   69.28  351.02    87.1  350.89  100.96  352.76  106.89   352.9  116.79   353.7
  119.27  353.26  122.73  351.25  128.67  348.84  130.65  348.37  134.57  349.34
  136.57  348.93  138.47  348.28  146.25  347.58  157.93  347.27  183.23  347.62
  190.04  348.45   194.9  349.94  202.68   350.8  207.65  351.77  208.52  351.85
#Mann= 4 ,-1 , 0
       0     .03       0   45.58     .16       0  136.57    .049       0
  190.04     .12       0
Bank Sta=119.27,207.65
XS Rating Curve= 0 ,0
Exp/Cntr=0.3,0.1

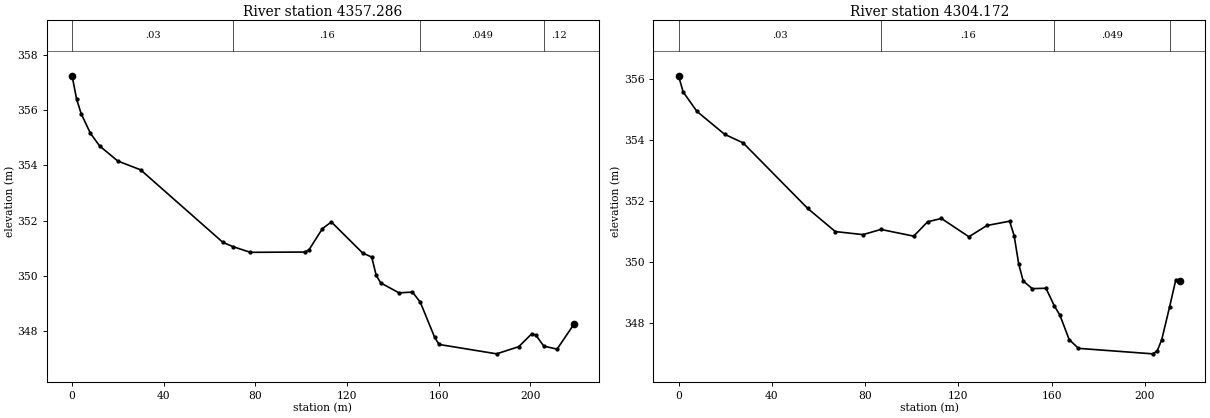
Type RM Length L Ch R = 1 ,4357.286,59.28,53.11,51.7
XS GIS Cut Line= 6
     320355.6307    4050235.7011     320420.0751    4050292.2872
     320462.8057    4050311.7008      320463.864     4050323.607
     320499.3183    4050364.4852      320511.251    4050380.7478
#Sta/Elev= 30
       0  357.25    1.99   356.4    3.99  355.87    7.98  355.17   11.97  354.71
   19.94  354.16   29.92  353.84   65.82  351.21   70.41  351.05   77.78  350.85
  101.41  350.86  103.36  350.94  109.23  351.71  113.14  351.95  126.83  350.82
  130.74  350.68   132.7  350.01  134.69  349.74  142.66  349.38  148.51  349.41
  151.94  349.04  158.18  347.77  160.11  347.51  185.23  347.17   194.9  347.43
  200.59   347.9  202.43  347.84  205.81  347.45   211.6  347.34  218.93  348.24
#Mann= 4 ,-1 , 0
       0     .03       0   70.41     .16       0  151.94    .049       0
  205.81     .12       0
Bank Sta=0,218.93
XS Rating Curve= 0 ,0
Exp/Cntr=0.3,0.1

Type RM Length L Ch R = 1 ,4304.172,19.2,24.8,26.26
XS GIS Cut Line= 4
     320343.5792    4050243.1492     320403.5441    4050347.8591
     320433.0418    4050362.5935     320469.9492    4050411.8985
#Sta/Elev= 30
       0  356.12    1.98  355.59    7.91  354.95   19.78   354.2   27.69  353.92
   55.39  351.77   67.26  351.01   79.12  350.91   86.81  351.08  100.88  350.86
  106.82  351.33  112.75  351.44  124.54  350.84   132.3  351.21     142  351.35
  143.94  350.88  145.88  349.96  147.82  349.39   151.7  349.14  157.61  349.15
  161.21  348.57  163.57  348.27  167.54  347.47  171.52  347.18  203.31     347
  205.29  347.09  207.28  347.47  210.59  348.53  213.24  349.41  215.23  349.39
#Mann= 4 ,-1 , 0
       0     .03       0   86.81     .16       0  161.21    .049       0
  210.59     .12       0
Bank Sta=0,215.23
XS Rating Curve= 0 ,0
Exp/Cntr=0.3,0.1

River Reach=Clinch River    ,Middle Reach

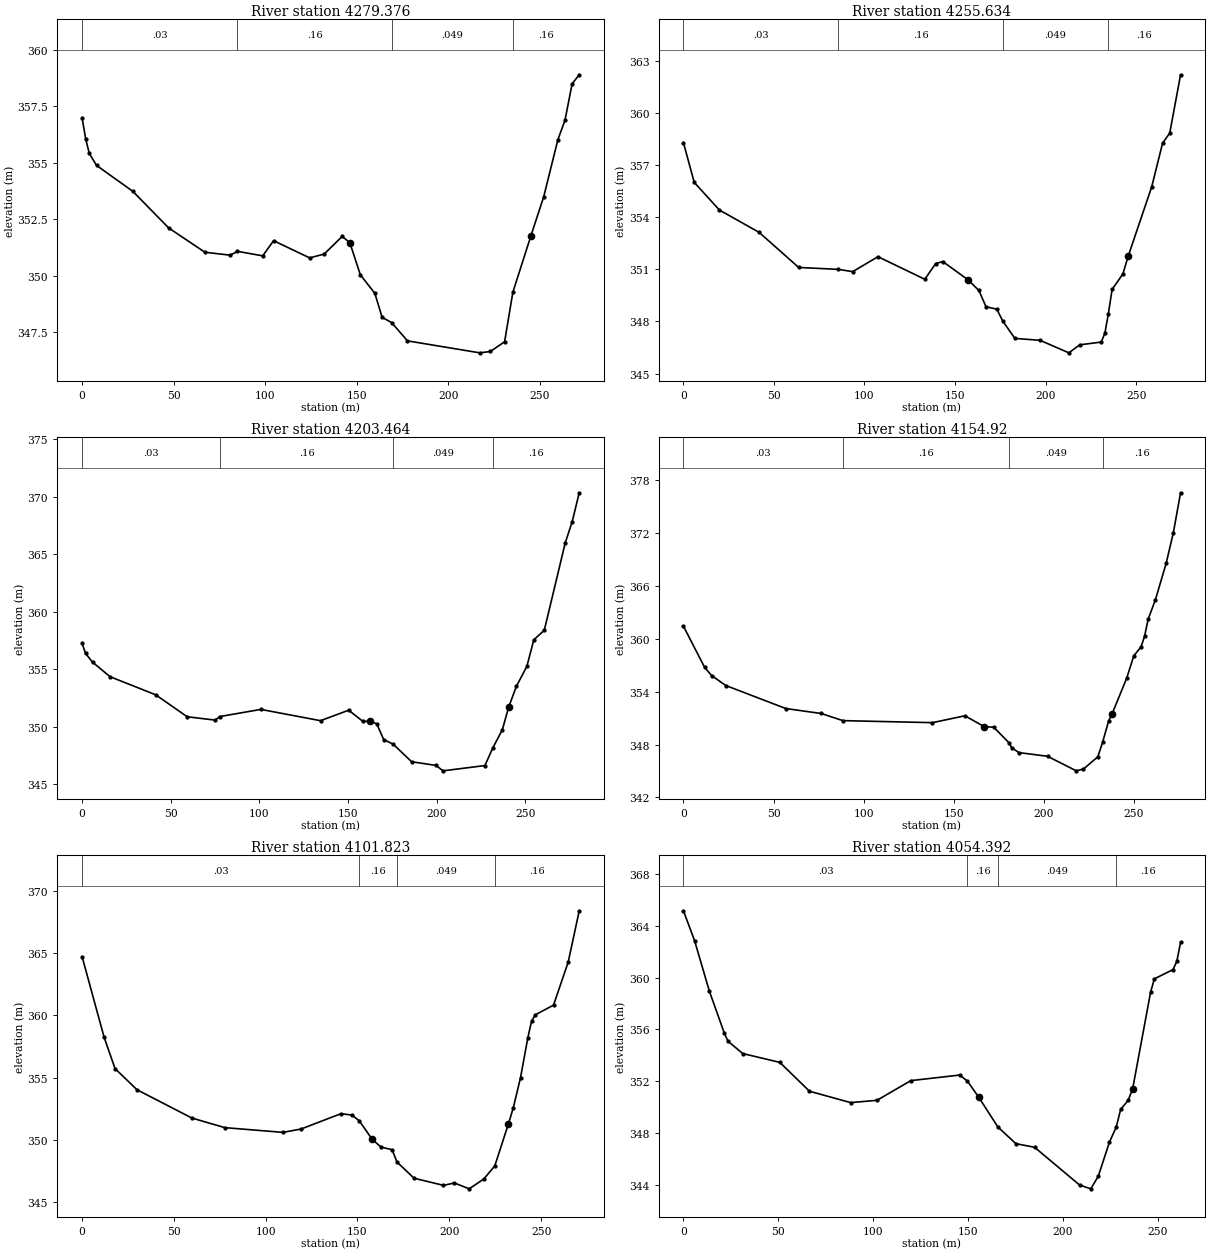
Type RM Length L Ch R = 1 ,4279.376,15.66,23.74,27.2
XS GIS Cut Line= 5
     320336.6232    4050248.0636     320401.4124    4050372.2086
     320416.4359    4050385.1111     320449.7769    4050424.2814
     320488.7458    4050470.0636
#Sta/Elev= 30
       0  356.99    1.97  356.05    3.94  355.41    7.89  354.88   27.61  353.74
   47.34  352.11   67.06  351.04   80.86  350.91   84.83  351.08   98.62  350.88
  104.53  351.55  124.26  350.79  132.15  350.96  142.01  351.74  146.19  351.46
  151.92  350.04  159.84  349.22  163.79  348.16  168.97  347.93  177.64  347.12
  217.09  346.59  222.91  346.65  230.67  347.08  235.17  349.27     245  351.76
     252  353.49  259.76  356.02  263.64  356.88  267.52  358.49   271.4  358.89
#Mann= 4 ,-1 , 0
       0     .03       0   84.83     .16       0  168.97    .049       0
  235.17     .16       0
Bank Sta=146.19,245
XS Rating Curve= 0 ,0
Exp/Cntr=0.3,0.1

Type RM Length L Ch R = 1 ,4255.634,32.76,52.17,63.74
XS GIS Cut Line= 3
     320320.6015    4050254.5014     320395.9612    4050392.4355
     320465.8256    4050486.7638
#Sta/Elev= 30
       0  358.28    5.97  355.99    19.9   354.4   41.78  353.12   63.67   351.1
   85.52  350.99   93.51  350.86  107.44  351.72   133.3  350.42  139.27  351.32
  143.25  351.44  157.18  350.39  163.15  349.78  167.13  348.84  173.09   348.7
   176.3  348.03  183.04  347.02  196.97  346.91  212.89  346.19  218.85  346.65
  230.79  346.81  232.78  347.33  234.66  348.42  236.76  349.84  242.73  350.73
  245.61  351.74  258.64  355.74  264.61  358.24  268.59  358.83  274.56  362.18
#Mann= 4 ,-1 , 0
       0     .03       0   85.52     .16       0   176.3    .049       0
  234.66     .16       0
Bank Sta=157.18,245.61
XS Rating Curve= 0 ,0
Exp/Cntr=0.3,0.1

Type RM Length L Ch R = 1 ,4203.464,53.89,48.54,48.84
XS GIS Cut Line= 4
     320301.8165    4050271.3392     320362.7586    4050382.1803
     320361.0967    4050409.9472     320408.0969    4050526.8685
#Sta/Elev= 30
       0  357.25    1.98  356.37    5.93  355.61   15.81  354.35    41.5  352.78
   59.29  350.87    75.1  350.58   77.68  350.89   100.8  351.51  134.44  350.53
  150.33  351.44  158.24  350.48  162.53  350.46  166.12  350.27  170.06  348.89
   175.4  348.49  185.81  346.96  199.59  346.64  203.53  346.17  227.16  346.63
  231.52  348.14     237  349.75  240.49  351.69  244.88  353.51  250.79  355.25
  254.72  357.56  260.63  358.39  272.44  365.99  276.38  367.84  280.32  370.34
#Mann= 4 ,-1 , 0
       0     .03       0   77.68     .16       0   175.4    .049       0
  231.52     .16       0
Bank Sta=162.53,240.49
XS Rating Curve= 0 ,0
Exp/Cntr=0.3,0.1

Type RM Length L Ch R = 1 ,4154.92 ,50.74,53.1,52.8
XS GIS Cut Line= 4
     320248.3828    4050289.9528     320298.8335    4050369.3239
     320307.8783    4050406.4264     320360.5787     4050540.048
#Sta/Elev= 30
       0  361.41   11.76  356.75   15.67  355.81   23.51  354.69   56.82  352.08
   76.41  351.52   88.49  350.71  138.22  350.48  156.18  351.26  167.01  350.02
  172.14  349.97  180.68   348.2  182.11  347.66   186.1  347.09  202.06  346.67
  218.02  345.02  222.01  345.23  229.99  346.61  232.72  348.33  235.98  350.68
  237.93   351.5  245.95   355.5  249.94  358.06  253.93  359.05  255.93  360.29
  257.92  362.22  261.91   364.4   267.9  368.54  271.89  372.02  275.88  376.53
#Mann= 4 ,-1 , 0
       0     .03       0   88.49     .16       0  180.68    .049       0
  232.72     .16       0
Bank Sta=167.01,237.93
XS Rating Curve= 0 ,0
Exp/Cntr=0.3,0.1

Type RM Length L Ch R = 1 ,4101.823,48.48,47.43,47.43
XS GIS Cut Line= 4
     320210.8897    4050308.7956     320253.7623     4050376.048
      320266.836    4050447.9719      320310.819    4050557.3871
#Sta/Elev= 30
       0  364.71   11.96  358.26   17.94  355.73   29.91  354.03   59.82  351.76
   77.76  350.99  109.39  350.61  119.27  350.88     141  352.11  146.93     352
  150.99  351.54  158.01  350.05  162.85  349.43  168.85  349.22  171.53  348.23
  180.84  346.93  196.83  346.36  202.83  346.55  210.82  346.08  218.82  346.87
  224.79  347.92  232.26  351.31  234.81  352.55   238.8  354.99   242.8  358.21
   244.8  359.52   246.8  360.04  256.79  360.82  264.79  364.28  270.78  368.39
#Mann= 4 ,-1 , 0
       0     .03       0  150.99     .16       0  171.53    .049       0
  224.79     .16       0
Bank Sta=158.01,232.26
XS Rating Curve= 0 ,0
Exp/Cntr=0.3,0.1

Type RM Length L Ch R = 1 ,4054.392,50.43,51.39,53.8
XS GIS Cut Line= 4
     320166.8993    4050326.5308     320202.6957    4050387.0594
     320222.8456    4050465.7071     320264.0367    4050568.1773
#Sta/Elev= 30
       0  365.17    5.86  362.87   13.67  358.96   21.49  355.74   23.44   355.1
   31.25  354.14   50.79  353.46   66.41  351.23   88.14  350.35     102  350.53
  119.83  352.05  145.57  352.48  149.65  352.01  155.59  350.77  165.68  348.47
  175.17  347.18  185.04   346.9   208.7  343.99  214.62  343.69  218.56  344.65
  224.48   347.3  228.06  348.46  230.39  349.83  234.34  350.52   236.7  351.41
  246.17  358.89  248.14  359.91     258  360.63  259.98  361.27  261.95  362.72
#Mann= 4 ,-1 , 0
       0     .03       0  149.65     .16       0  165.68    .049       0
  228.06     .16       0
Bank Sta=155.59,236.7
XS Rating Curve= 0 ,0
Exp/Cntr=0.3,0.1