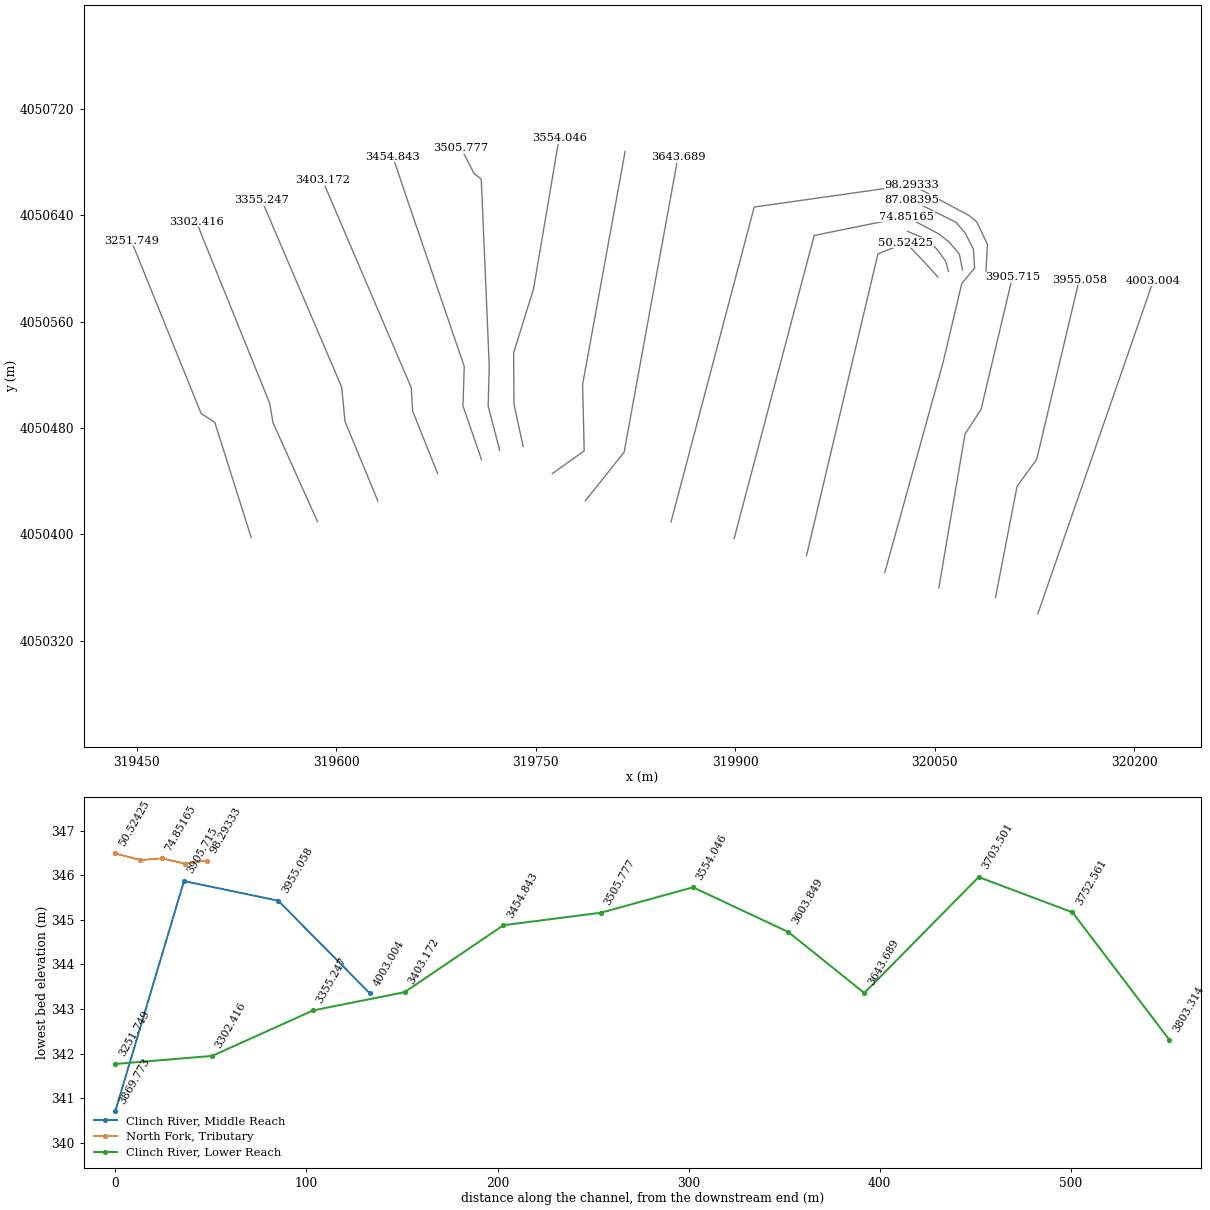
HEC-RAS study WBmod1D.prj: WBmod1D

--- WBmod1D.g09 (geometry) --- (continued)

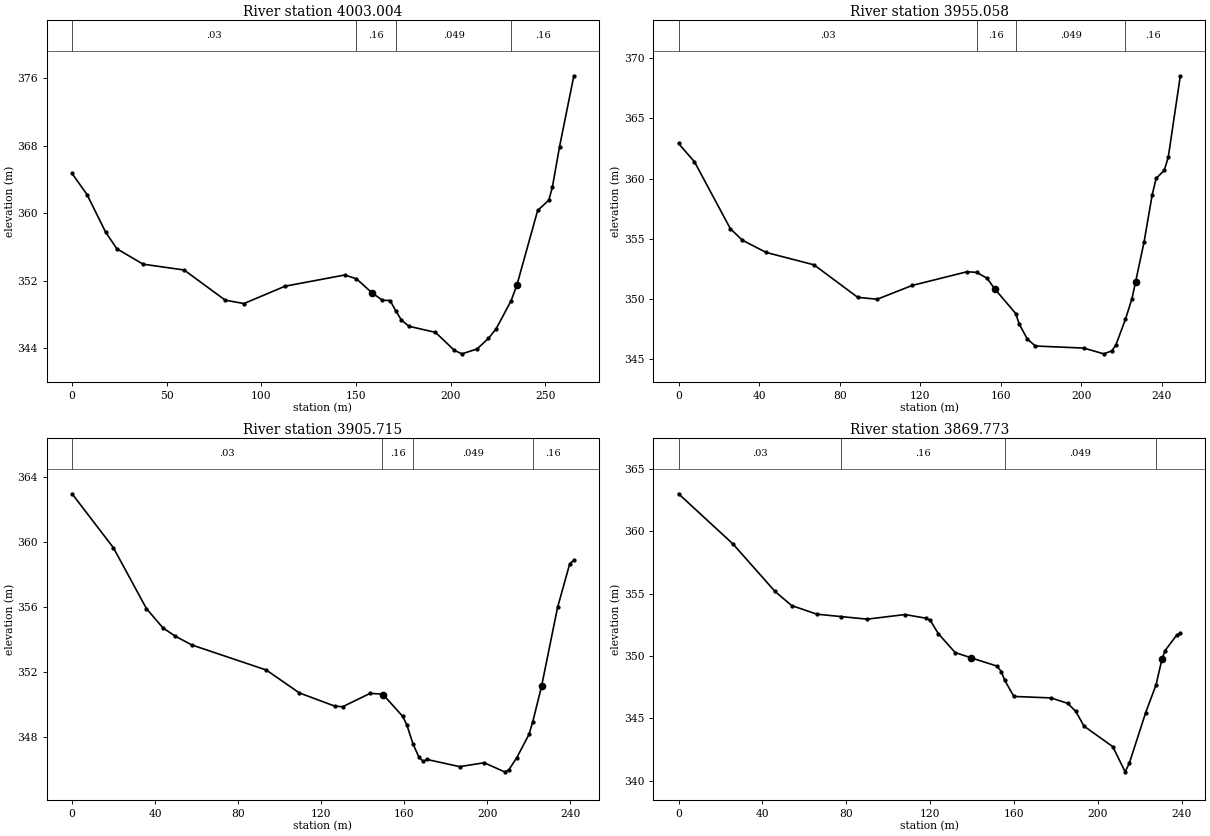
Type RM Length L Ch R = 1 ,4003.004,42.97,47.95,52
XS GIS Cut Line= 4
     320127.5561     4050340.332     320176.6961    4050482.0545
     320209.4561    4050576.5361     320214.4091    4050590.8209
#Sta/Elev= 30
       0  364.69    7.89   362.2   17.76  357.74   23.68  355.78    37.5  353.96
   59.21  353.27   80.92   349.7   90.79   349.3   112.5  351.35  144.08  352.68
  150.24  352.23  158.41  350.58     164  349.69     168  349.66  171.24  348.36
     174  347.35     178  346.61     192  345.89     202  343.76     206  343.35
     214  343.93     220  345.18     224  346.29  231.98  349.64  235.08  351.53
     246  360.32  251.89  361.53  253.78  363.08  257.56  367.87  265.12  376.25
#Mann= 4 ,-1 , 0
       0     .03       0  150.24     .16       0  171.24    .049       0
  231.98     .16       0
Bank Sta=158.41,235.08
XS Rating Curve= 0 ,0
Exp/Cntr=0.3,0.1

Type RM Length L Ch R = 1 ,3955.058,50.75,49.34,49.49
XS GIS Cut Line= 5
     320095.7166    4050352.4919     320111.8844    4050436.0227
      320126.686    4050456.3993     320135.6451    4050494.2464
     320158.6805     4050591.557
#Sta/Elev= 30
       0  362.92    7.91   361.4   25.72  355.84   31.66  354.88   43.53  353.86
   67.27  352.83   88.96  350.13   98.64  349.97   116.1  351.12  143.33  352.26
  148.04   352.2  153.16  351.72  157.06  350.82  167.43  348.78  169.16  347.91
  173.16  346.67  177.16  346.08  201.16  345.91  211.16  345.43  215.16  345.68
  217.16  346.17  221.89  348.29  225.16  350.03  226.94  351.41  231.16  354.73
  235.16  358.63  237.16  360.02  241.16  360.68  243.16  361.77  249.16  368.55
#Mann= 4 ,-1 , 0
       0     .03       0  148.04     .16       0  167.43    .049       0
  221.89     .16       0
Bank Sta=157.06,226.94
XS Rating Curve= 0 ,0
Exp/Cntr=0.3,0.1

Type RM Length L Ch R = 1 ,3905.715,37.46,35.94,32.79
XS GIS Cut Line= 4
     320053.0693    4050359.6191     320072.7926    4050475.3878
     320084.8748    4050493.9783     320108.3964     4050593.343
#Sta/Elev= 30
       0  362.99    19.9  359.67   35.83  355.92   43.79  354.73   49.76  354.22
   57.72  353.68   93.55  352.14  109.47  350.73  126.67  349.91  130.37  349.88
  143.54   350.7   149.3  350.66   149.8  350.63  159.25  349.29  161.21  348.78
  164.26  347.58   167.1  346.77  169.06  346.52  171.03  346.63  186.74  346.19
  198.52  346.43  208.34  345.87   210.3  345.98  214.23  346.74  220.12  348.18
   221.9  348.94  226.18  351.15  233.86  355.99  239.76  358.69  241.72   358.9
#Mann= 4 ,-1 , 0
       0     .03       0   149.3     .16       0  164.26    .049       0
   221.9     .16       0
Bank Sta=149.8,226.18
XS Rating Curve= 0 ,0
Exp/Cntr=0.3,0.1

Type RM Length L Ch R = 1 ,3869.773,65,66.46,14.16
XS GIS Cut Line= 4
      320012.478    4050371.3182     320056.2836    4050529.2275
     320070.2988    4050588.4335     320079.5228    4050599.6658
#Sta/Elev= 30
       0  363.02   25.98  358.99   45.96  355.19   53.96  354.05   65.95  353.36
   77.29  353.17   89.93  352.96  107.92  353.33  117.91  353.04  119.91  352.89
   123.9  351.79   131.9  350.28  139.48  349.86  151.88  349.19  153.88  348.76
   155.5  348.06  159.88  346.76  177.61  346.64  185.46  346.21  189.39  345.57
  193.31  344.38  207.05  342.73  212.94  340.71   214.9  341.39  222.75  345.47
  227.67  347.69   230.5  349.75  231.98  350.44  237.43  351.66  239.25  351.83
#Mann= 4 ,-1 , 0
       0     .03       0   77.29     .16       0   155.5    .049       0
  227.67     .16       0
Bank Sta=139.48,230.5
XS Rating Curve= 0 ,0
Exp/Cntr=0.3,0.1

River Reach=North Fork      ,Tributary

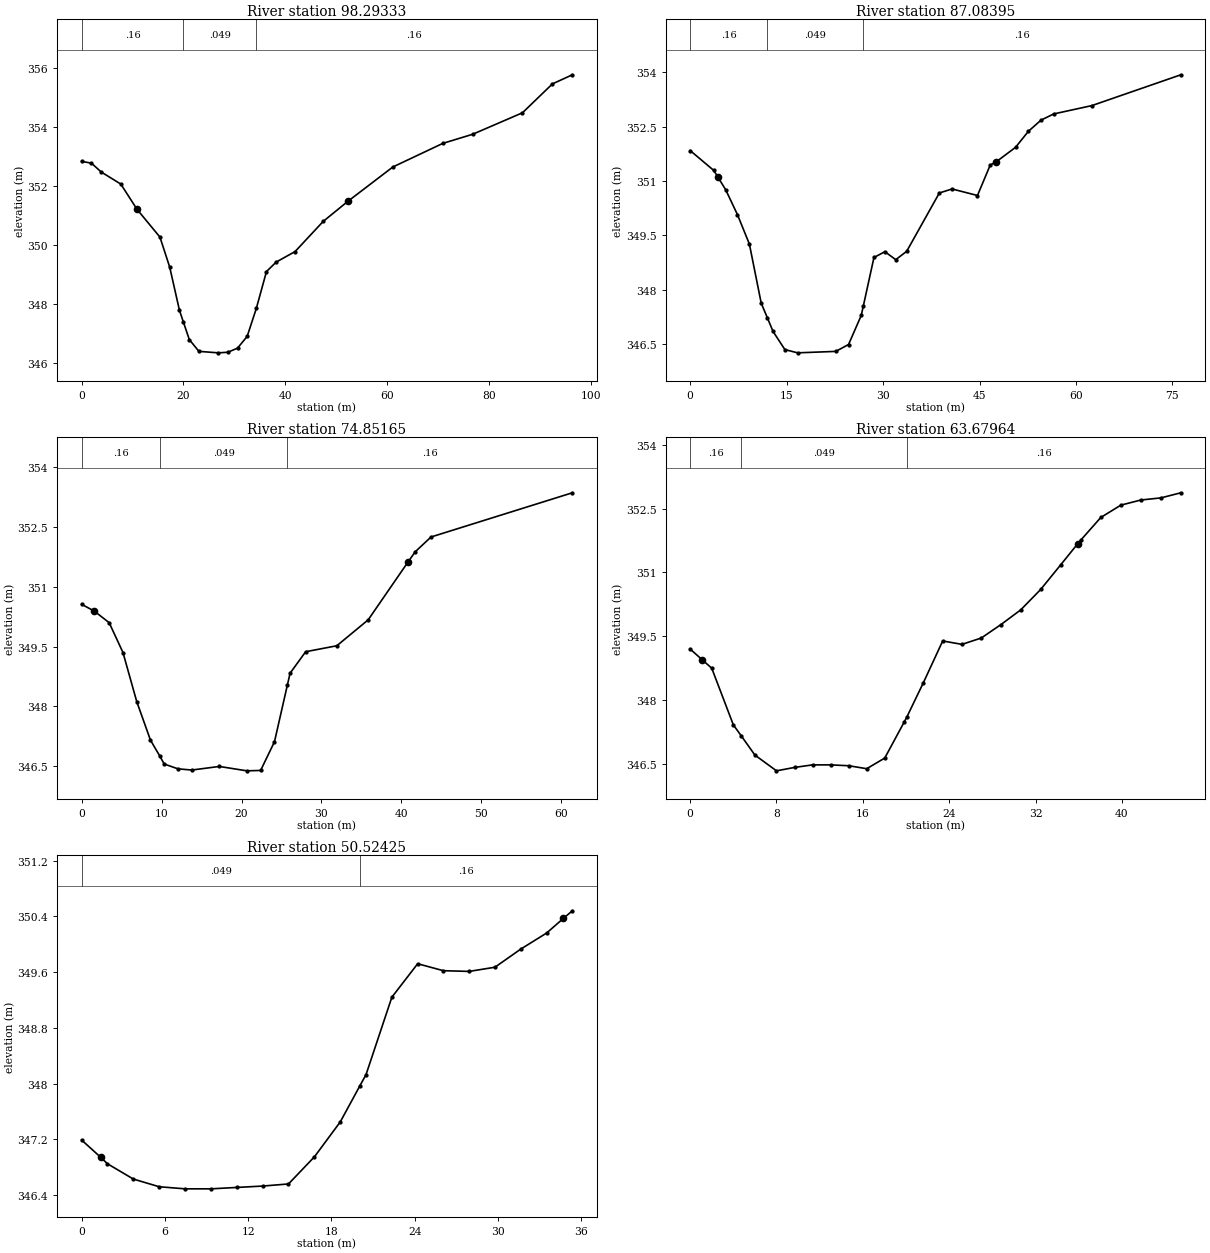
Type RM Length L Ch R = 1 ,98.29333,10.02,11.21,14.23
XS GIS Cut Line= 5
     320088.4987    4050596.8002     320089.6548    4050617.9138
     320081.5393    4050635.0498     320075.8435    4050639.6626
     320032.7105    4050662.8283
#Sta/Elev= 27
       0  352.83    1.92  352.77    3.84  352.47    7.69  352.06   10.89   351.2
   15.38  350.26    17.3  349.24   19.22  347.77   19.96  347.39   21.15  346.78
   23.04  346.38   26.83  346.33   28.73  346.35   30.63  346.49   32.52  346.89
   34.32  347.84   36.31  349.09   38.21  349.41   41.94  349.77   47.44  350.79
   52.27  351.47   61.14  352.64   70.94  353.44   76.81  353.75    86.6  354.48
   92.48  355.46    96.4  355.77
#Mann= 3 ,-1 , 0
       0     .16       0   19.96    .049       0   34.32     .16       0
Bank Sta=10.89,52.27
XS Rating Curve= 0 ,0
Exp/Cntr=0.3,0.1

Type RM Length L Ch R = 1 ,87.08395,9.71,12.23,14.68
XS GIS Cut Line= 5
     320080.0055    4050599.8958     320079.0598    4050614.5937
     320072.6152    4050626.8593      320066.001    4050634.5826
     320032.3946     4050651.348
#Sta/Elev= 30
       0  351.84    3.68  351.29    4.27  351.12    5.52  350.76    7.36  350.07
    9.21  349.26   11.05  347.63   12.02  347.22   12.89  346.85   14.73  346.35
   16.71  346.26   22.65   346.3   24.63  346.49    26.6  347.29   26.94  347.56
   28.58  348.89   30.28  349.05   31.97  348.83   33.67  349.06   38.75  350.67
   40.73  350.78   44.68   350.6   46.66  351.44    47.6  351.53   50.61  351.93
   52.59  352.37   54.57  352.68   56.54  352.85   62.47  353.08   76.31  353.93
#Mann= 3 ,-1 , 0
       0     .16       0   12.02    .049       0   26.94     .16       0
Bank Sta=4.27,47.6
XS Rating Curve= 0 ,0
Exp/Cntr=0.3,0.1

Type RM Length L Ch R = 1 ,74.85165,10.7,11.17,9.52
XS GIS Cut Line= 5
     320070.9412    4050598.7874     320068.5241    4050610.5976
     320060.7536    4050619.8212     320053.0692    4050625.8412
     320028.7965    4050638.7647
#Sta/Elev= 23
       0  350.56    1.58  350.39    3.44   350.1    5.17  349.35    6.89  348.12
    8.61  347.15    9.78  346.75   10.33  346.55   12.06  346.43   13.78   346.4
   17.22  346.49   20.67  346.38   22.39  346.39   24.12  347.11   25.73  348.53
   26.07  348.83   28.02  349.37   31.92  349.52   35.84  350.17   40.85  351.63
   41.73  351.88    43.7  352.25   61.38  353.36
#Mann= 3 ,-1 , 0
       0     .16       0    9.78    .049       0   25.73     .16       0
Bank Sta=1.58,40.85
XS Rating Curve= 0 ,0
Exp/Cntr=0.3,0.1

Type RM Length L Ch R = 1 ,63.67964,9.19,13.16,9.67
XS GIS Cut Line= 5
     320060.3787    4050597.6496     320058.2182    4050605.3508
       320052.38      4050613.51      320045.073    4050621.3843
     320029.6308    4050627.7458
#Sta/Elev= 30
       0   349.2    1.11  348.95       2  348.75       4  347.42    4.74  347.16
       6  346.71       8  346.34    9.67  346.42   11.34  346.48   13.01  346.48
   14.69  346.46   16.36  346.39   18.03  346.64   19.82  347.48   20.07   347.6
   21.61  348.41    23.4  349.39   25.19  349.31   26.98  349.46   28.77  349.77
   30.63  350.12   32.48   350.6   34.34  351.18    35.9  351.67    36.2  351.76
   38.05  352.29   39.91  352.58   41.76   352.7   43.62  352.75   45.47  352.87
#Mann= 3 ,-1 , 0
       0     .16       0    4.74    .049       0   20.07     .16       0
Bank Sta=1.11,35.9
XS Rating Curve= 0 ,0
Exp/Cntr=0.3,0.1

Type RM Length L Ch R = 1 ,50.52425,0.47,50.52,0.27
XS GIS Cut Line= 3
     320052.4888    4050593.3402      320039.956    4050607.1391
     320028.3079    4050619.1469
#Sta/Elev= 23
       0  347.19    1.39  346.94    1.86  346.85    3.73  346.63    5.59  346.52
    7.46  346.49    9.32  346.49   11.18  346.51   13.05  346.53   14.91  346.56
   16.78  346.95   18.64  347.45   20.06  347.97    20.5  348.13   22.36  349.24
   24.22  349.72   26.08  349.62   27.93  349.61   29.79  349.67   31.65  349.93
   33.51  350.16   34.72  350.37   35.37  350.48
#Mann= 2 ,-1 , 0
       0    .049       0   20.06     .16       0
Bank Sta=1.39,34.72
XS Rating Curve= 0 ,0
Exp/Cntr=0.3,0.1

River Reach=Clinch River    ,Lower Reach

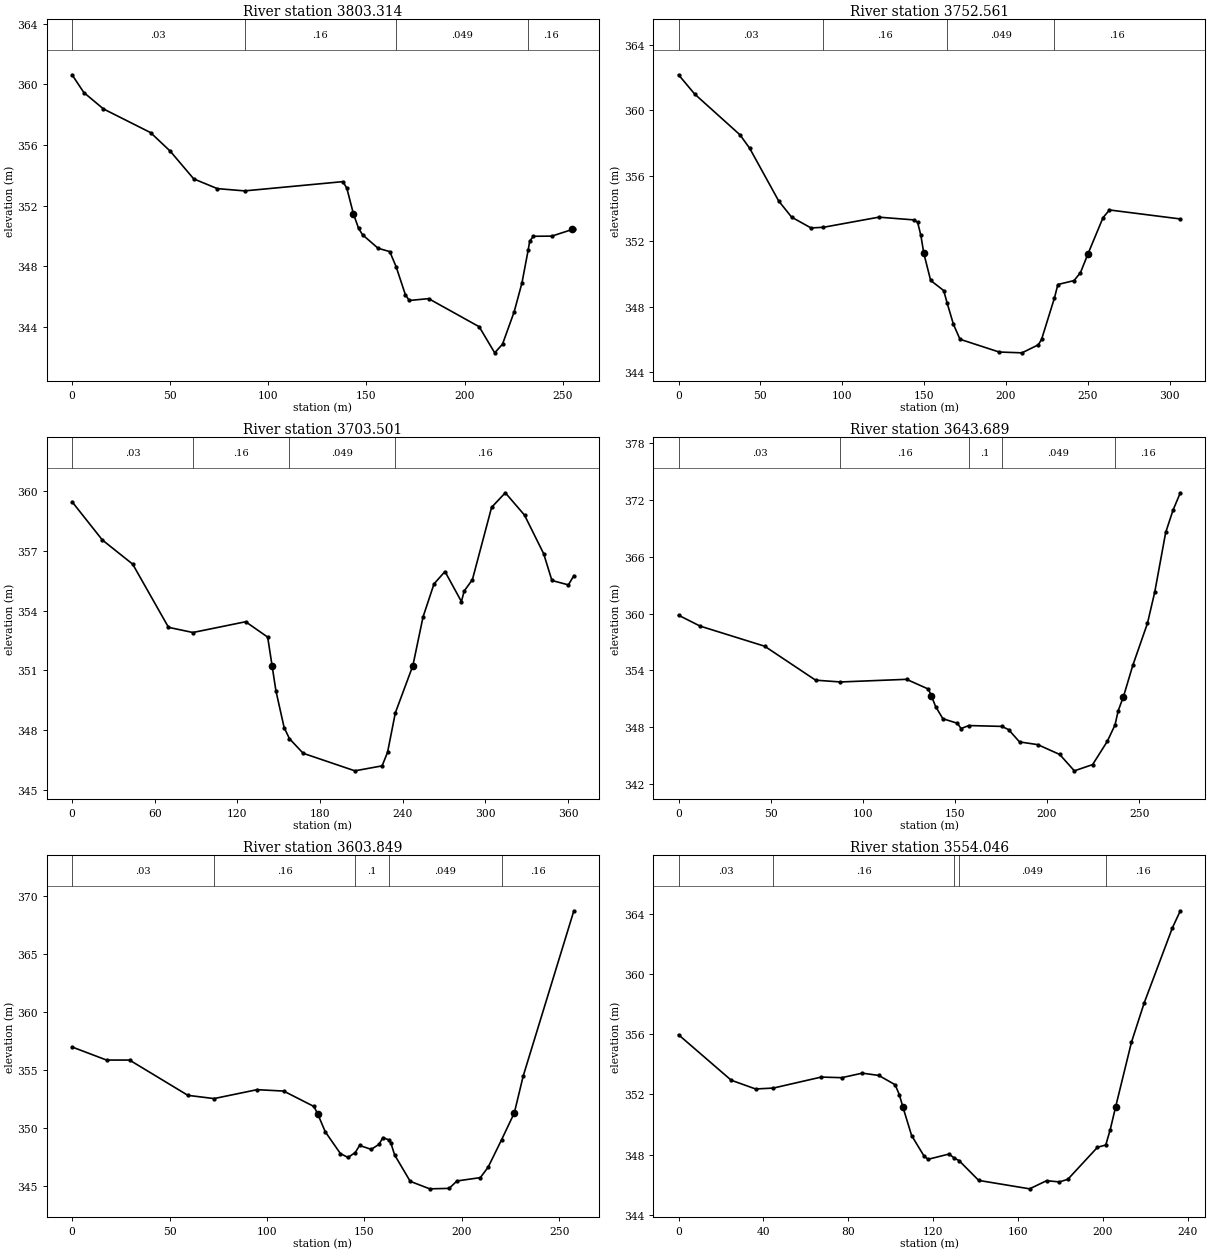
Type RM Length L Ch R = 1 ,3803.314,53.02,50.75,38.45
XS GIS Cut Line= 4
      319953.586     4050383.901     319988.1391     4050529.867
     320007.3026    4050610.8214     320028.1876    4050619.1885
#Sta/Elev= 30
       0  360.63       6  359.46      16  358.38      40  356.82      50   355.6
      62  353.77      74  353.13   87.91  352.98     138  353.59     140  353.16
  143.36  351.47     146  350.51     148  350.09  155.94   349.2  161.88  348.98
  165.11  347.99  169.81  346.15  171.79  345.76  181.69  345.88  207.44  344.03
  215.36  342.31  219.33  342.88  225.27  345.01  229.23  346.91  232.45  349.11
  233.19  349.67  235.07  349.99  244.44     350  254.94  350.44  255.69   350.5
#Mann= 4 ,-1 , 0
       0     .03       0   87.91     .16       0  165.11    .049       0
  232.45     .16       0
Bank Sta=143.36,254.94
XS Rating Curve= 0 ,0
Exp/Cntr=0.3,0.1

Type RM Length L Ch R = 1 ,3752.561,49.63,49.06,67.83
XS GIS Cut Line= 4
     319899.2076     4050396.827      319937.508    4050541.8549
      319959.387    4050624.7017     320028.7848    4050638.7674
#Sta/Elev= 30
       0  362.18    9.87     361    37.5  358.51   43.42  357.69   61.18  354.46
   69.08  353.47   80.92  352.81   88.45  352.85  122.37  353.47  144.08   353.3
  146.05  353.15  148.03  352.35  149.83  351.25  153.99   349.6  161.96  348.98
  164.03  348.23  167.93  346.91  171.92     346  195.83  345.22  209.78  345.17
  219.75  345.66  221.74  345.99  229.62  348.53   231.7  349.35  241.59  349.59
  245.52  350.08  250.15  351.24  259.29  353.44  263.22  353.91   306.5  353.36
#Mann= 4 ,-1 , 0
       0     .03       0   88.45     .16       0  164.03    .049       0
  229.62     .16       0
Bank Sta=149.83,250.15
XS Rating Curve= 0 ,0
Exp/Cntr=0.3,0.1

Type RM Length L Ch R = 1 ,3703.501,54.69,59.81,74.06
XS GIS Cut Line= 4
     319851.7715    4050409.3446     319890.0719    4050554.3724
     319914.2879    4050646.0686     320032.5468    4050662.8149
#Sta/Elev= 30
       0  359.46      22  357.54      44  356.33      70  353.16   87.71   352.9
     126  353.44     142  352.67  145.23  351.22     148  349.97  153.95  348.13
  157.84  347.57  167.78  346.84  205.32  345.96  225.08  346.21  229.03  346.89
  234.68  348.87  247.42  351.24  254.79  353.68  262.76  355.34  270.72  355.96
  282.66  354.45  284.65  354.98  290.62  355.55  304.56  359.18  314.51  359.91
  328.45  358.79  342.38  356.85  348.35  355.51   360.3  355.29  364.28  355.75
#Mann= 4 ,-1 , 0
       0     .03       0   87.71     .16       0  157.84    .049       0
  234.68     .16       0
Bank Sta=145.23,247.42
XS Rating Curve= 0 ,0
Exp/Cntr=0.3,0.1

Type RM Length L Ch R = 1 ,3643.689,39.95,39.84,39.84
XS GIS Cut Line= 4
     319787.2797    4050425.2006      319816.474    4050461.7289
     319835.9722    4050568.5346     319856.9908    4050683.6686
#Sta/Elev= 30
       0  359.82   11.69  358.67   46.76  356.54    74.4  352.95    87.9  352.76
  123.75  353.04  135.59  352.01  137.19  351.32  139.54  350.16  143.49  348.87
  151.38  348.39  153.36  347.83  157.54  348.15  175.49  348.06  179.14  347.72
  185.09  346.42  195.01  346.13  206.91  345.09  214.84  343.36  224.76  344.02
   232.7  346.47  236.92  348.21  238.65  349.72  241.52  351.22  246.58  354.52
  254.52  358.96  258.48  362.26  264.43  368.58   268.4  370.93  272.37  372.77
#Mann= 5 ,-1 , 0
       0     .03       0    87.9     .16       0  157.54      .1       0
  175.49    .049       0  236.92     .16       0
Bank Sta=137.19,241.52
XS Rating Curve= 0 ,0
Exp/Cntr=0.3,0.1

Type RM Length L Ch R = 1 ,3603.849,52.59,49.8,50.38
XS GIS Cut Line= 5
      319762.478     4050445.651      319786.478    4050462.7566
     319785.2773    4050512.6773     319796.7898    4050575.7398
     319817.2549    4050687.8417
#Sta/Elev= 30
       0  356.99   17.68  355.86   29.47  355.86   59.43  352.81   72.84  352.53
   94.95   353.3  108.55  353.18  124.09  351.85  126.03  351.21  129.91  349.66
  137.68  347.78  141.57  347.44  145.33  347.87  147.51  348.48  153.51  348.14
  157.51  348.58  159.51  349.16  162.38  348.97   163.5  348.73   165.5  347.66
   173.5  345.38   183.5  344.73  193.49  344.77  197.49  345.41  209.49   345.7
  213.48   346.6  220.44  348.99  226.93   351.3  231.48  354.48  257.47  368.76
#Mann= 5 ,-1 , 0
       0     .03       0   72.84     .16       0  145.33      .1       0
  162.38    .049       0  220.44     .16       0
Bank Sta=126.03,226.93
XS Rating Curve= 0 ,0
Exp/Cntr=0.3,0.1

Type RM Length L Ch R = 1 ,3554.046,27.87,48.27,66.62
XS GIS Cut Line= 6
     319740.5663    4050466.0877     319733.6833    4050497.8211
      319733.427    4050536.4477     319748.4031    4050584.5456
     319765.1369    4050683.1355     319767.6532    4050697.9607
#Sta/Elev= 30
       0  355.96   24.83  352.94   36.33  352.36   44.68  352.42   67.24  353.15
   76.91  353.11    86.6  353.41   94.35  353.26   102.1  352.64  104.04  351.99
  105.78  351.15  109.85  349.27  115.66  347.92   117.6  347.69  127.47  348.04
  129.91  347.78  132.24   347.6  141.47  346.29  165.47  345.73  173.47  346.27
  179.47  346.19  183.47  346.36  197.47  348.49  201.36  348.64  203.47  349.66
     206  351.16  213.47  355.46  219.47  358.07  232.75  363.05  236.51  364.19
#Mann= 5 ,-1 , 0
       0     .03       0   44.68     .16       0  129.91      .1       0
  132.24    .049       0  201.36     .16       0
Bank Sta=105.78,206
XS Rating Curve= 0 ,0
Exp/Cntr=0.3,0.1

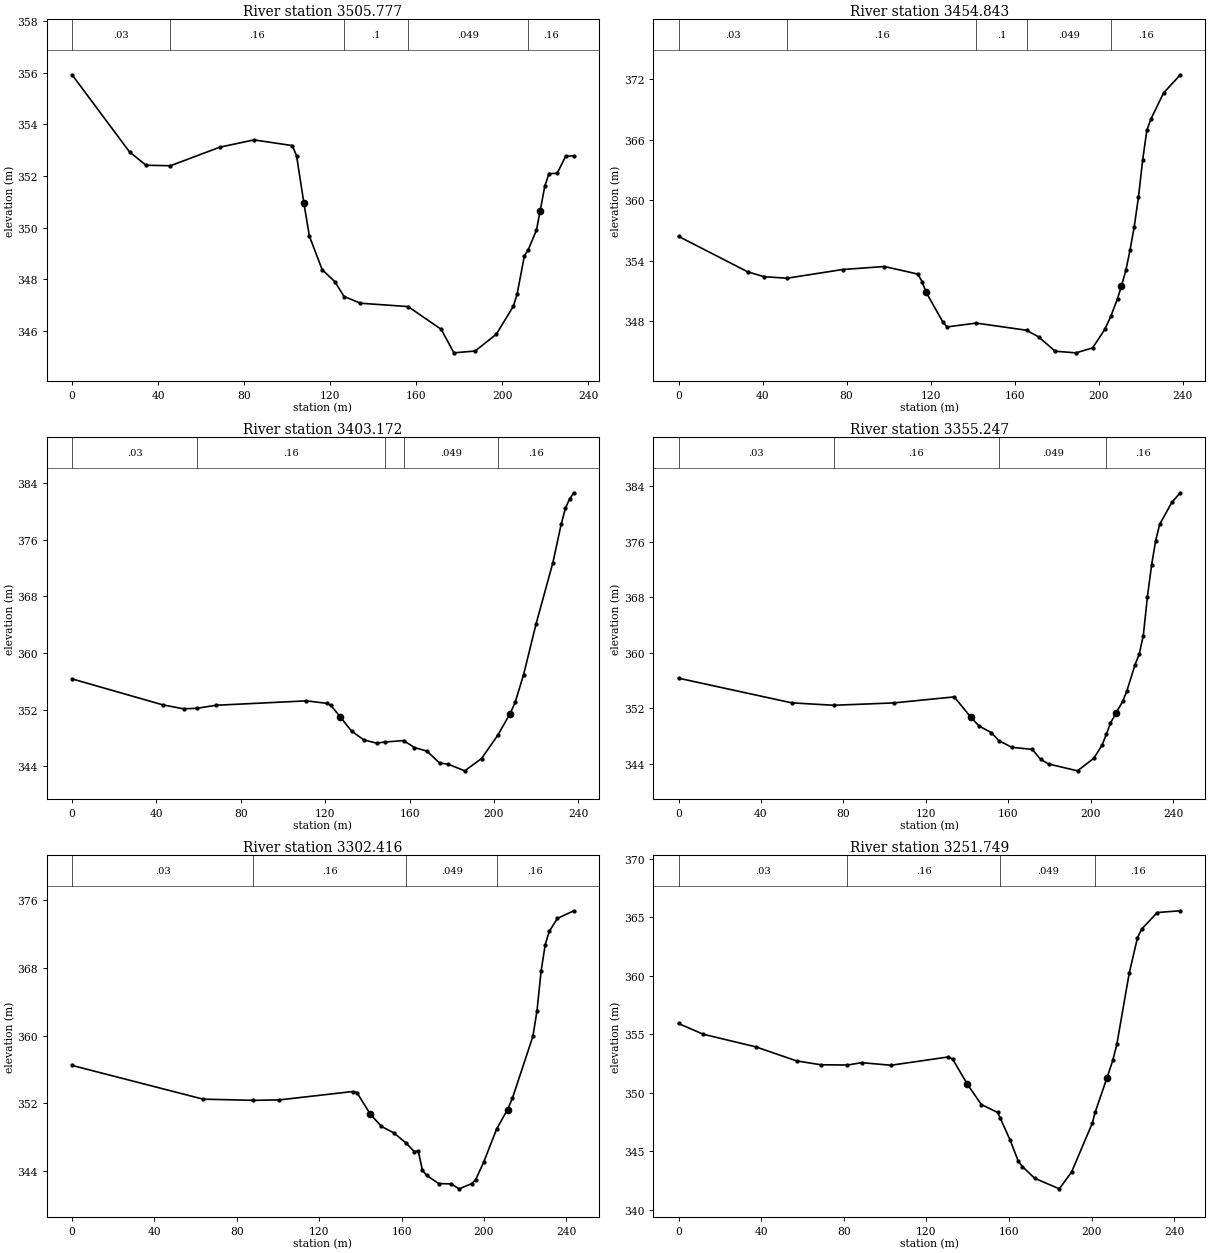
Type RM Length L Ch R = 1 ,3505.777,29.63,50.93,52.42
XS GIS Cut Line= 6
     319722.9439    4050463.1834     319714.2927    4050496.4799
     319715.0937    4050526.8719     319709.0757    4050667.0516
       319703.63     4050671.307     319693.9375    4050690.2194
#Sta/Elev= 30
       0  355.92   26.76  352.93    34.4  352.42   45.74   352.4   68.77  353.12
   84.61   353.4  102.43  353.18  104.41  352.78  107.79  350.96  110.35  349.68
  116.29  348.38  122.23  347.91  126.49  347.34  134.12  347.08  156.28  346.95
  171.65  346.07  177.57  345.16  187.43  345.23   197.3  345.88  205.19  346.96
  206.92  347.42  210.37  348.92   212.1  349.14  215.96  349.91  217.67  350.65
  219.83  351.61  221.76  352.09  225.62  352.11  229.49  352.76  233.35  352.79
#Mann= 5 ,-1 , 0
       0     .03       0   45.74     .16       0  126.49      .1       0
  156.28    .049       0   212.1     .16       0
Bank Sta=107.79,217.67
XS Rating Curve= 0 ,0
Exp/Cntr=0.3,0.1

Type RM Length L Ch R = 1 ,3454.843,47.55,51.67,53.98
XS GIS Cut Line= 6
      319709.207    4050456.3079     319695.3164     4050496.657
     319696.3082    4050526.0918     319675.0953    4050588.2779
     319651.4717    4050657.5312     319642.5664    4050684.0017
#Sta/Elev= 30
       0  356.43   32.97  352.91   40.73  352.43   51.62  352.28    78.1  353.14
   98.01  353.44  113.94  352.69  115.93  351.95  117.88  350.88  125.88  347.93
  127.87  347.45   141.7  347.83   165.7  347.12  171.45  346.46  179.36  345.04
  189.25  344.88  197.16  345.37  203.09  347.25  205.79  348.49  209.02  350.24
   210.9  351.52     213  353.07  214.99  355.07  216.99   357.4  218.98   360.3
  220.98  363.97  222.97  366.93  224.97  368.08  230.95  370.65  238.93  372.45
#Mann= 5 ,-1 , 0
       0     .03       0   51.62     .16       0   141.7      .1       0
   165.7    .049       0  205.79     .16       0
Bank Sta=117.88,210.9
XS Rating Curve= 0 ,0
Exp/Cntr=0.3,0.1

Type RM Length L Ch R = 1 ,3403.172,48.14,47.92,48.07
XS GIS Cut Line= 5
     319676.3162    4050445.5927     319657.4279    4050492.8681
     319656.4585    4050510.2555      319630.456    4050571.0264
     319589.7533    4050666.1535
#Sta/Elev= 30
       0  356.35   43.08  352.68   52.84  352.13   59.15   352.2   68.32  352.63
  111.09  353.25  120.81   352.9  122.76   352.6  127.21  350.96  132.48  348.99
   138.4  347.73  144.37  347.29  148.14  347.44  157.18  347.65  162.28  346.67
  168.25  346.16  174.22  344.48   178.2  344.33  186.16  343.38  194.12  345.12
  201.77  348.38  207.68  351.45  210.04  353.03  214.02   356.9  219.98  364.11
  227.94  372.74  231.92  378.22  233.91  380.43   235.9  381.76  237.89   382.6
#Mann= 5 ,-1 , 0
       0     .03       0   59.15     .16       0  148.14      .1       0
  157.18    .049       0  201.77     .16       0
Bank Sta=127.21,207.68
XS Rating Curve= 0 ,0
Exp/Cntr=0.3,0.1

Type RM Length L Ch R = 1 ,3355.247,54.16,52.83,52.17
XS GIS Cut Line= 5
     319631.3389     4050425.065     319606.6334    4050484.8609
     319604.1327      4050510.72     319586.4121    4050552.1352
     319544.0408    4050651.1619
#Sta/Elev= 30
       0  356.34    54.9  352.78   75.29  352.43  104.39  352.77  133.77  353.64
  141.78  350.71   145.7  349.46  151.68  348.49   155.4  347.33  161.66  346.37
  171.63  346.06  175.62  344.63  179.61  343.95  193.57  342.97  201.55   344.8
  205.54  346.73  207.62  348.28  209.53  349.85   212.3  351.33  215.51  353.02
  217.51  354.51   221.5   358.3  223.49   359.8  225.48  362.49  227.48  368.11
  229.47   372.6  231.47  376.18  233.46  378.57  239.45  381.77  243.44  383.09
#Mann= 4 ,-1 , 0
       0     .03       0   75.29     .16       0   155.4    .049       0
  207.62     .16       0
Bank Sta=141.78,212.3
XS Rating Curve= 0 ,0
Exp/Cntr=0.3,0.1

Type RM Length L Ch R = 1 ,3302.416,50.67,50.67,50.67
XS GIS Cut Line= 4
      319585.983    4050409.5122     319552.5564     4050483.837
     319549.9534    4050498.6644     319494.8524    4050635.0074
#Sta/Elev= 30
       0  356.48   63.61  352.51   87.94  352.37  100.52  352.42  136.29  353.41
  138.28  353.29  144.84  350.72  150.21   349.3  156.17  348.54  162.29  347.32
   166.1  346.34  168.09  346.38  170.08  344.15  172.07  343.54  178.03  342.57
  183.99  342.53  187.96  341.95  193.92  342.55  195.91  343.01  199.89  345.13
  206.18  349.03  211.44  351.29   213.8  352.64  223.73  359.91  225.72  362.93
  227.71  367.59   229.7  370.69  231.68  372.28  235.66   373.8  243.61  374.69
#Mann= 4 ,-1 , 0
       0     .03       0   87.94     .16       0  162.29    .049       0
  206.18     .16       0
Bank Sta=144.84,211.44
XS Rating Curve= 0 ,0
Exp/Cntr=0.3,0.1

Type RM Length L Ch R = 1 ,3251.749,46.85,50.25,52.4
XS GIS Cut Line= 5
     319536.0694    4050397.7958     319508.7342    4050484.2603
     319498.4863    4050490.7921     319452.2697    4050605.1513
     319445.9772    4050620.7217
#Sta/Elev= 30
       0  355.91   11.83     355   37.46  353.91   57.17  352.71      69  352.38
   81.81  352.36   88.71  352.56  102.84  352.34  130.69  353.05  132.68  352.88
  139.88  350.71   146.6  348.98  154.56   348.3  155.74  347.83  160.53  345.95
  164.51  344.13   166.5  343.67  172.47  342.67   184.4  341.77  190.37  343.23
  200.32  347.37  201.73  348.32  207.46  351.27  210.26  352.75  212.25  354.15
  218.22  360.21   222.2  363.23  224.19  363.97  231.78   365.4  242.97  365.55
#Mann= 4 ,-1 , 0
       0     .03       0   81.81     .16       0  155.74    .049       0
  201.73     .16       0
Bank Sta=139.88,207.46
XS Rating Curve= 0 ,0
Exp/Cntr=0.3,0.1