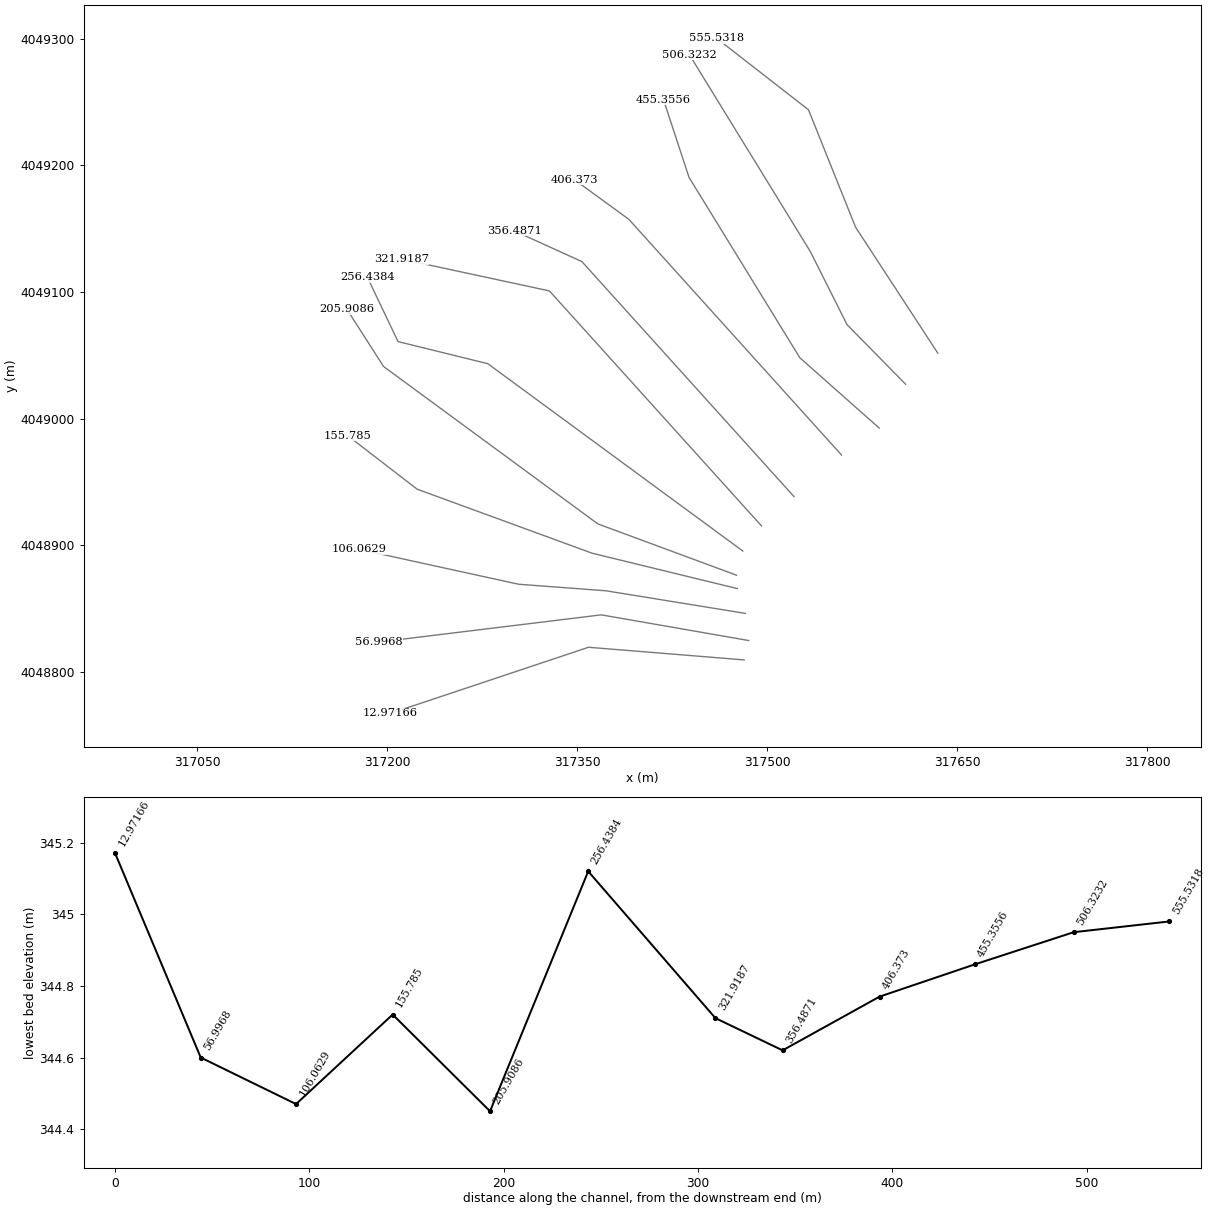
HEC-RAS study WBmod1D.prj: WBmod1D

--- WBmod1D.g09 (geometry) --- (continued)

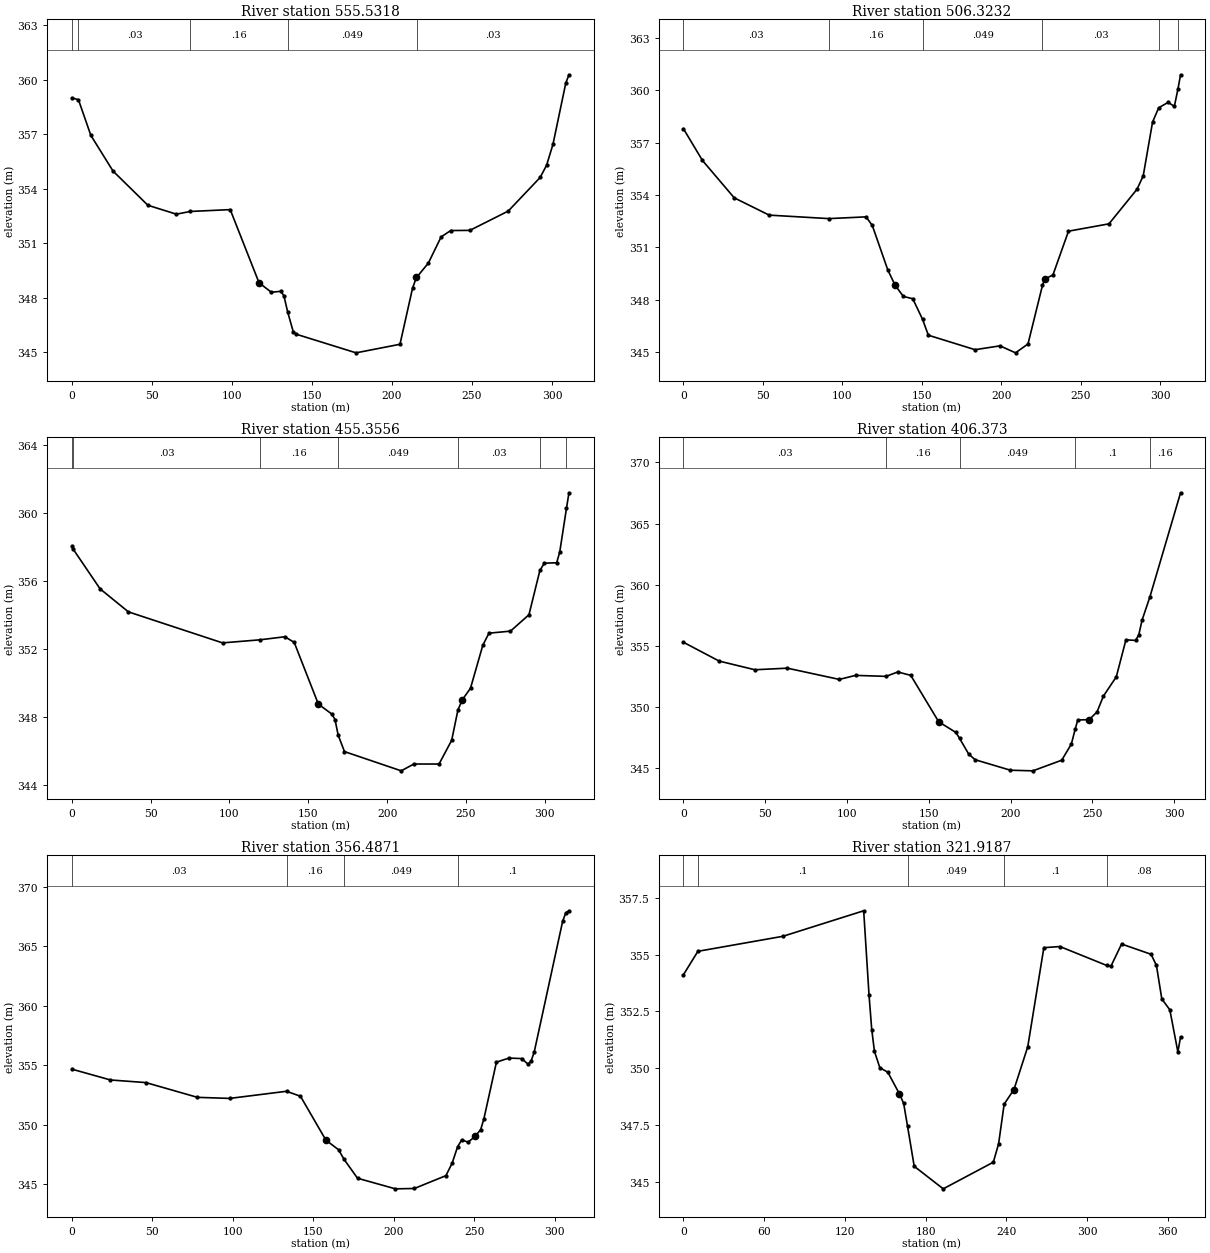
Type RM Length L Ch R = 1 ,555.5318,41.59,49.21,57.69
XS GIS Cut Line= 4
     317634.8213    4049051.7047     317569.8734    4049151.1431
     317532.6444    4049243.9548     317460.1466    4049300.3794
#Sta/Elev= 30
       0  358.99    4.13  358.89   11.88  356.93   25.73  354.97   47.51  353.09
   65.32   352.6   74.06  352.75   98.97  352.85  116.98  348.83  124.65  348.31
  130.53  348.36   132.5  348.12  134.89  347.22  138.38  346.13  140.34     346
  177.59  344.98  205.04  345.45  212.89  348.53  215.34  349.13  215.84  349.17
  222.76  349.91  230.75  351.35  236.74   351.7  248.73  351.71  272.69  352.77
  292.66  354.62  296.66  355.29  300.65  356.44  308.64   359.8  310.64  360.26
#Mann= 5 ,-1 , 0
       0      .1       0    4.13     .03       0   74.06     .16       0
  134.89    .049       0  215.84     .03       0
Bank Sta=116.98,215.34
XS Rating Curve= 0 ,0
Exp/Cntr=0.3,0.1

Type RM Length L Ch R = 1 ,506.3232,50.4,50.97,48.95
XS GIS Cut Line= 5
     317609.3383    4049027.1877     317563.0994    4049074.2391
     317534.0661     4049132.045     317481.7199      4049217.25
     317438.6291    4049287.3899
#Sta/Elev= 30
       0  357.79   11.99  355.97   31.98  353.83   53.97  352.84   91.56  352.64
  114.97  352.74  118.89  352.25   128.7  349.69  133.29  348.82   138.5  348.18
  144.38  348.05  150.55  346.87  154.19  345.96   183.6  345.13  199.28  345.35
  209.09  344.95  216.93  345.46  226.02  348.81  227.49  349.18  232.62  349.41
  242.42  351.92   267.9  352.34  285.54  354.32  289.46  355.09  295.34  358.17
  299.22  358.99  305.14   359.3  309.06  359.07   311.3  360.05  312.97  360.88
#Mann= 6 ,-1 , 0
       0     .03       0   91.56     .16       0  150.55    .049       0
  226.02     .03       0  299.22      .1       0   311.3     .16       0
Bank Sta=133.29,227.49
XS Rating Curve= 0 ,0
Exp/Cntr=0.3,0.1

Type RM Length L Ch R = 1 ,455.3556,38.64,48.98,62.83
XS GIS Cut Line= 5
      317588.478    4048992.5728     317525.8222    4049048.0972
     317490.6391    4049105.3655      317438.293    4049190.5704
     317418.1895    4049251.7595
#Sta/Elev= 30
       0  358.03     .63   357.9   17.94  355.54   35.88  354.19   95.58  352.37
  119.33  352.55  135.12  352.73  141.05   352.4  156.35  348.78  164.93  348.19
  166.93  347.87  168.93  346.96  172.93  345.99  208.93  344.86  216.93  345.26
  232.93  345.26  240.93  346.65  244.93  348.44  247.75  349.04  252.88  349.71
  260.69  352.23  264.59  352.94  278.25  353.06  289.96  354.02  296.89  356.62
  299.72  357.05  307.53  357.07  309.48   357.7  313.76  360.27  315.34  361.18
#Mann= 7 ,-1 , 0
       0      .1       0     .63     .03       0  119.33     .16       0
  168.93    .049       0  244.93     .03       0  296.89      .1       0
  313.76     .16       0
Bank Sta=156.35,247.75
XS Rating Curve= 0 ,0
Exp/Cntr=0.3,0.1

Type RM Length L Ch R = 1 ,406.373 ,49.95,49.89,51.55
XS GIS Cut Line= 4
     317558.8118    4048971.2016     317457.7115    4049083.2281
     317390.7139    4049157.4664     317347.8281    4049188.6979
#Sta/Elev= 30
       0  355.29   21.84  353.75   43.68  353.04   63.54  353.17   95.31  352.25
  105.23  352.58  123.87   352.5  131.05  352.86  138.99  352.58   156.1  348.78
  166.59  347.91  168.82  347.43  174.43  346.14  178.35  345.68  199.92  344.82
  213.65  344.77  231.29  345.64  237.18  346.96   239.5  348.17   241.1  348.93
   248.1  348.96  252.87  349.59   256.8  350.89  264.66  352.46  270.55  355.49
  276.45  355.44  278.41   355.9  280.37  357.08  285.27  359.03  303.95  367.52
#Mann= 5 ,-1 , 0
       0     .03       0  123.87     .16       0  168.82    .049       0
   239.5      .1       0  285.27     .16       0
Bank Sta=156.1,248.1
XS Rating Curve= 0 ,0
Exp/Cntr=0.3,0.1

Type RM Length L Ch R = 1 ,356.4871,34.58,34.57,36.99
XS GIS Cut Line= 4
     317521.1733    4048938.4483      317420.677    4049049.8057
     317353.6794     4049124.044     317300.1798    4049148.3462
#Sta/Elev= 30
       0  354.68      24  353.77      46  353.55      78  352.31      98  352.22
  133.35  352.82     142   352.4  157.77  348.72  165.69   347.9  169.11  347.09
  177.45  345.51  200.98  344.62  212.74  344.65  232.35  345.73  236.27   346.8
  239.56  348.15  242.16  348.74  246.08  348.54  250.45  349.02  253.92   349.6
  255.88  350.48  263.71  355.27  271.55  355.61  279.38  355.57   283.3   355.1
  285.26  355.36  287.21  356.14  304.84  367.11   306.8  367.82  308.76  367.99
#Mann= 4 ,-1 , 0
       0     .03       0  133.35     .16       0  169.11    .049       0
  239.56      .1       0
Bank Sta=157.77,250.45
XS Rating Curve= 0 ,0
Exp/Cntr=0.3,0.1

Type RM Length L Ch R = 1 ,321.9187,54.12,65.48,74.13
XS GIS Cut Line= 4
     317495.5103    4048915.2883      317395.014    4049026.6457
     317328.0164     4049100.884     317211.1221     4049126.048
#Sta/Elev= 30
       0  354.11   10.75  355.14      74   355.8     134  356.92     138   353.2
     140   351.7     142  350.75     146  350.03  151.96  349.83  160.57  348.88
  163.73  348.46  166.63  347.45  171.57   345.7  193.14  344.71  230.39  345.88
  234.31  346.69  238.43  348.43  245.71  349.07  255.98  350.95  267.94   355.3
  279.89  355.35  314.65  354.52  317.76  354.48  325.73  355.46  347.65  355.01
  351.64  354.52  355.62  353.05   361.6  352.57  367.58  350.72  369.57  351.38
#Mann= 5 ,-1 , 0
       0     .03       0   10.75      .1       0  166.63    .049       0
  238.43      .1       0  314.65     .08       0
Bank Sta=160.57,245.71
XS Rating Curve= 0 ,0
Exp/Cntr=0.3,0.1

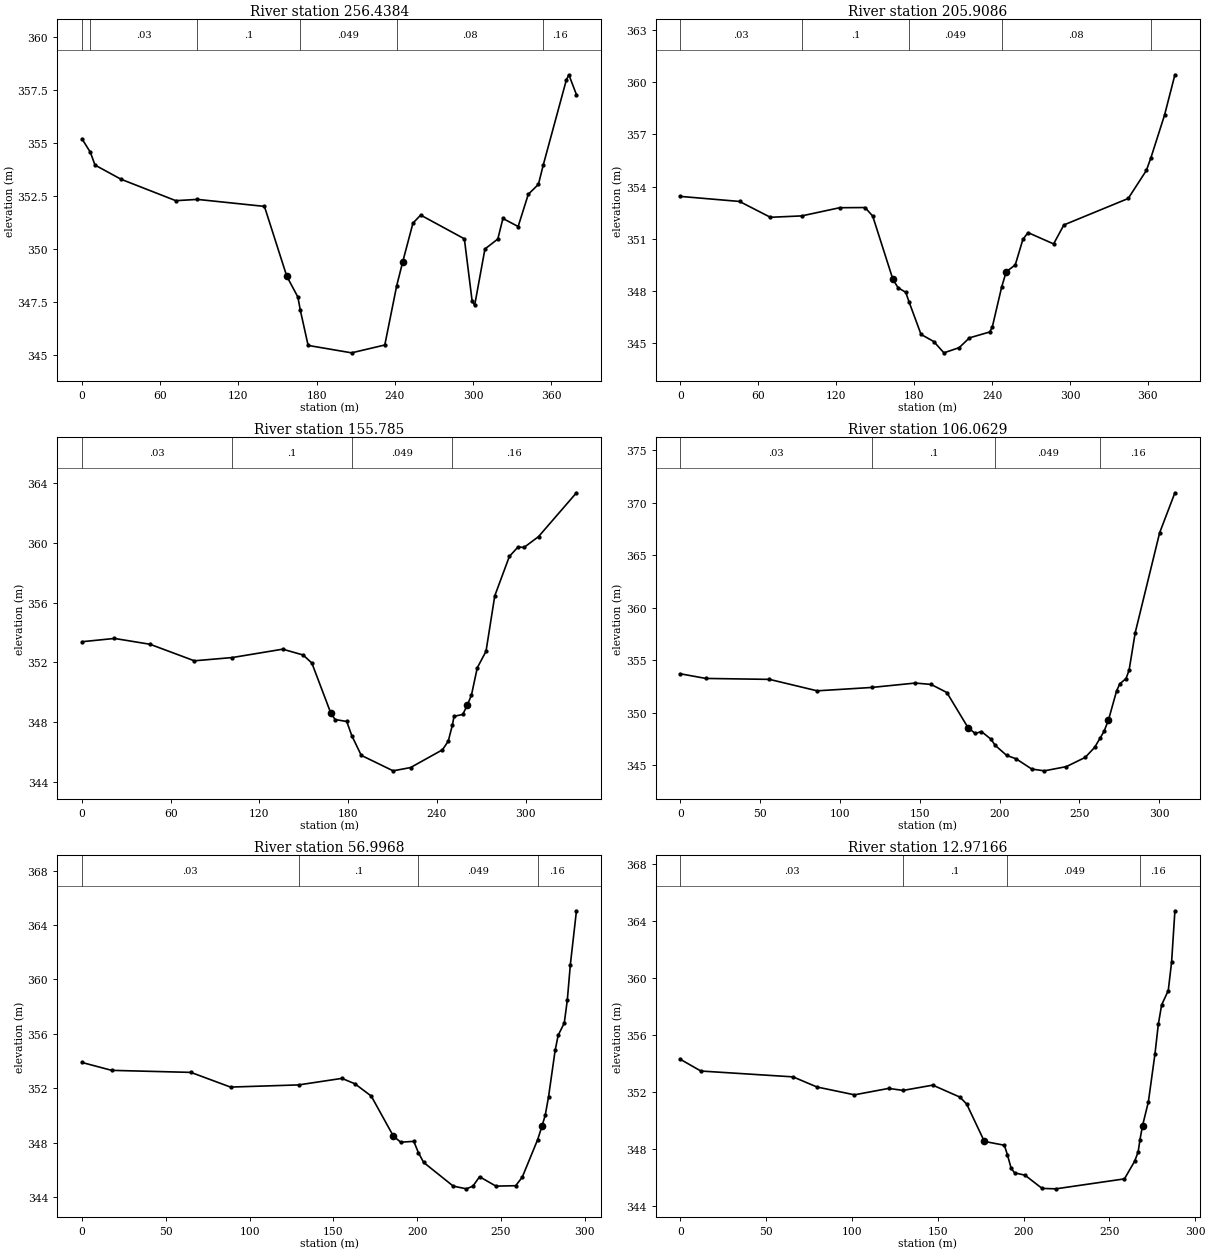
Type RM Length L Ch R = 1 ,256.4384,50.69,50.53,48.8
XS GIS Cut Line= 5
     317480.8344    4048895.3885      317359.947    4048984.1927
     317279.3553    4049043.3956      317208.478     4049060.836
     317184.1717    4049111.7417
#Sta/Elev= 30
       0  355.22    6.48  354.58      10  353.98      30  353.31      72   352.3
    88.6  352.36     140  352.03  157.17  348.73  165.69  347.75   167.5  347.14
  173.53  345.47  206.86  345.12  232.35  345.49   241.5  348.29     246  349.39
  253.95  351.24  259.86  351.62   293.4   350.5  299.32  347.58  301.29  347.36
  309.18  350.02  319.05  350.49  322.99  351.46  334.66  351.08  342.44   352.6
  350.22  353.07  353.96  353.99  371.62  357.99  373.57  358.24   379.4   357.3
#Mann= 6 ,-1 , 0
       0      .1       0    6.48     .03       0    88.6      .1       0
   167.5    .049       0   241.5     .08       0  353.96     .16       0
Bank Sta=157.17,246
XS Rating Curve= 0 ,0
Exp/Cntr=0.3,0.1

Type RM Length L Ch R = 1 ,205.9086,33.57,50.12,63.77
XS GIS Cut Line= 6
     317475.8265    4048876.3234     317366.2822    4048916.8402
     317330.0318    4048943.4699     317249.4401    4049002.6728
     317196.9949    4049041.1992     317167.8832    4049086.6428
#Sta/Elev= 30
       0  353.44   45.53  353.15   69.29  352.24   93.44  352.32  122.66  352.79
  142.22   352.8  148.09  352.31  163.66  348.67  167.66  348.19  173.54  347.93
  176.12  347.37  185.31  345.51  195.11   345.1  202.95  344.45  214.72  344.75
  222.56  345.31  238.25  345.65  240.21  345.94   247.4  348.23  250.91  349.11
  257.86   349.5  263.75  350.97  267.69  351.36  287.41  350.71   295.3   351.8
  344.84  353.32  358.83  354.93  362.34  355.66  372.83  358.11  380.82  360.43
#Mann= 5 ,-1 , 0
       0     .03       0   93.44      .1       0  176.12    .049       0
   247.4     .08       0  362.34     .16       0
Bank Sta=163.66,250.91
XS Rating Curve= 0 ,0
Exp/Cntr=0.3,0.1

Type RM Length L Ch R = 1 ,155.785 ,40.48,49.72,56.84
XS GIS Cut Line= 5
     317476.4879      4048865.74     317361.8644    4048893.6606
     317317.4283    4048909.9165     317223.5152    4048944.2725
     317168.8521    4048986.4221
#Sta/Elev= 30
       0  353.38      22   353.6   45.99  353.21   75.98   352.1  101.71  352.32
  135.72  352.88  149.52  352.49  155.43  351.95  168.29  348.58  171.17  348.16
  179.02  348.03  182.39  347.09  188.82  345.76  210.39  344.72  222.15  344.94
  243.72  346.13  247.64  346.71  250.41  347.78  251.57  348.38  257.45   348.5
  260.44  349.11  263.33   349.8  267.26  351.63  273.18  352.74   279.1  356.46
  288.96   359.1  294.87  359.74  298.82   359.7  308.68  360.43  334.32  363.37
#Mann= 4 ,-1 , 0
       0     .03       0  101.71      .1       0  182.39    .049       0
  250.41     .16       0
Bank Sta=168.29,260.44
XS Rating Curve= 0 ,0
Exp/Cntr=0.3,0.1

Type RM Length L Ch R = 1 ,106.0629,30.91,49.07,64.91
XS GIS Cut Line= 5
     317482.7969    4048846.1564     317372.6639    4048864.0158
     317303.6526    4048869.1923     317207.4705    4048890.2333
     317177.5658    4048896.7753
#Sta/Elev= 30
       0  353.71   15.94  353.27   55.79  353.18   85.67  352.09  119.78  352.41
  147.16  352.83  157.05   352.7  166.94  351.93  180.23  348.58  184.72  348.03
  188.65  348.21  194.56  347.49  197.23   346.9  204.41  345.94  210.31  345.62
  220.16  344.64  228.04  344.47  241.82  344.87  253.63  345.75  259.54   346.7
  263.11  347.62  265.45  348.23  268.24  349.32  273.33  352.09   275.3  352.75
  279.23  353.26  281.15  354.06  284.97  357.62  300.28  367.14  309.85  370.95
#Mann= 4 ,-1 , 0
       0     .03       0  119.78      .1       0  197.23    .049       0
  263.11     .16       0
Bank Sta=180.23,268.24
XS Rating Curve= 0 ,0
Exp/Cntr=0.3,0.1

Type RM Length L Ch R = 1 ,56.9968 ,32.8,44.03,55.2
XS GIS Cut Line= 5
     317485.4176    4048824.7295     317368.9895    4048844.9961
     317305.3277    4048837.2169      317206.066    4048825.0877
      317193.435    4048823.5442
#Sta/Elev= 30
       0  353.89   17.73  353.31      65  353.16   88.63  352.08  129.27  352.24
  155.11  352.72  162.88  352.32   172.6  351.42  185.79  348.48  190.16  348.03
     198  348.09  200.72  347.26  203.88  346.54  221.53   344.8  229.37   344.6
  233.29   344.8  237.22  345.49  247.02   344.8  258.78  344.83  262.71  345.46
   271.9  348.22  274.43  349.19  276.43  350.02  278.39  351.37  282.31  354.77
  284.13  355.89  287.77  356.79  289.59  358.48   291.4  361.09  295.04  365.04
#Mann= 4 ,-1 , 0
       0     .03       0  129.27      .1       0  200.72    .049       0
   271.9     .16       0
Bank Sta=185.79,274.43
XS Rating Curve= 0 ,0
Exp/Cntr=0.3,0.1

Type RM Length L Ch R = 1 ,12.97166,16.12,12.97,13.25
XS GIS Cut Line= 5
      317481.859    4048809.4101     317358.9155    4048819.3992
     317313.8852    4048804.3645     317219.0324    4048772.6953
     317202.5205    4048767.1823
#Sta/Elev= 30
       0  354.26   11.94  353.44   65.65  353.03   79.58  352.32  101.46  351.77
  121.36  352.22  129.83  352.08  147.09  352.45  162.91  351.61  166.87  351.12
  177.16   348.5  188.82  348.23  190.56  347.58  192.82   346.6  194.82  346.29
  200.82  346.13  210.82   345.2  218.82  345.17  258.82  345.87  264.82  347.12
  266.82  347.77  267.88  348.63  269.37  349.61  272.76  351.27  276.63  354.66
  278.56  356.72  280.49  358.08  284.36  359.09   286.3  361.09  288.23  364.69
#Mann= 4 ,-1 , 0
       0     .03       0  129.83      .1       0  190.56    .049       0
  267.88     .16       0
Bank Sta=177.16,269.37
XS Rating Curve= 0 ,0
Exp/Cntr=0.3,0.1
LCMann Table=0